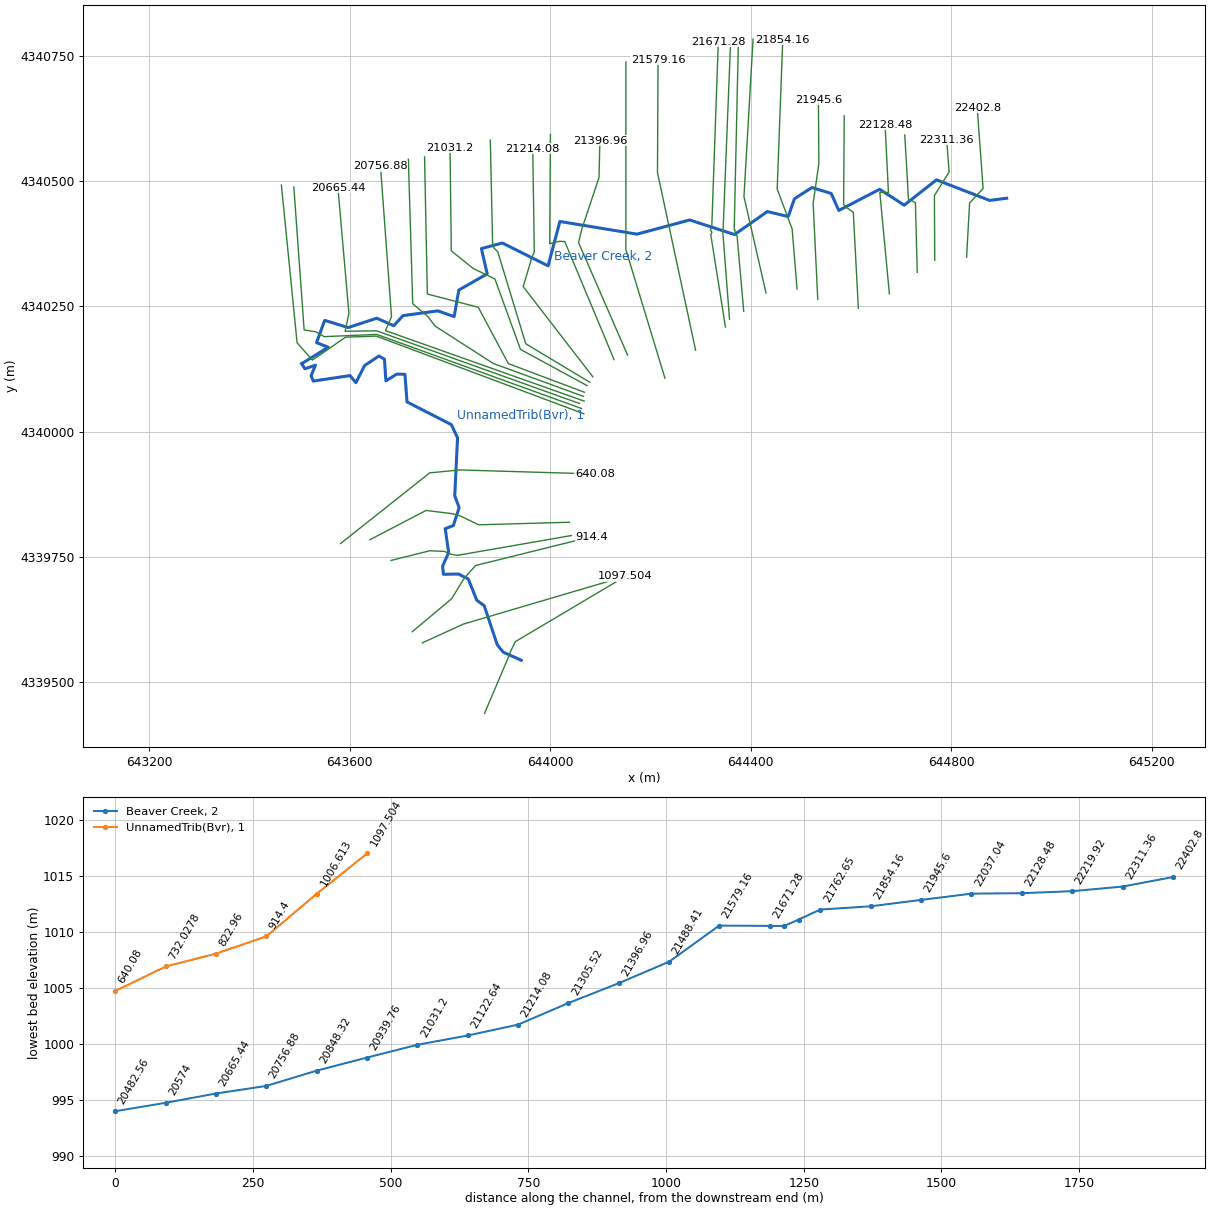
--- BeaverCreek.prj (project) ---

Proj Title=BeaverCreek
Current Plan=p01
Default Exp/Contr=0.3,0.1
SI Units
Geom File=g01
Flow File=f01
Plan File=p01
Background Map Layer=Google Hybrid
Background Map Layer=Bing Satellite
Y Axis Title=Elevation
X Axis Title(PF)=Main Channel Distance
X Axis Title(XS)=Station
BEGIN DESCRIPTION:
September 2018
Tucker County ABFE Study
US Army Corps of Engineers, Pittsburgh District
NAD 1983 UTM 17N (meters)
END DESCRIPTION:
DSS Export Rating Curves= 0
DSS Export Rating Curve Sorted= 0
DSS Export Volume Flow Curves= 0
DXF OffsetX= 0
DXF OffsetY= 0
DXF ScaleX= 1
DXF ScaleY= 10

--- BeaverCreek.p01 (plan) ---

Plan Title=BeaverCreek_plan
Program Version=5.05
Short Identifier=Plan1_subcritical
Geom File=g01
Flow File=f01
Subcritical Flow
K Sum by GR= 0
Std Step Tol= 0.003
Critical Tol= 0.003
Num of Std Step Trials= 20
Max Error Tol= 0.1
Flow Tol Ratio= 0.001
Split Flow NTrial= 30
Split Flow Tol= 0.006
Split Flow Ratio= 0.02
Log Output Level= 0
Friction Slope Method= 1
Unsteady Friction Slope Method= 2
Unsteady Bridges Friction Slope Method= 1
Parabolic Critical Depth
Global Vel Dist= 0 , 0 , 0
Global Log Level= 0
CheckData=True
Encroach Param=-1 ,0,0, 0
Computation Interval=1MIN
Output Interval=1HOUR
Instantaneous Interval=1HOUR
Mapping Interval=1HOUR
Computation Time Step Use Courant=        0
Computation Time Step Use Time Series=    0
Computation Time Step Count To Double=0
Computation Time Step Max Doubling=0
Computation Time Step Max Halving=0
Computation Time Step Residence Courant=0
Run HTab= 0
Run UNet= 0
Run Sediment= 0
Run PostProcess= 0
Run WQNet= 0
Run RASMapper=-1
UNET Theta= 1
UNET Theta Warmup= 1
UNET ZTol= 0.006
UNET ZSATol= 0.006
UNET MxIter= 20
UNET Max Iter WO Improvement= 0
UNET MaxInSteps= 0
UNET DtIC= 0
UNET DtMin= 0
UNET MaxCRTS= 20
UNET WFStab= 2
UNET SFStab= 1
UNET WFX= 1
UNET SFX= 1
UNET 1D Methodology=Finite Difference
UNET DSS MLevel= 4
UNET Pardiso=0
UNET DZMax Abort= 30
UNET Use Existing IB Tables=-1
UNET Froude Reduction=False
UNET Froude Limit= 0.8
UNET Froude Power= 4
UNET D1 Cores= 0
UNET D2 Coriolis=0
UNET D2 Cores= 0
UNET D2 Theta= 1
UNET D2 Theta Warmup= 1
UNET D2 Z Tol= 0.003
UNET D2 Volume Tol= 0.003
UNET D2 Max Iterations= 20
UNET D2 Equation= 0
UNET D2 RampUpFraction=0.1
UNET D2 TimeSlices= 1
UNET D2 BCVolumeCheck=0
UNET D1D2 MaxIter= 0
UNET D1D2 ZTol=0.003
UNET D1D2 QTol=0.1
UNET D1D2 MinQTol=0.03
Write IC File= 0
Write IC File at Fixed DateTime=0
Write IC File at Sim End=0
Echo Input=False
Echo Parameters=False
Echo Output=False
Write Detailed= 0
HDF Write Warmup=0
HDF Write Time Slices=0
HDF Flush=0
HDF Face Node Velocities=0
HDF Compression= 1
HDF Chunk Size= 1
HDF Spatial Parts= 1
HDF Use Max Rows=0
HDF Fixed Rows= 1
Calibration Method= 0
Calibration Iterations= 20
Calibration Max Change=0.05
Calibration Tolerance=0.2
Calibration Maximum=1.5
Calibration Minimum=0.5
Calibration Optimization Method= 1
WQ AD Non Conservative
WQ ULTIMATE=-1
WQ Max Comp Step=1HOUR
WQ Output Interval=15MIN
WQ Output Selected Increments= 0
WQ Output face flow=0
WQ Output face velocity=0
WQ Output face area=0
WQ Output face dispersion=0
WQ Output cell volume=0
WQ Output cell surface area=0
WQ Output cell continuity=0
WQ Output cumulative cell continuity=0
WQ Output face conc=0
WQ Output face dconc_dx=0
WQ Output face courant=0
WQ Output face peclet=0
WQ Output face adv mass=0
WQ Output face disp mass=0
WQ Output cell mass=0
WQ Output cell source sink temp=0
WQ Output nsm pathways=0
WQ Output nsm derived pathways=0
WQ Output MaxMinRange=-1
WQ Daily Max Min Mean=-1
WQ Daily Range=0
WQ Daily Time=0
WQ Create Restart=0
WQ Fixed Restart=0
WQ System Summary=0
WQ Write To DSS=0
WQ Use Fixed Temperature=0
Sorting and Armoring Iterations= 10
XS Update Threshold= 0.02
Bed Roughness Predictor= 0
Hydraulics Update Threshold= 0.02
Energy Slope Method= 1
Volume Change Method= 1
Sediment Retention Method= 0
XS Weighting Method= 0
Number of US Weighted Cross Sections= 1
Number of DS Weighted Cross Sections= 1
Upstream XS Weight=0
Main XS Weight=1
Downstream XS Weight=0
Number of DS XS's Weighted with US Boundary= 1
Upstream Boundary Weight= 1
Weight of XSs Associated with US Boundary= 0
Number of US XS's Weighted with DS Boundary= 1
Downstream Boundary Weight= 0.5
Weight of XSs Associated with DS Boundary= 0.5
Percentile Method= 0
Sediment Output Level= 4
Mass or Volume Output= 0
Output Increment Type= 1
Profile and TS Output Increment= 1
XS Output Flag= 0
XS Output Increment= 10
Write Gradation File= 0
Read Gradation Hotstart= 0
Write HDF5 File= 1
Write Binary Output= 1
Write DSS Sediment File= 0
SV Curve= 0
Specific Gage Flag= 0

--- BeaverCreek.f01 (steady flow) ---

Flow Title=BeaverCreek_flow
Program Version=5.05
Number of Profiles= 1
Profile Names=PF 1
River Rch & RM=Beaver Creek,2               ,22402.8
   14.64
River Rch & RM=Beaver Creek,2               ,21214.08
 16.0555
River Rch & RM=Beaver Creek,2               ,20482.56
 16.8484
River Rch & RM=Beaver Creek,1               ,20391.12
   28.33
River Rch & RM=Beaver Creek,1               ,20025.39
 28.5997
River Rch & RM=Beaver Creek,1               ,19476.72
 32.3375
River Rch & RM=Beaver Creek,1               ,18562.32
 32.8189
River Rch & RM=Beaver Creek,1               ,18013.68
 39.9547
River Rch & RM=Beaver Creek,1               ,17465.04
 41.4838
River Rch & RM=Beaver Creek,1               ,16916.4
 42.1068
River Rch & RM=Beaver Creek,1               ,14996.16
  45.618
River Rch & RM=Beaver Creek,1               ,14356.08
 50.5451
River Rch & RM=Beaver Creek,1               ,13533.12
 55.7837
River Rch & RM=Beaver Creek,1               ,12618.72
 62.0416
River Rch & RM=Beaver Creek,1               ,10424.16
 68.3845
River Rch & RM=Beaver Creek,1               ,8046.72
 73.6231
River Rch & RM=Beaver Creek,1               ,6858
 83.7888
River Rch & RM=Beaver Creek,1               ,4663.44
 91.5192
River Rch & RM=Beaver Creek,1               ,2103.12
  98.032
River Rch & RM=Beaver Creek,1               ,1097.28
 100.411
River Rch & RM=UnnamedTrib(Bvr),1               ,1097.504
   14.64
River Rch & RM=UnnamedTrib(Bvr),1               ,91.43998
 15.5458
Boundary for River Rch & Prof#=Beaver Creek,2               , 1
Up Type= 2
Dn Type= 0
Boundary for River Rch & Prof#=Beaver Creek,1               , 1
Up Type= 0
Dn Type= 1
Dn Known WS=938.8
Boundary for River Rch & Prof#=UnnamedTrib(Bvr),1               , 1
Up Type= 2
Dn Type= 0
DSS Import GetInterval= 0
DSS Import GetPeak= 0
DSS Import FillOption= 0

--- BeaverCreek.g01 (geometry) ---

Geom Title=BeaverCreek_geometry
Program Version=5.05

Junct Name=1
Junct Desc=, 0 , 0 ,-1 ,0
Up River,Reach=Beaver Creek    ,2
Up River,Reach=UnnamedTrib(Bvr),1
Dn River,Reach=Beaver Creek    ,1
Junc L&A=92,
Junc L&A=125,

River Reach=Beaver Creek    ,2
Reach XY= 30
     644910.8301    4340465.3427     644876.6988    4340460.9771
     644770.6467     4340501.982     644706.4057    4340451.5494
     644657.4048    4340483.1436      644575.913    4340441.0219
     644560.6729    4340474.8886     644522.2569    4340486.7051
     644487.3637    4340464.1521     644475.0605    4340428.8301
     644433.3886     4340438.752     644367.9705    4340392.8913
     644278.5207    4340421.9718     644173.2365    4340393.7066
     644019.5989    4340418.9556     643996.0314    4340330.4049
       643904.75    4340376.0456      643863.078    4340364.9331
     643874.5874    4340314.5299      643817.986    4340282.1657
     643808.7061    4340229.2016     643776.1622     4340240.711
      643706.709     4340231.186     643688.1484    4340211.0727
     643654.3214    4340226.0266     643597.1713    4340207.3734
     643550.5055     4340221.745     643534.1542    4340177.2949
     643557.6493    4340168.2461     643504.6267    4340135.3848

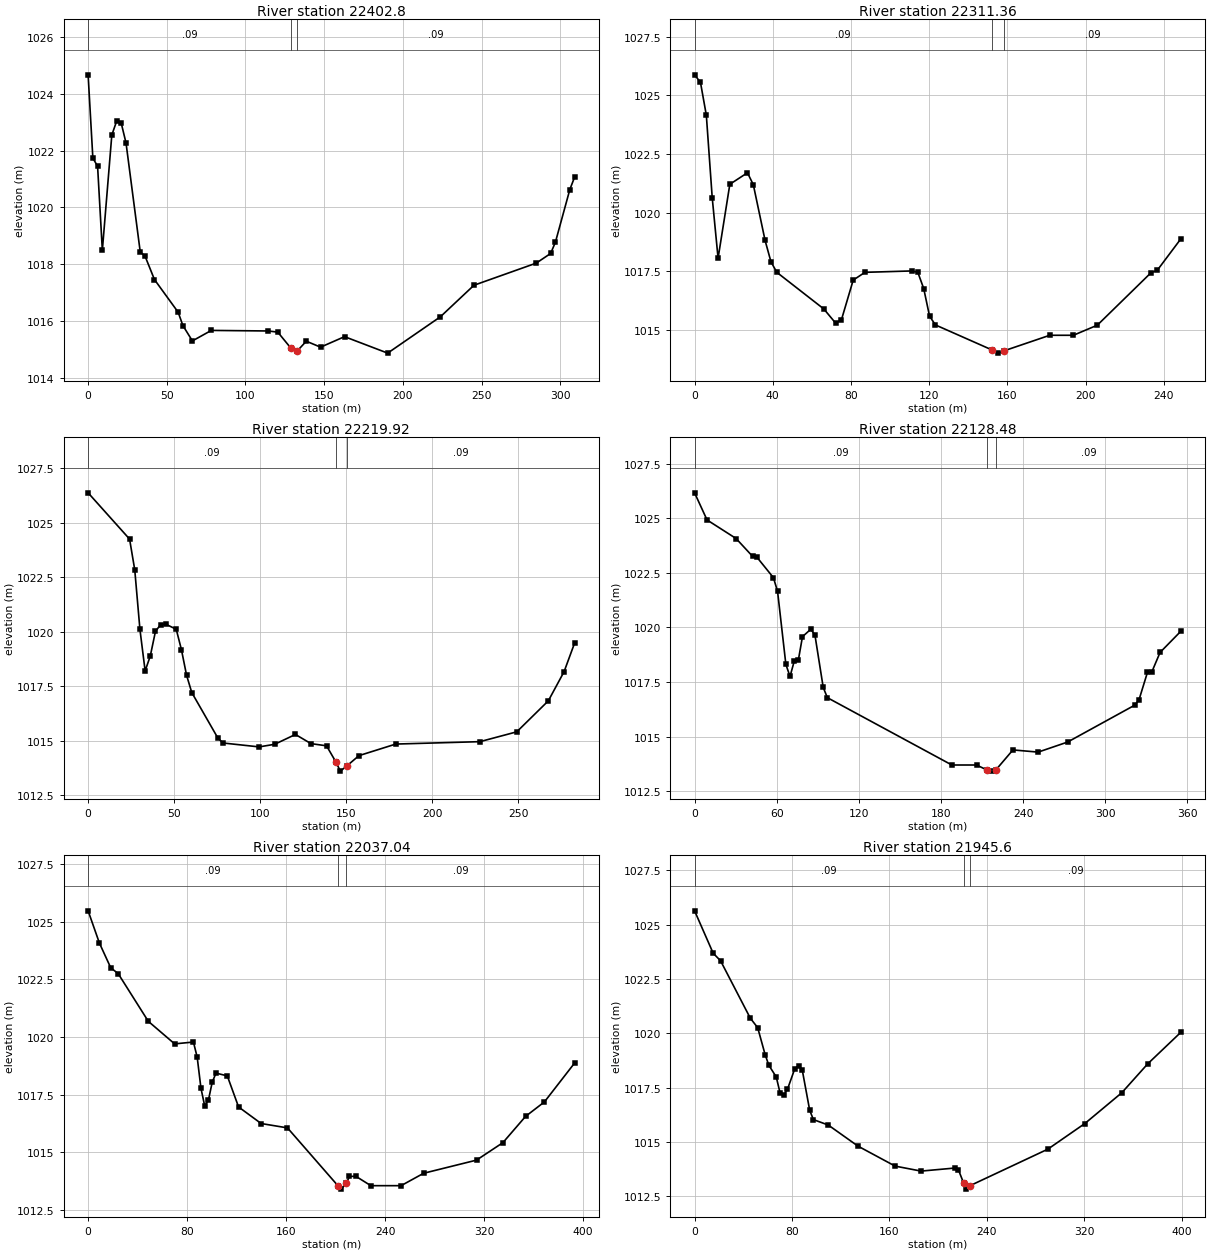
Type RM Length L Ch R = 1 ,22402.8 ,91.01,91.44,93.5
XS GIS Cut Line= 4
     644830.7883    4340347.7807     644836.8198    4340456.0351
     644863.7324     4340484.657644851.9975141824340645.66816937
#Sta/Elev= 30
       0 1024.67    3.01 1021.74    6.02 1021.45    9.04 1018.49   15.06 1022.55
   18.07 1023.03   21.08 1022.96   24.09 1022.27   33.13 1018.43   36.14 1018.29
   42.16 1017.46   57.22 1016.31   60.23 1015.84   66.26  1015.3    78.3 1015.67
  114.47 1015.65  120.51 1015.61  128.64 1015.06   132.6 1014.93  138.64 1015.29
  147.71 1015.08  162.94 1015.45  190.35 1014.87  223.86 1016.15  245.18 1017.26
  284.78 1018.04  293.92 1018.38  296.96 1018.78   306.1 1020.63  309.15 1021.07
#Mann= 3 , 0 , 0
       0     .09       0  128.64     .04       0   132.6     .09       0
Bank Sta=128.64,132.6
XS Rating Curve= 0 ,0
Exp/Cntr=0.3,0.1

Type RM Length L Ch R = 1 ,22311.36,89.81,91.44,94.11
XS GIS Cut Line= 4
     644767.2882    4340341.4307     644766.6287    4340470.6579
     644795.9476    4340517.6198644791.1019471894340581.71669958
#Sta/Elev= 30
       0 1025.87    3.01 1025.55    6.01 1024.15    9.02 1020.64   12.02 1018.06
   18.03 1021.21   27.05  1021.7   30.05 1021.19   36.06 1018.82   39.07 1017.91
   42.07 1017.46   66.12  1015.9   72.13  1015.3   75.13 1015.44   81.14 1017.13
   87.15 1017.46   111.2 1017.52   114.2 1017.46  117.21 1016.77  120.21 1015.59
  123.22 1015.22  152.03 1014.16  155.45 1014.02  158.37 1014.12  181.68 1014.78
  193.77 1014.78  206.02 1015.21  233.56 1017.45  236.62 1017.54  248.87  1018.9
#Mann= 3 , 0 , 0
       0     .09       0  152.03     .04       0  158.37     .09       0
Bank Sta=152.03,158.37
XS Rating Curve= 0 ,0
Exp/Cntr=0.3,0.1

Type RM Length L Ch R = 1 ,22219.92,98.55,91.44,86.79
XS GIS Cut Line= 6
     644732.3631    4340317.6181     644728.6847    4340456.1347
     644719.8409    4340461.8379     644718.6834    4340461.8497
     644714.8734    4340463.3843644707.5107617024340591.58884906
#Sta/Elev= 30
       0 1026.36    24.1 1024.24   27.11 1022.83   30.12  1020.1   33.14  1018.2
   36.15 1018.89   39.16 1020.02   42.17 1020.32   45.18 1020.34   51.21 1020.11
   54.22 1019.18   57.23    1018   60.25 1017.21   75.31 1015.14   78.32  1014.9
   99.41 1014.72  108.44 1014.84  120.49 1015.29  129.53 1014.87  138.57 1014.77
  143.93 1014.04  146.61 1013.61  150.25 1013.84  157.42 1014.32  178.82 1014.85
  227.74 1014.96  249.14 1015.41  267.48 1016.83  276.66 1018.17  282.77 1019.48
#Mann= 3 , 0 , 0
       0     .09       0  143.93     .04       0  150.25     .09       0
Bank Sta=143.93,150.25
XS Rating Curve= 0 ,0
Exp/Cntr=0.3,0.1

Type RM Length L Ch R = 1 ,22128.48,84.99,91.44,100.02
XS GIS Cut Line= 4
     644676.8005    4340274.7556     644657.7175    4340476.9815
       644674.91    4340476.7819644668.215713002 4340611.7493402
#Sta/Elev= 30
       0 1026.16     9.1 1024.92   30.32 1024.07   42.44 1023.25   45.48 1023.22
    57.6 1022.28   60.63 1021.65    66.7 1018.31   69.73 1017.76   72.76 1018.45
   75.79  1018.5   78.82 1019.58   84.89 1019.92   87.92 1019.66   93.98 1017.26
   97.01 1016.79  187.97 1013.71  205.99 1013.71  213.73 1013.48  217.45 1013.43
  220.32  1013.5   232.6  1014.4  251.03  1014.3  272.53 1014.76  321.67 1016.45
  324.74  1016.7  330.88 1017.95  333.95 1017.95  340.09 1018.86  355.45 1019.84
#Mann= 3 , 0 , 0
       0     .09       0  213.73     .04       0  220.32     .09       0
Bank Sta=213.73,220.32
XS Rating Curve= 0 ,0
Exp/Cntr=0.3,0.1

Type RM Length L Ch R = 1 ,22037.04,108.9,91.44,86.76
XS GIS Cut Line= 6
     644614.8879    4340246.1805     644604.8299     4340437.395
     644592.0971    4340446.2564     644591.0119     4340447.503
     644585.5682    4340452.8467644586.7089635914340629.68634238
#Sta/Elev= 30
       0 1025.48    9.12 1024.08   18.24 1023.01   24.31 1022.75   48.63 1020.68
   69.91  1019.7    85.1 1019.78   88.14 1019.12   91.18 1017.77   94.22    1017
   97.26 1017.27   100.3 1018.04  103.34 1018.43  112.46 1018.31  121.57 1016.96
  139.81 1016.24  161.09 1016.05  201.82 1013.54  204.41 1013.39  208.64 1013.65
  211.19 1013.94  216.27 1013.95  228.47 1013.54  252.86 1013.54  271.15 1014.08
  313.84 1014.65  335.18 1015.41  353.48 1016.55  368.72 1017.18  393.11 1018.87
#Mann= 3 , 0 , 0
       0     .09       0  201.82     .04       0  208.64     .09       0
Bank Sta=201.82,208.64
XS Rating Curve= 0 ,0
Exp/Cntr=0.3,0.1

Type RM Length L Ch R = 1 ,21945.6 ,90.92,91.44,93.65
XS GIS Cut Line= 4
     644533.9252     4340263.643     644524.7657    4340455.5146
      644536.174    4340534.4453644535.247719407 4340662.0828058
#Sta/Elev= 30
       0 1025.64   15.25 1023.69   21.34 1023.34   45.74  1020.7   51.83 1020.26
   57.93 1019.02   60.98 1018.53   67.08 1017.99   70.13 1017.27   73.18 1017.16
   76.23 1017.42   82.32 1018.38   85.37 1018.52   88.42 1018.31   94.52 1016.46
   97.57 1016.03  109.77 1015.78  134.16 1014.81  164.65 1013.89  185.99 1013.66
  213.56  1013.8  216.63 1013.72  220.99  1013.1  222.76 1012.83  225.83 1012.98
  290.08 1014.67  320.47 1015.85  350.86 1017.27  372.13  1018.6  399.48 1020.06
#Mann= 3 , 0 , 0
       0     .09       0  220.99     .04       0  225.83     .09       0
Bank Sta=220.99,225.83
XS Rating Curve= 0 ,0
Exp/Cntr=0.3,0.1

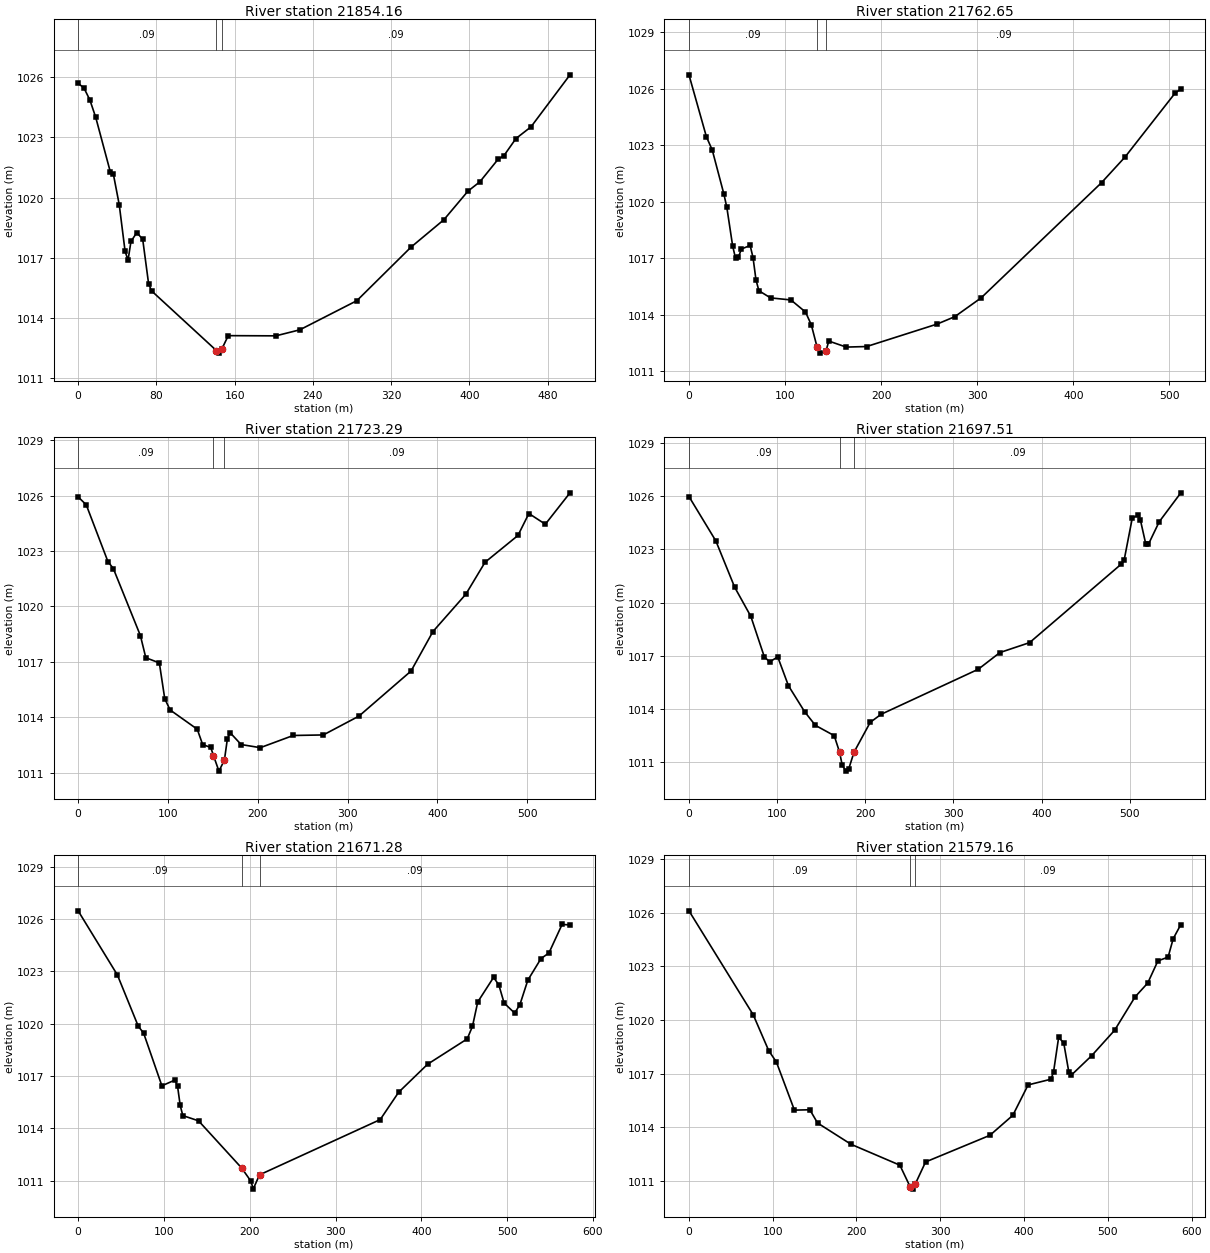
Type RM Length L Ch R = 1 ,21854.16,90.59,91.51,92.94
XS GIS Cut Line= 4
     644492.6501    4340284.2806     644482.8868    4340403.9228
     644452.9995    4340483.6217     644464.1084    4340781.1085
#Sta/Elev= 30
       0 1025.69       6 1025.45      12 1024.86   18.01 1023.99   33.01 1021.26
   36.01 1021.17   42.01 1019.65   48.02 1017.32   51.02 1016.89   54.02 1017.82
   60.02 1018.26   66.02 1017.92   72.02 1015.72   75.02 1015.36  141.32 1012.39
  144.36 1012.26  146.96 1012.47  153.48 1013.13  202.12 1013.12  226.64 1013.42
  284.95 1014.87   340.2 1017.53  373.95  1018.9  398.51 1020.32  410.78 1020.79
   429.2  1021.9  435.33 1022.09  447.61 1022.94  462.96 1023.52  502.85 1026.11
#Mann= 3 , 0 , 0
       0     .09       0  141.32     .04       0  146.96     .09       0
Bank Sta=141.32,146.96
XS Rating Curve= 0 ,0
Exp/Cntr=0.3,0.1

Type RM Length L Ch R = 1 ,21762.65,36.95,39.37,35.77
XS GIS Cut Line= 3
     644430.7375    4340276.3431     644386.7329    4340468.4276
     644404.8966    4340782.6903
#Sta/Elev= 30
       0 1026.73   18.19 1023.44   24.25 1022.74   36.38  1020.4   39.41  1019.7
   45.48 1017.65   48.51 1016.99   51.54 1017.07   54.57 1017.49   63.67 1017.68
    66.7 1017.03   69.73 1015.86   72.76 1015.28   84.89  1014.9  106.11 1014.79
  121.27 1014.15  127.33 1013.47  133.39 1012.28  136.43 1011.97  142.49 1012.07
  145.52 1012.61  163.71 1012.29  184.93 1012.32  258.18 1013.51  276.52  1013.9
  304.03  1014.9  429.33 1021.01  453.78 1022.37  505.73 1025.75  511.85 1025.98
#Mann= 3 , 0 , 0
       0     .09       0  133.39     .04       0  142.49     .09       0
Bank Sta=133.39,142.49
XS Rating Curve= 0 ,0
Exp/Cntr=0.3,0.1

Type RM Length L Ch R = 1 ,21723.29,28.54,25.78,25.88
XS GIS Cut Line= 6
     644386.2874    4340239.8305      644373.036    4340389.9597
      644368.935    4340394.4576     644368.7365    4340402.2628
     644367.2813    4340402.8581     644375.7656    4340784.2603
#Sta/Elev= 30
       0 1025.93    9.04  1025.5   33.16 1022.43   39.19 1022.05   69.33 1018.42
   75.36 1017.22   90.43 1016.94   96.46    1015  102.48 1014.39  132.63 1013.35
  138.66 1012.52   147.7 1012.36  150.71 1011.92   156.8 1011.08   162.9 1011.68
  166.24 1012.84  169.29 1013.16   181.5 1012.52  202.86 1012.35  239.49 1013.01
  273.06 1013.04  312.74 1014.06  370.72  1016.5  395.14 1018.64  431.76 1020.66
  453.13 1022.39  489.75 1023.84  501.96 1025.03  520.27 1024.45  547.74 1026.15
#Mann= 3 , 0 , 0
       0     .09       0  150.71     .04       0   162.9     .09       0
Bank Sta=150.71,162.9
XS Rating Curve= 0 ,0
Exp/Cntr=0.3,0.1

Type RM Length L Ch R = 1 ,21697.51,23.4,26.23,28.95
XS GIS Cut Line= 6
      644357.924    4340223.9907     644344.8234    4340394.3244
     644344.5853    4340397.3407     644344.5853    4340398.7694
     644345.2203    4340404.5638     644360.2576    4340781.0674
#Sta/Elev= 30
       0 1025.98   30.51 1023.48   51.86 1020.87   70.17 1019.23   85.42 1016.96
   91.52 1016.66  100.67 1016.95  112.87 1015.32  131.18 1013.86  143.38 1013.09
  164.74 1012.51  170.84 1011.58  173.86 1010.84  178.21 1010.51  181.12 1010.62
  187.25 1011.58  205.63 1013.26  217.88 1013.71  328.17 1016.25  352.67 1017.19
  386.37 1017.75  490.53 1022.18  493.59 1022.39  502.78 1024.75  508.91 1024.93
  511.97 1024.68   518.1 1023.32  521.16 1023.29  533.42 1024.56  557.92 1026.19
#Mann= 3 , 0 , 0
       0     .09       0  170.84     .04       0  187.25     .09       0
Bank Sta=170.84,187.25
XS Rating Curve= 0 ,0
Exp/Cntr=0.3,0.1

Type RM Length L Ch R = 1 ,21671.28,104.8,92.12,94.25
XS GIS Cut Line= 6
     644349.7881    4340208.5567     644320.6148    4340392.3121
     644322.8373    4340397.3921     644319.9622    4340401.7365
     644322.6437    4340410.7845     644335.5513    4340777.3901
#Sta/Elev= 30
       0 1026.48   45.75  1022.8   70.15 1019.85   76.25 1019.47    97.6 1016.44
  112.85 1016.77   115.9  1016.4  118.95 1015.31     122 1014.73  140.31 1014.43
  190.42 1011.73  201.59 1010.95  203.95 1010.51   211.4 1011.33  352.03  1014.5
  373.53 1016.07  407.32 1017.68   453.4 1019.13  459.54 1019.85  465.69 1021.25
  484.12 1022.66  490.26 1022.23  496.41 1021.19  508.69 1020.61  514.84  1021.1
  524.05  1022.5  539.41 1023.74  548.63 1024.06  563.99  1025.7   573.2 1025.67
#Mann= 3 , 0 , 0
       0     .09       0  190.42     .04       0   211.4     .09       0
Bank Sta=190.42,211.4
XS Rating Curve= 0 ,0
Exp/Cntr=0.3,0.1

Type RM Length L Ch R = 1 ,21579.16,92.11,90.75,90.48
XS GIS Cut Line= 3
     644290.2567    4340162.2545     644214.2519    4340516.5356
     644215.4015    4340741.4122
#Sta/Elev= 30
       0 1026.11   76.77 1020.29   95.19 1018.29   104.4 1017.65   125.9 1014.96
  144.32 1014.98  153.53 1014.24  193.45 1013.05   251.8 1011.88  264.08 1010.67
  267.15 1010.54  270.22 1010.83   282.5 1012.06  359.27 1013.55  386.65 1014.67
  404.89 1016.37  432.24 1016.69  435.28  1017.1  441.35 1019.03  447.43 1018.72
  453.51 1017.09  456.55 1016.92  480.86 1018.01  508.21 1019.43  532.52 1021.29
  547.72 1022.07  559.87 1023.31  572.03 1023.52   578.1 1024.55  587.22 1025.34
#Mann= 3 , 0 , 0
       0     .09       0  264.08     .04       0  270.22     .09       0
Bank Sta=264.08,270.22
XS Rating Curve= 0 ,0
Exp/Cntr=0.3,0.1

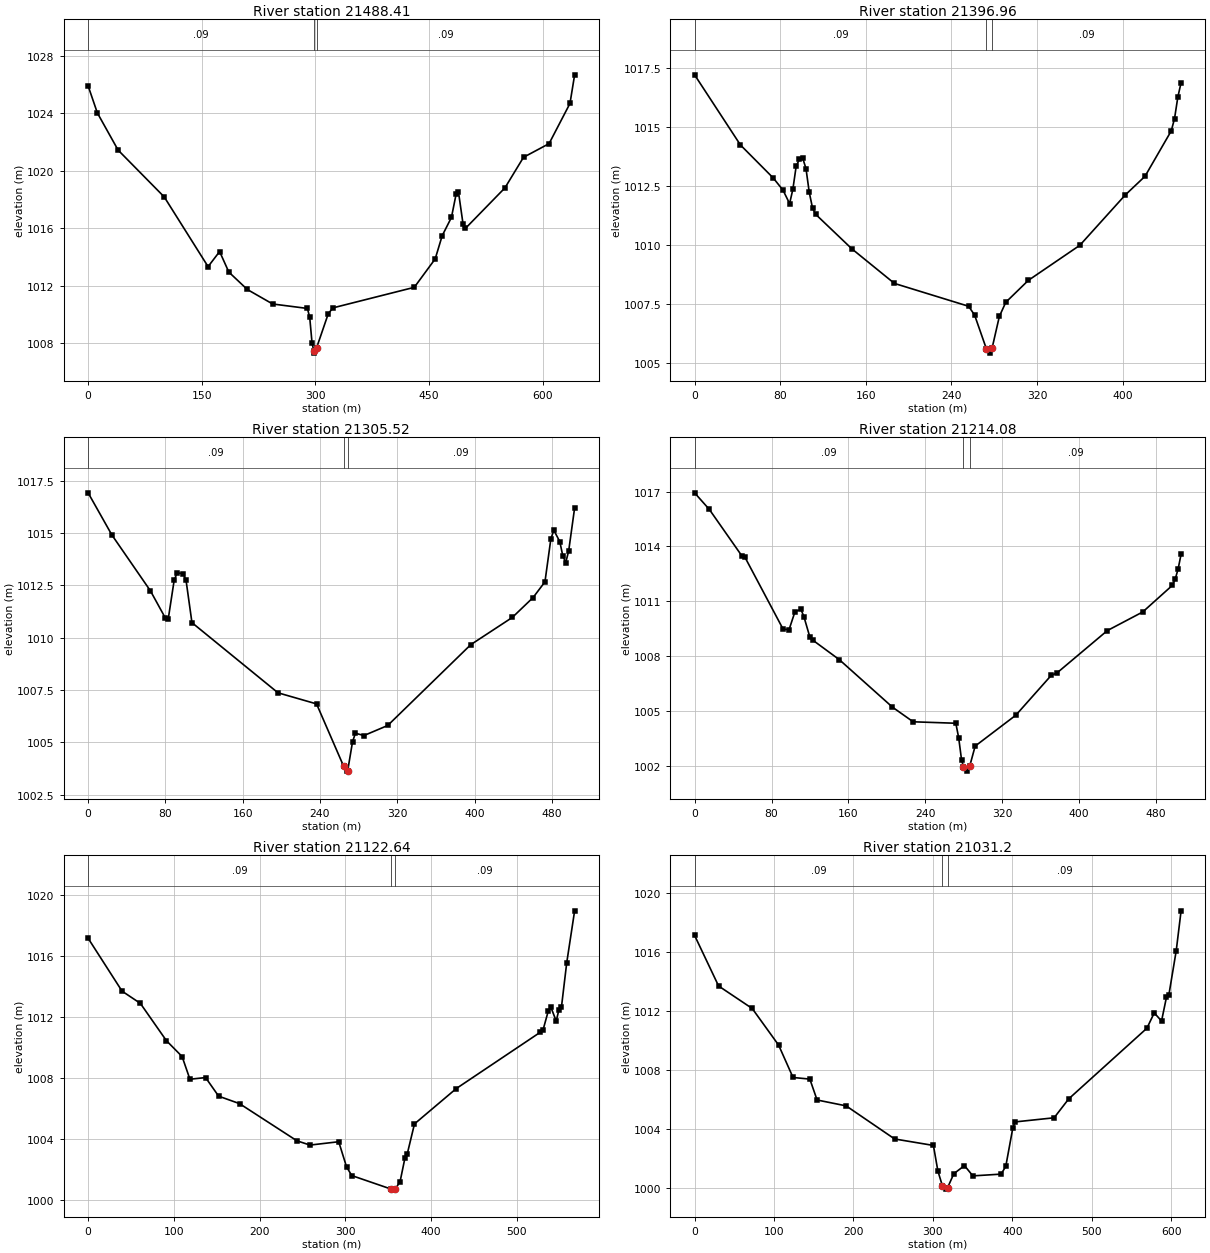
Type RM Length L Ch R = 1 ,21488.41,90.96,91.45,90.69
XS GIS Cut Line= 3
     644229.1378    4340106.4273     644151.1837    4340362.8837
     644151.2555    4340737.1939
#Sta/Elev= 30
       0 1025.92   12.18 1024.04    39.6 1021.45  100.52 1018.19  158.39 1013.34
  173.62 1014.39   185.8 1012.96  210.17 1011.75  243.67 1010.74  289.52 1010.43
  292.59 1009.81  295.66 1008.02  297.92  1007.5  298.72 1007.32  301.79 1007.71
  317.13 1010.07  323.27 1010.47  430.65  1011.9  458.27 1013.88  467.47 1015.49
  479.74 1016.77  485.88 1018.39  488.95 1018.55  495.08 1016.29  498.15    1016
  550.31 1018.82  574.86 1020.95   608.6  1021.9  636.22  1024.7  642.35 1026.69
#Mann= 3 , 0 , 0
       0     .09       0  297.92     .04       0  301.79     .09       0
Bank Sta=297.92,301.79
XS Rating Curve= 0 ,0
Exp/Cntr=0.3,0.1

Type RM Length L Ch R = 1 ,21396.96,58.06,91.44,98.25
XS GIS Cut Line= 5
     644154.6575    4340152.3326     644056.8445    4340376.8405
     644063.3722    4340403.9011     644097.6077    4340506.6073
644099.396046872 4340580.1491639
#Sta/Elev= 30
       0 1017.22   42.86 1014.24   73.47 1012.84   82.65 1012.32   88.77 1011.75
   91.83 1012.36   94.89 1013.33   97.96 1013.64  101.02 1013.68  104.08 1013.24
  107.14 1012.23   110.2 1011.56  113.26 1011.29  146.93 1009.83  186.73 1008.36
  256.02 1007.39  261.59 1007.02  272.73 1005.57  275.73  1005.4  278.06 1005.63
  284.76 1006.96  290.77 1007.56  311.82 1008.49  359.94 1009.98  402.45 1012.12
  420.84 1012.91  445.36 1014.84  448.42 1015.36  451.49 1016.27  454.55 1016.89
#Mann= 3 , 0 , 0
       0     .09       0  272.73     .04       0  278.06     .09       0
Bank Sta=272.73,278.06
XS Rating Curve= 0 ,0
Exp/Cntr=0.3,0.1

Type RM Length L Ch R = 1 ,21305.52,106.45,91.44,84.84
XS GIS Cut Line= 6
     644127.6479    4340143.5131     644029.3984     4340378.745
     644019.9091    4340379.5076     644013.6971    4340378.3782
     643999.3284    4340374.6439644000.7485913654340592.69228772
#Sta/Elev= 30
       0 1016.92   24.57 1014.91    64.5 1012.24   79.86 1010.95   82.93 1010.89
   89.07 1012.74   92.14  1013.1   98.28 1013.06  101.36 1012.75   107.5 1010.72
  196.57 1007.37   236.5 1006.84  264.45 1003.87  268.42 1003.63  268.65 1003.63
  273.73 1005.03   276.7 1005.44  285.61 1005.33  310.17 1005.81  396.16 1009.67
  439.16 1010.97  460.66 1011.92  472.94 1012.67  479.08 1014.73  482.16 1015.13
   488.3 1014.59  491.37 1013.92  494.44 1013.59  497.51 1014.15  503.65  1016.2
#Mann= 3 , 0 , 0
       0     .09       0  264.45     .04       0  268.65     .09       0
Bank Sta=264.45,268.65
XS Rating Curve= 0 ,0
Exp/Cntr=0.3,0.1

Type RM Length L Ch R = 1 ,21214.08,69.54,91.44,95.86
XS GIS Cut Line= 6
     644085.3145    4340109.1172     643946.4079    4340289.0343
     643961.6769    4340340.0311     643961.9783    4340342.7316
     643968.5723    4340358.4384643965.4589285424340564.03445688
#Sta/Elev= 30
       0 1016.93   15.36 1016.02   49.15 1013.48   52.22 1013.42   92.15 1009.46
   98.29 1009.45  104.44 1010.43  110.58 1010.55  113.65 1010.16  119.79 1009.05
  122.86 1008.87  150.51  1007.8   205.8  1005.2   227.3  1004.4  271.66 1004.32
  274.62 1003.53  277.58 1002.33  279.61 1001.94  283.25  1001.7  286.09 1001.97
  291.77 1003.07  334.04 1004.76  370.87 1006.94  377.01 1007.08  429.18 1009.39
  466.01 1010.41   496.7 1011.86  499.77  1012.2  502.84 1012.77  505.91 1013.57
#Mann= 3 , 0 , 0
       0     .09       0  279.61     .04       0  286.09     .09       0
Bank Sta=279.61,286.09
XS Rating Curve= 0 ,0
Exp/Cntr=0.3,0.1

Type RM Length L Ch R = 1 ,21122.64,50.83,91.44,94.31
XS GIS Cut Line= 6
     644079.3834    4340098.2032     643951.4921    4340175.0982
      643895.642    4340358.6666     643888.3869    4340365.6185
     643885.4005    4340375.2066643880.808762016 4340581.4022126
#Sta/Elev= 30
       0 1017.19   39.59 1013.72   60.91 1012.92   91.36 1010.47  109.64 1009.43
  118.77 1007.94  137.05 1008.05  152.27 1006.83  176.64 1006.34  243.64  1003.9
  258.87 1003.62  292.37 1003.84  301.51 1002.19   307.6 1001.62  353.66 1000.73
   358.6 1000.75  363.99 1001.23  369.58 1002.76  372.37 1003.05  380.76 1005.01
  429.56 1007.33  527.72 1011.03  530.79 1011.18  536.92 1012.43  539.99 1012.65
  546.13 1011.76  549.19 1012.48  552.26 1012.69   558.4 1015.59   567.6 1018.99
#Mann= 3 , 0 , 0
       0     .09       0  353.66     .04       0   358.6     .09       0
Bank Sta=353.66,358.6
XS Rating Curve= 0 ,0
Exp/Cntr=0.3,0.1

Type RM Length L Ch R = 1 ,21031.2 ,89.42,91.44,86.43
XS GIS Cut Line= 6
     644073.8051    4340091.5665      643941.053    4340163.7985
     643889.9942    4340304.3018     643846.8141    4340325.1774
     643802.9968    4340360.3011   643800.4879334340566.22073335
#Sta/Elev= 30
       0 1017.15   30.23 1013.71   72.54 1012.18  105.79 1009.69  123.93 1007.49
  145.09 1007.38  154.18 1005.96  190.79 1005.56  251.81 1003.31  300.62 1002.87
  306.23 1001.14  311.83 1000.14  316.59   999.9  318.56 1000.01  326.35 1000.95
   339.7  1001.5   350.3  1000.8  385.77 1000.92  391.68 1001.44  400.55 1004.05
  403.51 1004.47  452.56 1004.75  471.01 1006.04  569.36 1010.84  578.58 1011.88
   587.8 1011.33  593.95 1012.94  597.02 1013.11  606.24  1016.1  612.39 1018.82
#Mann= 3 , 0 , 0
       0     .09       0  311.83     .04       0  318.56     .09       0
Bank Sta=311.83,318.56
XS Rating Curve= 0 ,0
Exp/Cntr=0.3,0.1

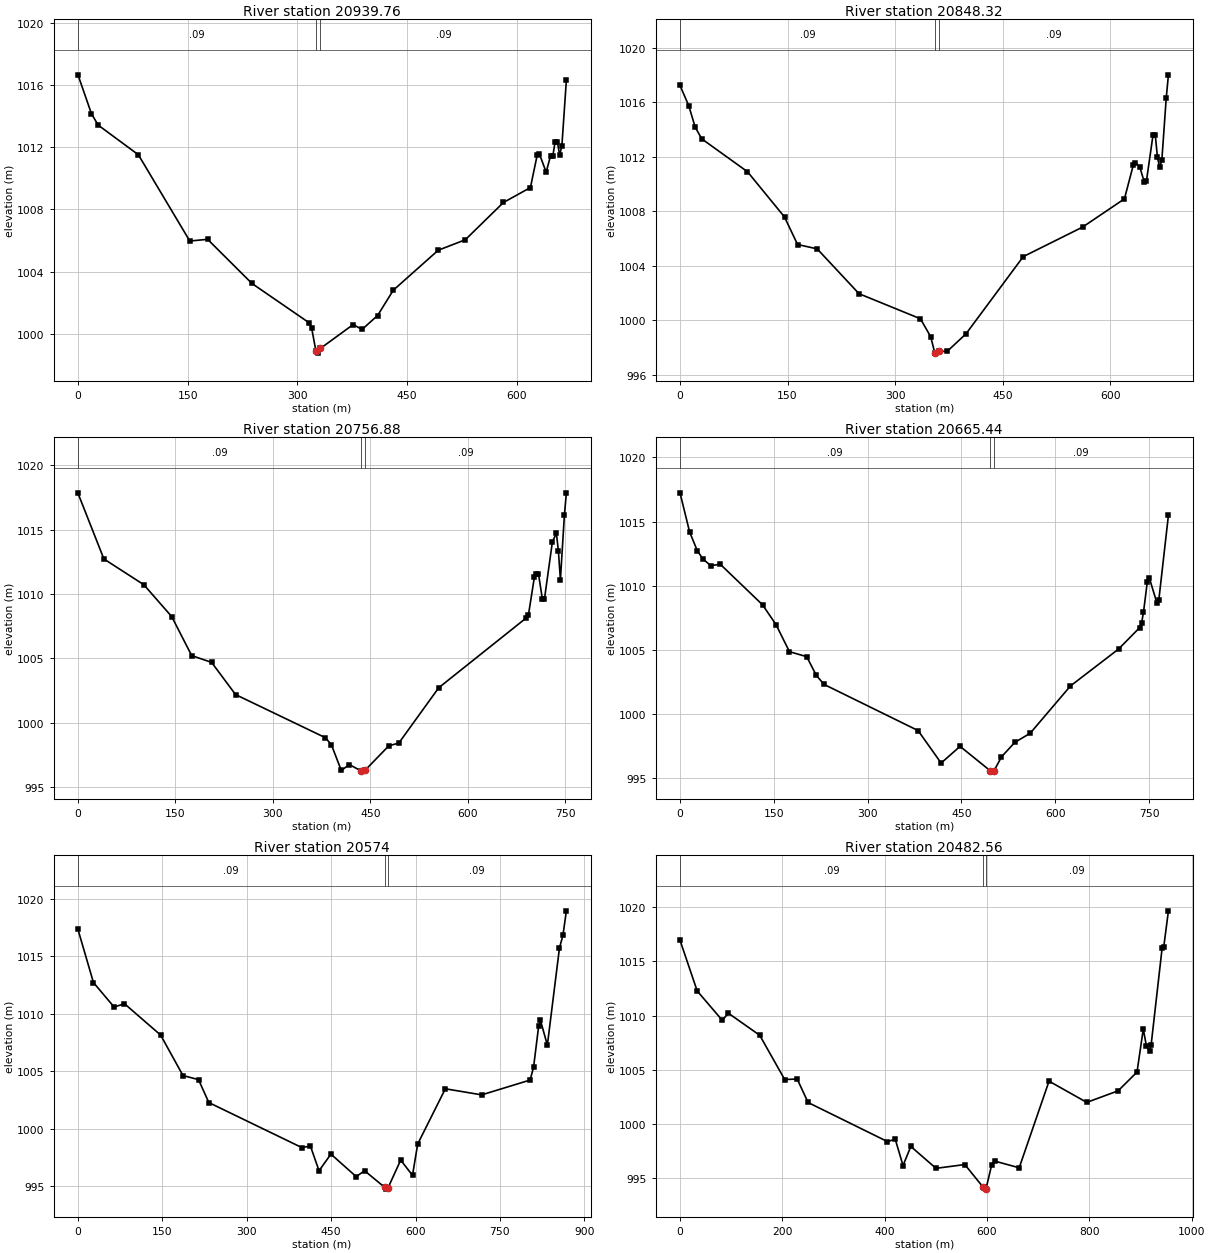
Type RM Length L Ch R = 1 ,20939.76,91.51,91.44,94.08
XS GIS Cut Line= 5
     644068.5134    4340078.3373     643916.7833    4340135.4592
     643856.7758     4340247.867     643755.2588    4340274.2615
643749.6703671284340547.76081795
#Sta/Elev= 30
       0 1016.66   18.35 1014.17   27.53 1013.43   82.59 1011.52  152.95 1005.97
   177.3 1006.08  237.97 1003.24  316.52  1000.7  319.52 1000.39  325.51  998.88
  328.51  998.76  331.51  999.06  376.46  1000.6  388.45 1000.28  409.81 1001.18
  431.32 1002.81  492.79 1005.38  529.68 1006.05  581.93 1008.45  618.81 1009.41
  628.03 1011.49   631.1 1011.57  640.33  1010.4  646.47 1011.47  649.55 1011.47
  652.62 1012.37  655.69 1012.35  658.77 1011.49  661.84  1012.1  667.99 1016.33
#Mann= 3 , 0 , 0
       0     .09       0  325.51     .04       0  331.51     .09       0
Bank Sta=325.51,331.51
XS Rating Curve= 0 ,0
Exp/Cntr=0.3,0.1

Type RM Length L Ch R = 1 ,20848.32,92.9,91.44,90.95
XS GIS Cut Line= 6
     644066.4959    4340070.1793     643886.8293    4340135.7164
      643770.485    4340210.4688     643756.7706    4340228.8617
     643726.0704    4340254.8895643717.3845017944340543.10284399
#Sta/Elev= 30
       0 1017.23   12.14 1015.75   21.25 1014.16   30.36 1013.31   94.11  1010.9
  145.71 1007.58  163.93 1005.56  191.25 1005.24  249.64 1001.95  335.27 1000.11
  349.61  998.79  355.35  997.59   361.1  997.73   372.6  997.72  398.86  999.01
  478.62 1004.67  561.45 1006.84  619.73 1008.91     632 1011.37  635.07 1011.57
   641.2 1011.24  647.34 1010.15   650.4 1010.21  659.61  1013.6  662.68 1013.63
  665.74 1011.97  668.81 1011.23  671.88 1011.73  678.01 1016.31  681.08 1018.01
#Mann= 3 , 0 , 0
       0     .09       0  355.35     .04       0   361.1     .09       0
Bank Sta=355.35,361.1
XS Rating Curve= 0 ,0
Exp/Cntr=0.3,0.1

Type RM Length L Ch R = 1 ,20756.88,90.85,91.44,91.93
XS GIS Cut Line= 4
     644068.0834    4340060.6543     643671.7593    4340201.2145
     643683.7685    4340228.9072 643661.76281794 4340528.8878267
#Sta/Elev= 30
       0 1017.83    39.9 1012.72  101.29 1010.72  144.26 1008.24  174.96 1005.21
  205.65 1004.68  242.48 1002.18  380.61  998.83  389.82  998.29  405.16  996.28
  417.44  996.74   435.6  996.25  438.62  996.23  441.64  996.29  478.32   998.2
  493.66  998.41  555.05 1002.71  690.09 1008.15  693.16 1008.39  702.37 1011.35
  705.44 1011.53   708.5 1011.57  714.64 1009.58  717.71  1009.6  729.99 1014.07
  736.13 1014.71   739.2 1013.32  742.27 1011.11   748.4 1016.12  751.47 1017.86
#Mann= 3 , 0 , 0
       0     .09       0   435.6     .04       0  441.64     .09       0
Bank Sta=435.6,441.64
XS Rating Curve= 0 ,0
Exp/Cntr=0.3,0.1

Type RM Length L Ch R = 1 ,20665.44,86.58,91.44,95.55
XS GIS Cut Line= 5
     644058.7348    4340055.8918     643654.1728    4340200.8225
     643591.2468    4340199.9524     643598.8062    4340235.5884
643576.8570351754340486.38354135
#Sta/Elev= 30
       0 1017.24   15.35 1014.19   27.63 1012.73   36.83 1012.07   49.11 1011.57
   64.46 1011.67  131.99 1008.51  153.48 1006.97  174.97 1004.86  202.59 1004.47
  217.94 1003.01  230.22 1002.31  380.63  998.71  417.46  996.18  447.72  997.48
  495.71  995.59  501.78  995.55  513.92  996.66  535.24  997.79   559.8   998.5
  624.27 1002.19  701.03 1005.06   734.8 1006.73  737.87 1007.07  740.94 1007.92
  747.08  1010.3  750.15 1010.63  762.43 1008.66   765.5 1008.89  780.85  1015.5
#Mann= 3 , 0 , 0
       0     .09       0  495.71     .04       0  501.78     .09       0
Bank Sta=495.71,501.78
XS Rating Curve= 0 ,0
Exp/Cntr=0.3,0.1

Type RM Length L Ch R = 1 ,20574   ,93.65,91.44,88.51
XS GIS Cut Line= 6
     644062.9681    4340045.8376     643654.2434     4340193.714
     643549.4745    4340189.2491     643532.4496    4340198.9777
      643509.484    4340202.5978643488.9305146444340487.67850901
#Sta/Elev= 30
       0 1017.34   27.55 1012.71   64.28 1010.58   82.65 1010.87  146.93 1008.14
  186.72 1004.61  214.27 1004.26  232.63 1002.26  397.92  998.34  413.23  998.47
  428.53  996.32  449.63  997.77  494.58  995.81  509.56  996.32  545.12  994.88
  547.92  994.72  550.81  994.79  573.66  997.25  594.67  995.92  603.89  998.65
  653.07 1003.46  717.61 1002.93  803.67 1004.22  809.81 1005.32  819.04 1008.96
  822.11 1009.42   834.4 1007.26  855.92 1015.73  862.06 1016.82  868.21 1018.96
#Mann= 3 , 0 , 0
       0     .09       0  545.12     .04       0  550.81     .09       0
Bank Sta=545.12,550.81
XS Rating Curve= 0 ,0
Exp/Cntr=0.3,0.1

Type RM Length L Ch R = 1 ,20482.56,84.86,91.44,83.76
XS GIS Cut Line= 6
     644067.2809    4340035.4747     643653.4165    4340190.3185
     643592.0331    4340188.2018     643526.1076    4340142.4996
     643495.4234    4340176.8879643464.1208786374340491.56077372
#Sta/Elev= 30
       0 1016.95   33.59 1012.27   82.46 1009.57   94.68 1010.21  155.76 1008.18
  204.62 1004.09  229.02 1004.14  250.31 1001.97  405.45  998.36  420.65  998.58
  435.86  996.15  451.16  997.91   500.3  995.89  556.66  996.24  592.58  994.14
  597.93  993.97  609.13  996.21  614.97  996.56  662.92  995.94  721.25 1003.94
  794.94 1001.98  856.34 1003.05  893.19 1004.78  905.47 1008.76  911.61 1007.16
  917.75 1006.69  920.82 1007.31  942.31 1016.25  945.38 1016.32  954.59 1019.67
#Mann= 3 , 0 , 0
       0     .09       0  592.58     .04       0  597.93     .09       0
Bank Sta=592.58,597.93
XS Rating Curve= 0 ,0
Exp/Cntr=0.3,0.1

River Reach=UnnamedTrib(Bvr),1
Reach XY= 30
     643942.4532    4339543.7971     643906.3415      4339560.06
      643894.466    4339575.0666     643868.6501    4339652.5737
     643853.8737    4339663.4817 643836.920464774339705.84343058
     643817.4249    4339715.8387     643787.2748    4339715.2474
     643785.6376    4339731.6682     643797.7799    4339758.5703
     643790.8467     4339806.132     643807.1186     4339812.482
     643818.6304    4339848.1688     643809.8967    4339872.0134
      643815.453    4339987.5042     643803.1498     4340013.698
     643714.7128    4340059.0682643710.4816012594340114.23653746
     643694.0489     4340114.529     643672.5777    4340101.0107
     643669.6614    4340144.4298      643658.687    4340150.6202
      643630.112    4340131.5702     643612.6494    4340097.4388
     643600.8696    4340111.6214      643527.718    4340100.6138
     643523.3524    4340111.3295     643532.1734    4340132.4244
     643511.0492    4340125.2201     643504.6267    4340135.3848

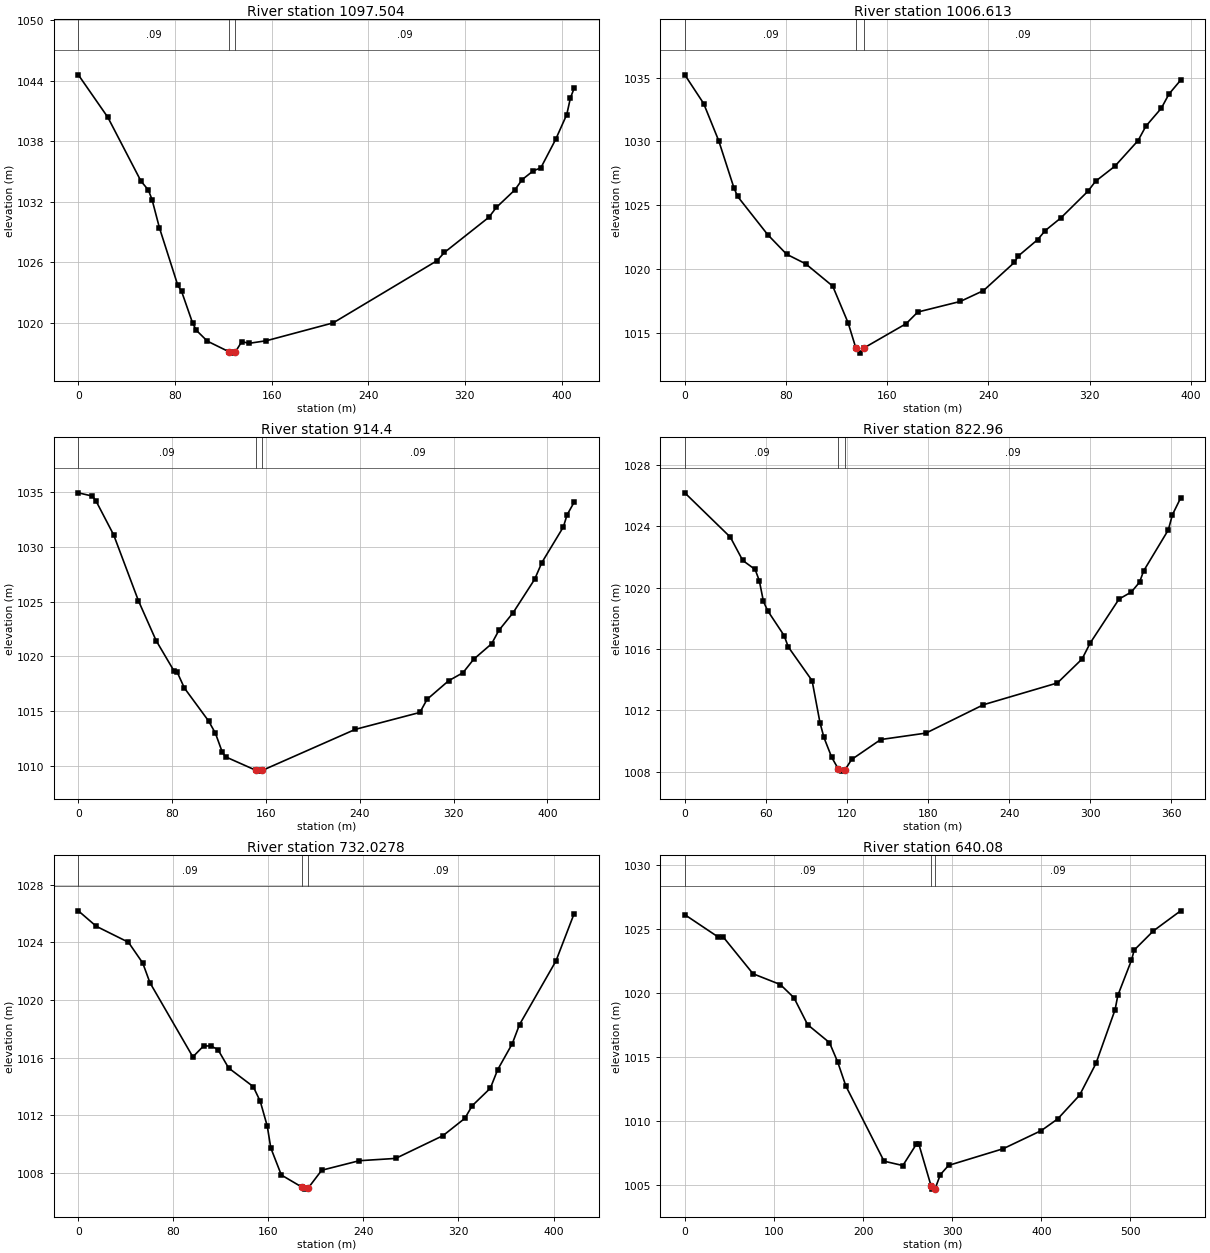
Type RM Length L Ch R = 1 ,1097.504,97.17,90.89,82.38
XS GIS Cut Line= 5
     643869.3104    4339437.8371     643917.0354    4339550.1484
     643920.5667    4339559.9418     643930.7165    4339580.8941
     644149.7693    4339710.8877
#Sta/Elev= 30
       0 1044.57   24.41 1040.36   51.86 1034.03   57.96 1033.15   61.02  1032.2
   67.12 1029.41   82.37 1023.69   85.42 1023.12   94.57 1019.97   97.62 1019.25
  106.78 1018.17  124.63 1017.12  127.24 1016.98  129.84 1017.07  135.35 1018.13
  141.17 1017.95  155.72 1018.21  210.96 1019.98  296.89 1026.14  303.03 1026.96
  339.86 1030.45     346 1031.42  361.34 1033.16  367.48 1034.19  376.68 1035.06
  382.82 1035.34   395.1 1038.16  404.31 1040.63  407.37 1042.29  410.44 1043.24
#Mann= 3 , 0 , 0
       0     .09       0  124.63     .05       0  129.84     .09       0
Bank Sta=124.63,129.84
XS Rating Curve= 0 ,0
Exp/Cntr=0.3,0.1

Type RM Length L Ch R = 1 ,1006.613,87.51,92.21,97.08
XS GIS Cut Line= 3
     643745.4851    4339578.5957     643826.7999    4339615.8231
     644116.9609    4339701.3626
#Sta/Elev= 30
       0 1035.21   14.91 1032.96   26.83 1030.04   38.75 1026.38   41.73 1025.68
   65.58 1022.68   80.49 1021.15   95.54  1020.4  116.93 1018.65  129.15 1015.76
  135.27 1013.78  138.32  1013.4  141.89 1013.82  174.99 1015.71  184.16 1016.62
  217.77 1017.45   236.1  1018.3  260.55 1020.51   263.6 1021.01  278.88 1022.29
  284.99 1023.01  297.21 1023.99   318.6 1026.08  324.71 1026.87  339.99 1028.05
  358.33 1030.06  364.44 1031.18  376.66 1032.59  382.77 1033.71  391.94 1034.79
#Mann= 3 , 0 , 0
       0     .09       0  135.27     .05       0  141.89     .09       0
Bank Sta=135.27,141.89
XS Rating Curve= 0 ,0
Exp/Cntr=0.3,0.1

Type RM Length L Ch R = 1 ,914.4   ,94,91.44,68.53
XS GIS Cut Line= 6
     643725.3768    4339600.8208      643803.861    4339666.7482
     643826.3976    4339703.6936     643833.2006    4339712.2974
     643851.5011    4339732.7564     644083.0942    4339790.2628
#Sta/Elev= 30
       0 1034.89   12.06 1034.59   15.07 1034.15   30.15 1031.06   51.25 1025.07
   66.32 1021.45    81.4 1018.72   84.41 1018.55   90.44 1017.13  111.16 1014.12
  116.93 1013.01   122.7 1011.31  125.58 1010.87  151.74 1009.63     154 1009.57
  156.74 1009.63   236.2 1013.37  291.27 1014.91  297.39  1016.1  315.74 1017.79
  327.98 1018.52  337.16 1019.75  352.46 1021.16  358.57 1022.37  370.81 1023.99
  389.17 1027.03  395.29 1028.55  413.64 1031.79   416.7 1032.87  422.82 1034.04
#Mann= 3 , 0 , 0
       0     .09       0  151.74     .05       0  156.74     .09       0
Bank Sta=151.74,156.74
XS Rating Curve= 0 ,0
Exp/Cntr=0.3,0.1

Type RM Length L Ch R = 1 ,822.96  ,87.45,90.93,84.28
XS GIS Cut Line= 6
     643682.8317    4339742.8494     643760.1034    4339762.1994
     643789.2136    4339760.9141     643802.7634    4339755.2236
       643814.98    4339752.9812     644042.6657    4339792.5912
#Sta/Elev= 30
       0 1026.18    33.7 1023.29   42.89 1021.77   52.08 1021.18   55.15 1020.45
   58.21  1019.1   61.28  1018.5   73.53 1016.87   76.59 1016.13   94.23 1013.93
  100.05  1011.2  102.97 1010.23   108.8 1008.92  113.72 1008.16  116.18 1008.03
  118.64 1008.12   123.5 1008.79  145.05 1010.09   178.5 1010.51  221.07 1012.36
   275.8 1013.78  294.05 1015.34  300.13 1016.39  321.42 1019.25  330.54 1019.71
  336.62 1020.35  339.66 1021.09  357.91 1023.76  360.95 1024.75  367.03 1025.84
#Mann= 3 , 0 , 0
       0     .09       0  113.72     .05       0  118.64     .09       0
Bank Sta=113.72,118.64
XS Rating Curve= 0 ,0
Exp/Cntr=0.3,0.1

Type RM Length L Ch R = 1 ,732.0278,85.61,91.95,94.74
XS GIS Cut Line= 6
     643640.4983    4339784.1245     643752.7116    4339842.5754
      643805.527     4339836.093     643821.3971     4339831.446
     643857.5658    4339813.9832     644038.4324    4339819.0495
#Sta/Elev= 30
       0 1026.19   15.06 1025.12   42.17 1024.01   54.22 1022.57   60.25 1021.21
    96.4 1016.06  105.44 1016.82  111.46 1016.82  117.49 1016.57  126.52 1015.29
  147.22    1014  153.13 1012.98  159.04 1011.26     162 1009.75  170.87 1007.87
     188 1007.04  190.76 1006.89  193.52 1006.97  204.88  1008.2  236.44 1008.86
   267.1 1009.02  306.97  1010.6  325.37  1011.8   331.5 1012.67  346.84 1013.89
  352.97 1015.17  365.24 1016.97  371.37  1018.3  402.04 1022.71  417.37    1026
#Mann= 3 , 0 , 0
       0     .09       0     188     .05       0  193.52     .09       0
Bank Sta=188,193.52
XS Rating Curve= 0 ,0
Exp/Cntr=0.3,0.1

Type RM Length L Ch R = 1 ,640.08  ,81.89,91.44,97.81
XS GIS Cut Line= 4
     643582.2898    4339776.7161     643759.8774    4339917.5334
     643819.7204    4339923.3876     644089.2325    4339915.3581
#Sta/Elev= 30
       0 1026.11   36.75  1024.4   42.88 1024.39   76.57  1021.5   107.2 1020.66
  122.51 1019.63  137.82 1017.53  162.33 1016.13  171.51 1014.63   180.7 1012.75
  223.58 1006.88  244.68 1006.54  259.71 1008.19  262.72 1008.19  276.28 1004.97
  277.75  1004.7  280.76 1004.71  286.77 1005.83  295.96 1006.55  357.24 1007.85
  400.14 1009.27  418.52 1010.18  443.04 1012.03  461.42 1014.51  482.87  1018.7
  485.93 1019.81  501.25 1022.56  504.32 1023.35  525.76 1024.84   556.4 1026.41
#Mann= 3 , 0 , 0
       0     .09       0  276.28     .05       0  280.76     .09       0
Bank Sta=276.28,280.76
XS Rating Curve= 0 ,0
Exp/Cntr=0.3,0.1