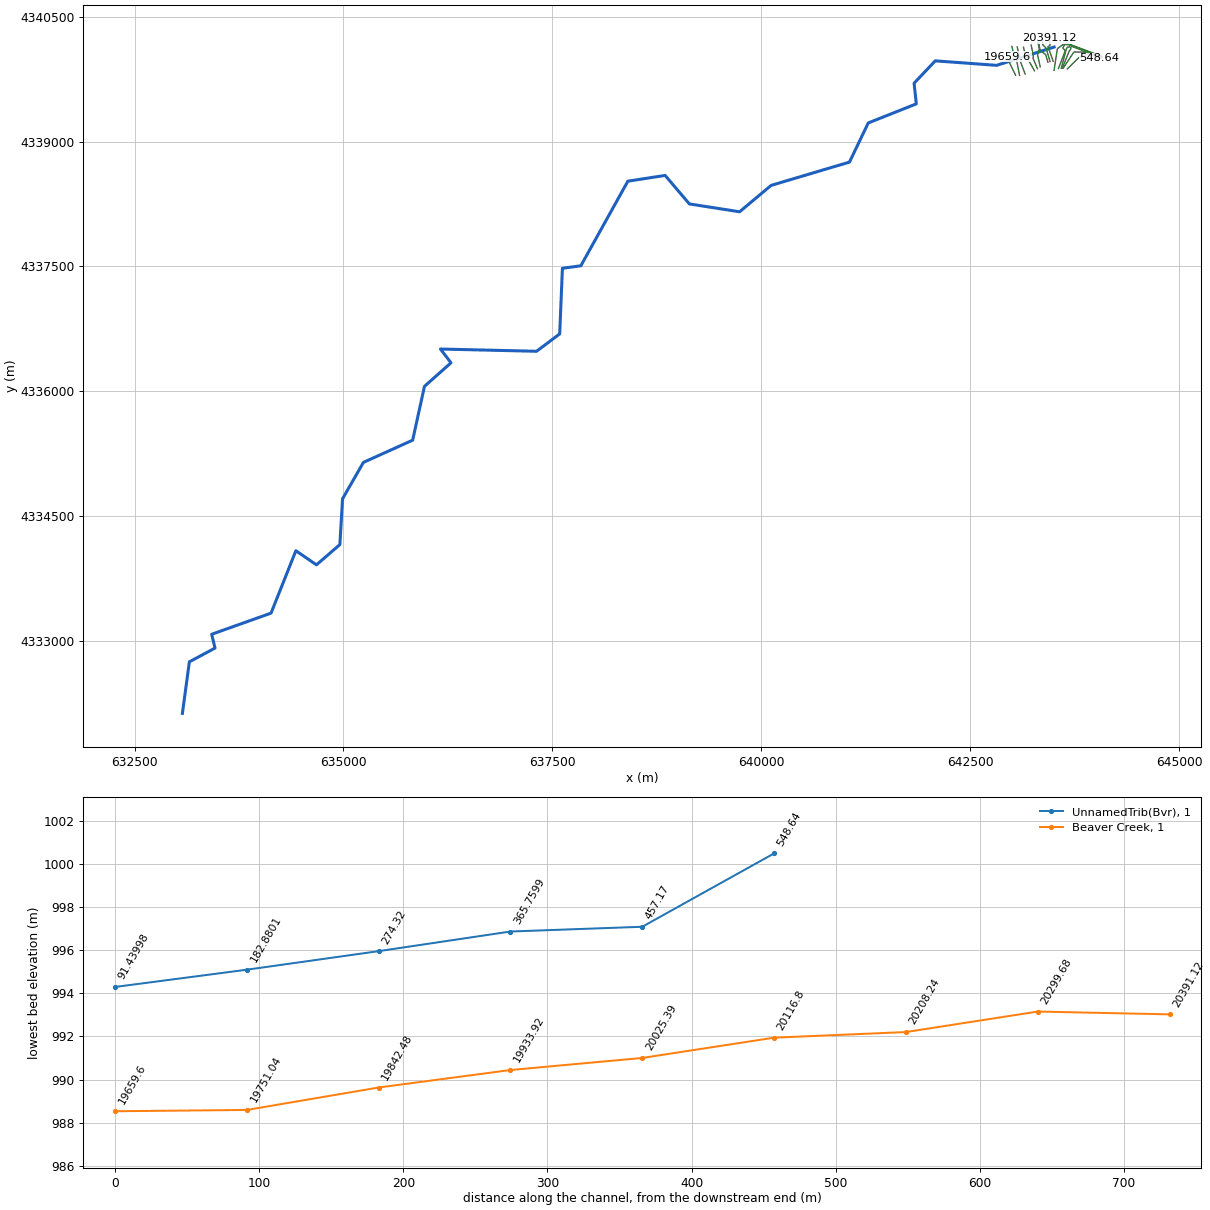
HEC-RAS study BeaverCreek.prj: BeaverCreek

--- BeaverCreek.g01 (geometry) --- (continued)

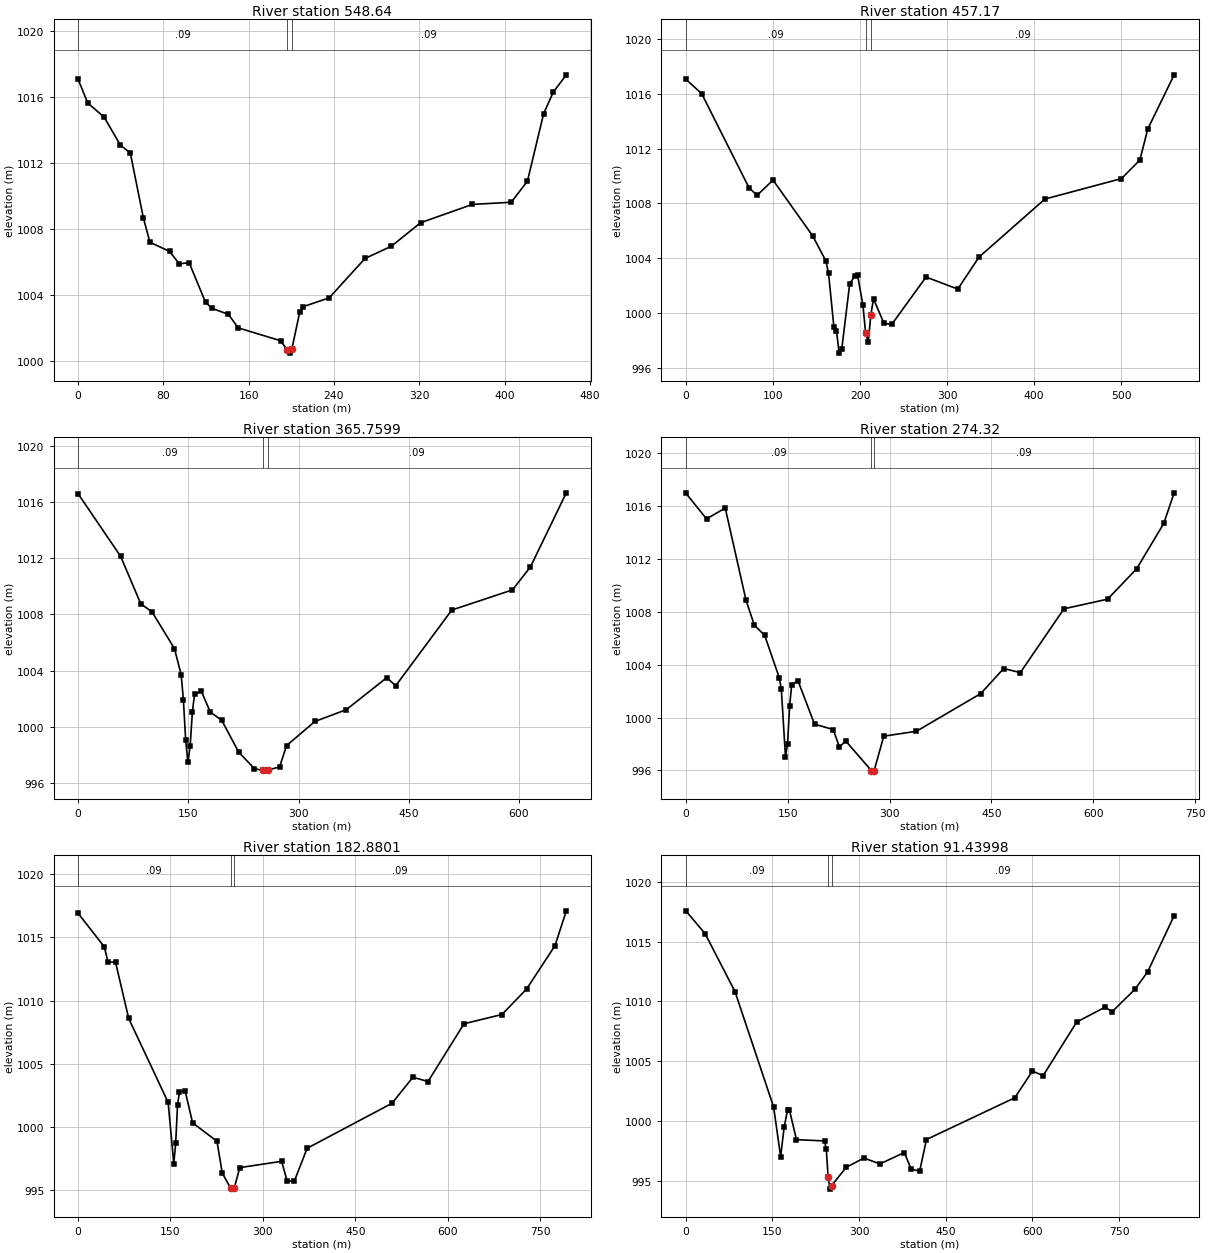
Type RM Length L Ch R = 1 ,548.64  ,85.23,91.47,99.25
XS GIS Cut Line= 5
     643662.6175    4339872.9188     643795.8297    4340004.1888
     643813.1439    4340015.9377     643916.8729    4340053.1841
     644046.7932    4340002.0357
#Sta/Elev= 30
       0 1017.09     9.2 1015.63   24.53 1014.78   39.86 1013.07   49.06 1012.61
   61.32 1008.67   67.45  1007.2   85.85 1006.64   95.04 1005.89  104.24 1005.96
  119.57 1003.56   125.7 1003.19  141.03 1002.83  150.23 1002.01  190.01 1001.23
  195.99 1000.69  198.98 1000.48  200.42  1000.7  207.95 1002.98  211.01 1003.29
   235.5 1003.83  269.18 1006.22  293.67 1006.95   321.2 1008.38  369.76 1009.49
  406.18 1009.62  421.36  1010.9  436.54 1014.99  445.64  1016.3  457.79 1017.34
#Mann= 3 , 0 , 0
       0     .09       0  195.99     .05       0  200.42     .09       0
Bank Sta=195.99,200.42
XS Rating Curve= 0 ,0
Exp/Cntr=0.3,0.1

Type RM Length L Ch R = 1 ,457.17  ,61.31,91.41,77.77
XS GIS Cut Line= 5
     643612.8757    4339881.3855     643733.1171    4340063.8658
     643745.2701    4340076.9245     643884.8617    4340073.7303
     644056.3183    4340005.2107
#Sta/Elev= 30
       0 1017.06   18.21 1016.01   72.84 1009.11   81.95  1008.6  100.16  1009.7
  145.69 1005.63  160.87  1003.8   163.9 1002.89  169.97  999.02  173.01  998.72
  176.04  997.08  179.08  997.38  188.18 1002.15  194.25 1002.72  197.29 1002.75
  203.36 1000.58  206.39  998.57  209.43  997.88  212.46  999.88   215.5 1001.04
  227.45  999.26  236.37  999.17  275.83 1002.63  312.26 1001.75  336.54 1004.08
  412.32 1008.32   500.1 1009.81  521.29 1011.16  530.37 1013.43  560.64 1017.38
#Mann= 3 , 0 , 0
       0     .09       0  206.39     .05       0  212.46     .09       0
Bank Sta=206.39,212.46
XS Rating Curve= 0 ,0
Exp/Cntr=0.3,0.1

Type RM Length L Ch R = 1 ,365.7599,55.01,91.44,41.14
XS GIS Cut Line= 6
     643603.3507    4339884.5605     643683.1891    4340082.7423
      643704.885    4340112.9048     643701.2867    4340129.5207
     643714.3269    4340144.3402      644064.785    4340009.4441
#Sta/Elev= 30
       0 1016.59   57.99 1012.13   85.46 1008.75  100.73 1008.18  131.25 1005.57
   140.4 1003.71  143.46 1001.89  146.51  999.06  149.56  997.48  152.61  998.65
  155.67 1001.09  158.72 1002.36  167.88 1002.53  180.08 1001.05  195.35 1000.49
  218.68  998.21   240.1  997.03  251.21  996.92  253.69  996.86  258.65  996.94
  274.24  997.16  283.82  998.68  322.33 1000.39  365.07 1001.23  420.02  1003.5
  432.24 1002.93  508.56 1008.31  590.99 1009.74  615.42 1011.37  664.27 1016.64
#Mann= 3 , 0 , 0
       0     .09       0  251.21     .05       0  258.65     .09       0
Bank Sta=251.21,258.65
XS Rating Curve= 0 ,0
Exp/Cntr=0.3,0.1

Type RM Length L Ch R = 1 ,274.32  ,37.68,91.44,104.47
XS GIS Cut Line= 6
     643589.5923    4339879.2688     643650.7908    4340112.9405
     643664.7817    4340135.6465     643684.0226    4340134.3189
     643692.7555    4340159.3016     644070.0766    4340014.7358
#Sta/Elev= 30
       0 1016.95   30.58    1015   58.09 1015.82   88.67 1008.86   100.9 1006.98
  116.19  1006.2  137.59 1003.01  140.65 1002.16  146.77  997.05  149.82  997.98
  152.88 1000.85  155.94 1002.46  165.11 1002.79  189.57   999.5  217.09  999.09
  226.26  997.77  235.44  998.23  273.34  995.99  274.15  995.95   277.3  995.98
  291.55  998.59  339.57  998.96  434.46 1001.81  468.13  1003.7  492.62 1003.39
   556.9 1008.21  621.19 1008.94  664.04 1011.24  703.84 1014.66  719.14 1016.97
#Mann= 3 , 0 , 0
       0     .09       0  273.34     .05       0   277.3     .09       0
Bank Sta=273.34,277.3
XS Rating Curve= 0 ,0
Exp/Cntr=0.3,0.1

Type RM Length L Ch R = 1 ,182.8801,95.31,91.44,63.8
XS GIS Cut Line= 6
     643555.7256    4339877.1522     643637.8887    4340090.4398
     643609.0693    4340124.3668     643630.1332    4340164.9184
     643692.0458    4340163.3309       644074.31    4340018.9691
#Sta/Elev= 30
       0 1016.92   42.67 1014.26   48.76 1013.05   60.95 1013.04   82.28 1008.59
  146.28 1001.95  155.42  997.11  158.47   998.7  161.52 1001.75  164.57 1002.77
  173.71 1002.89   185.9 1000.34  225.52  998.87  234.02  996.36  247.57  995.17
  250.26  995.09  253.31  995.14  262.44  996.79  330.38  997.29  339.23  995.73
  351.03  995.73  371.67  998.32  509.43 1001.88  543.23 1003.94  567.81  1003.6
  626.18 1008.17  687.62  1008.9  727.56 1010.91  773.65 1014.34  792.08  1017.1
#Mann= 3 , 0 , 0
       0     .09       0  247.57     .05       0  253.31     .09       0
Bank Sta=247.57,253.31
XS Rating Curve= 0 ,0
Exp/Cntr=0.3,0.1

Type RM Length L Ch R = 1 ,91.43998,62.82,91.44,54.37
XS GIS Cut Line= 6
     643503.8672    4339854.9271     643542.0975    4340107.4461
     643546.2659     4340118.353     643621.1373    4340171.7976
     643688.8708    4340168.6226     644079.6016    4340023.2024
#Sta/Elev= 30
       0 1017.57   33.44 1015.66   85.13 1010.82  152.02 1001.16  164.18  997.01
  170.26  999.48  176.34 1000.95  179.38 1000.92  191.54  998.43  240.19  998.32
  243.23  997.61  246.29  995.33  249.35  994.29  252.42  994.59  277.79  996.12
  308.45  996.89  336.05   996.4  378.27  997.35  390.06  995.97   404.8  995.79
  416.59  998.44   569.4 1001.93  600.06 1004.17  618.45 1003.78   676.7 1008.27
  725.75 1009.51  738.01 1009.13  777.86 1011.03  799.32 1012.46   845.3 1017.16
#Mann= 3 , 0 , 0
       0     .09       0  246.29     .05       0  252.42     .09       0
Bank Sta=246.29,252.42
XS Rating Curve= 0 ,0
Exp/Cntr=0.3,0.1

River Reach=Beaver Creek    ,1
Reach XY= 30
     643504.6267    4340135.3848     642816.7615    4339915.5156
     642082.0651    4339969.8082     641828.6996    4339700.7264
     641855.3696    4339452.7584     641280.0585    4339223.3642
     641055.7443     4338752.987     640117.8474    4338472.9515
     639740.4979    4338155.7684      639139.342    4338250.1822
     638849.3657    4338592.7977      638403.344    4338523.4341
     637840.8916    4337506.9558     637620.2286    4337476.4757
     637587.6848    4336688.2804     637311.1418     4336479.365
     636160.1353    4336506.2894     636287.1356    4336340.9245
     635969.3841    4336057.8829     635828.0963    4335410.9754
     635238.5897    4335143.9471     634988.9421    4334706.4415
     634957.0333    4334155.8954     634676.6802    4333912.6899
     634430.5506    4334082.1721     634133.2615    4333332.3454
     633422.7507    4333078.0763     633463.0158     4332912.593
     633155.8868    4332746.8577       633072.49    4332127.5198

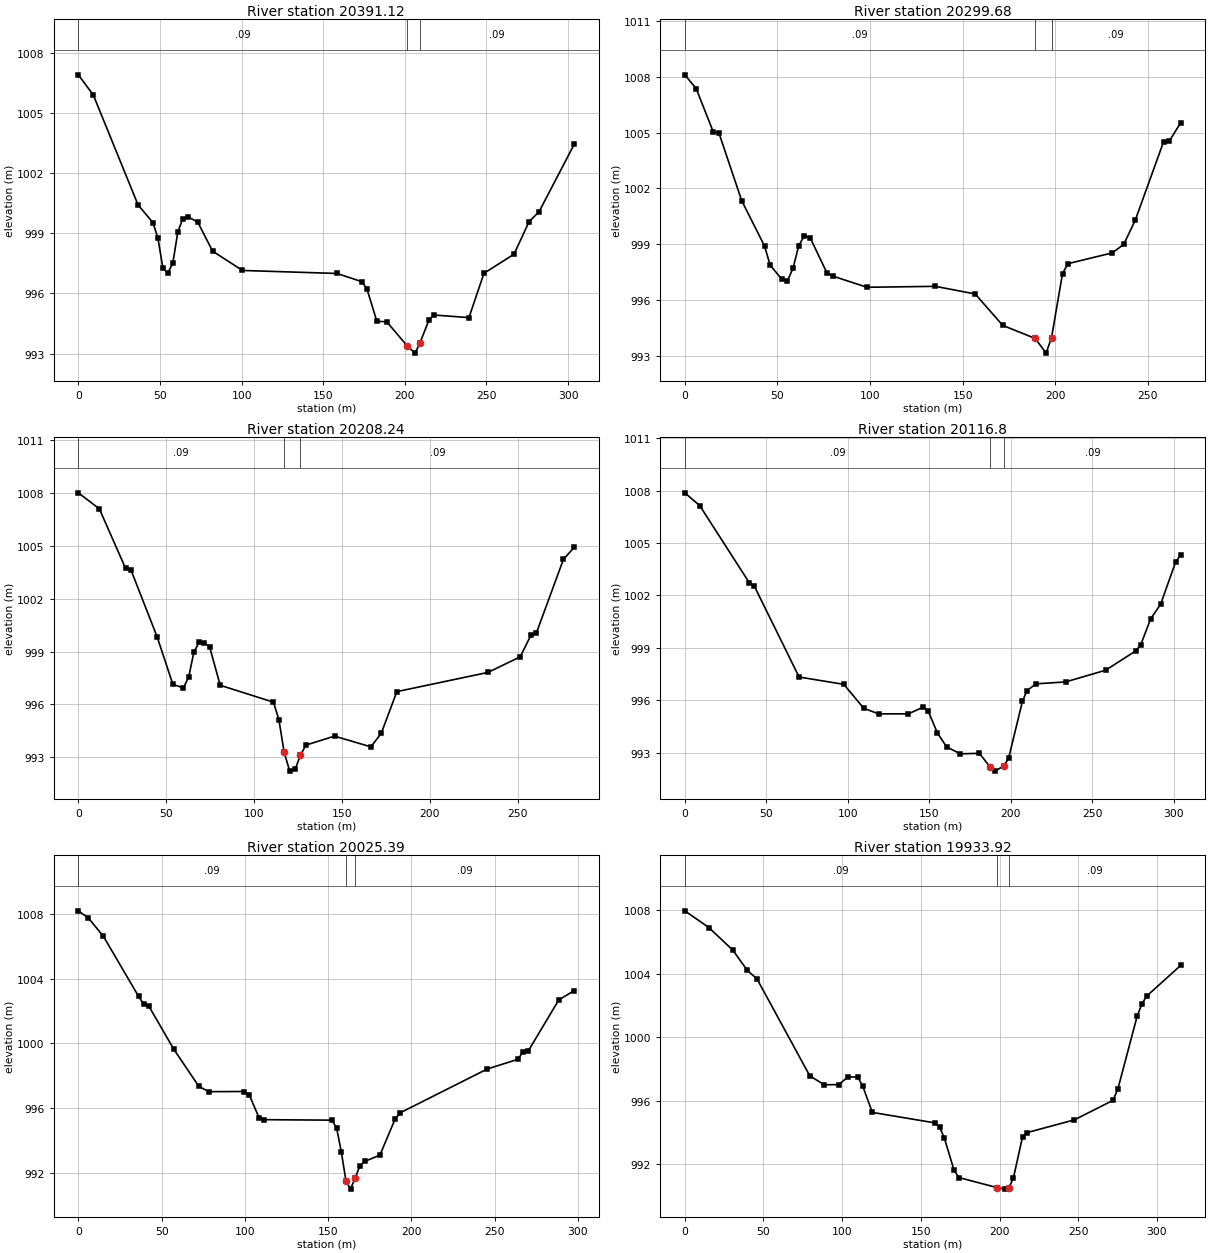
Type RM Length L Ch R = 1 ,20391.12,56.02,91.44,100.78
XS GIS Cut Line= 6
     643493.9012    4339963.6931     643430.5737    4340141.7037
       643442.58    4340145.5871     643446.2584    4340148.5297
     643455.9738    4340154.7212643448.1631081064340240.30296358
#Sta/Elev= 30
       0 1006.89    9.14 1005.89   36.57 1000.41   45.71  999.52   48.76  998.75
   51.81  997.25   54.85  997.01    57.9  997.51   60.95  999.07      64  999.72
   67.04  999.82   73.14  999.55   82.28   998.1  100.56  997.14  158.47  996.99
   173.7  996.58  176.75  996.23  182.84  994.61  188.94  994.58  201.56  993.37
  206.27  993.02  209.15  993.51  214.91  994.69  217.79  994.92  239.27  994.79
  248.48     997  266.89  997.95   276.1  999.57  282.24 1000.07  303.72 1003.42
#Mann= 3 , 0 , 0
       0     .09       0  201.56     .04       0  209.15     .09       0
Bank Sta=201.56,209.15
XS Rating Curve= 0 ,0
Exp/Cntr=0.3,0.1

Type RM Length L Ch R = 1 ,20299.68,81.28,91.44,80.38
XS GIS Cut Line= 5
      643455.316     4339960.915     643410.5981    4340117.5483
     643395.9383    4340135.6285     643370.6446    4340160.4238
643364.3977817674340206.03511998
#Sta/Elev= 30
       0 1008.11    6.15 1007.37   15.37 1005.04   18.44 1004.98   30.73 1001.34
   43.03  998.91    46.1  997.87   52.25  997.14   55.32  997.03    58.4   997.7
   61.47  998.92   64.54  999.46   67.62  999.36   76.84  997.44   79.91  997.29
   98.35  996.69  135.23  996.74  156.74  996.33  171.62  994.64  189.12  993.94
  195.02  993.15  197.97  993.99  203.88  997.43  206.83  997.96   230.8  998.54
  236.94     999  243.08 1000.28  258.42 1004.51  261.49 1004.54  267.63 1005.53
#Mann= 3 , 0 , 0
       0     .09       0  189.12     .04       0  197.97     .09       0
Bank Sta=189.12,197.97
XS Rating Curve= 0 ,0
Exp/Cntr=0.3,0.1

Type RM Length L Ch R = 1 ,20208.24,99.18,91.44,59.58
XS GIS Cut Line= 6
     643430.1806    4339952.9775     643403.4435    4340044.7954
     643371.6168    4340068.9603     643364.4198    4340076.0895
     643333.9398    4340108.2629643319.3779236834340199.08949145
#Sta/Elev= 30
       0 1008.02   11.95 1007.11    26.9 1003.72   29.88 1003.65   44.83  999.83
   53.79  997.13   59.77  996.93   62.76  997.55   65.75  998.97   68.74  999.53
   71.72   999.5   74.71  999.25   80.69  997.08     111  996.12  114.08  995.12
  117.07  993.28  120.22   992.2   123.3   992.3  126.37  993.11  129.44  993.68
  145.72  994.19   166.4  993.58  172.31  994.35  181.18  996.72  232.97  997.81
  251.37   998.7   257.5  999.94  260.57 1000.06   275.9 1004.23  282.03 1004.92
#Mann= 3 , 0 , 0
       0     .09       0  117.07     .04       0  126.37     .09       0
Bank Sta=117.07,126.37
XS Rating Curve= 0 ,0
Exp/Cntr=0.3,0.1

Type RM Length L Ch R = 1 ,20116.8 ,79.55,91.41,86.44
XS GIS Cut Line= 6
     643337.9069    4339897.5251     643306.1814    4340043.5342
     643313.5787    4340067.6665     643315.6241     4340082.648
     643327.2647    4340108.1129643311.1933155464340192.48030903
#Sta/Elev= 30
       0 1007.88    9.15 1007.15   39.64 1002.72   42.69 1002.53   70.13  997.33
   97.58  996.91  109.78  995.54  118.92  995.22  137.22  995.22  146.37  995.61
  149.42  995.36  155.03  994.12  160.63  993.33  169.05  992.93  180.73  992.96
   187.3  992.18  190.33  991.94  195.93  992.25  198.73   992.7  207.13  995.93
  209.93  996.55  215.53  996.94  233.67  997.05  258.21  997.72  276.61  998.82
  279.68  999.16  285.82 1000.66  291.95  1001.5  301.16 1003.92  304.22 1004.32
#Mann= 3 , 0 , 0
       0     .09       0   187.3     .04       0  195.93     .09       0
Bank Sta=187.3,195.93
XS Rating Curve= 0 ,0
Exp/Cntr=0.3,0.1

Type RM Length L Ch R = 1 ,20025.39,81.38,91.47,92.07
XS GIS Cut Line= 5
      643304.834    4339875.1678     643252.1407    4340000.3009
     643255.7588    4340027.7523     643255.6985    4340036.1995
643229.6778898064340159.33845595
#Sta/Elev= 30
       0 1008.19    6.03 1007.75   15.09 1006.61   36.21  1002.9   39.22 1002.43
   42.24 1002.32   57.33  999.64   72.41  997.34   78.45  997.02   99.57  997.03
  102.59  996.83  108.62  995.39  111.64  995.29  152.39  995.26  155.16  994.75
  157.93  993.31   160.7  991.52  163.46     991  166.28   991.7   169.1  992.44
  171.91  992.71  181.12   993.1  190.33  995.35   193.4  995.72  245.59  998.42
  264.01  999.02  267.07  999.48  270.14  999.52  288.56 1002.69  297.77 1003.26
#Mann= 3 , 0 , 0
       0     .09       0   160.7     .04       0  166.28     .09       0
Bank Sta=160.7,166.28
XS Rating Curve= 0 ,0
Exp/Cntr=0.3,0.1

Type RM Length L Ch R = 1 ,19933.92,92.86,91.44,86.48
XS GIS Cut Line= 5
     643268.8505    4339849.7677     643172.0397    4340026.7009
     643168.7711    4340029.3799     643156.5159    4340049.1298
643138.2346447174340133.09693958
#Sta/Elev= 30
       0 1007.96   15.28 1006.91   30.56 1005.48   39.73 1004.21   45.84 1003.68
   79.45  997.57   88.62  997.01   97.79  997.02   103.9  997.52  110.01  997.48
  113.07  996.92  119.18  995.27  158.91  994.61  161.96  994.34  165.02  993.63
  171.13  991.62  174.18  991.17  198.63  990.53   203.8  990.44  205.91  990.51
  208.82  991.14  214.63  993.73  217.54     994  247.57   994.8  272.13  996.03
  275.19  996.74  287.47 1001.33  290.54 1002.11  293.61  1002.6  315.09 1004.52
#Mann= 3 , 0 , 0
       0     .09       0  198.63     .04       0  205.91     .09       0
Bank Sta=198.63,205.91
XS Rating Curve= 0 ,0
Exp/Cntr=0.3,0.1

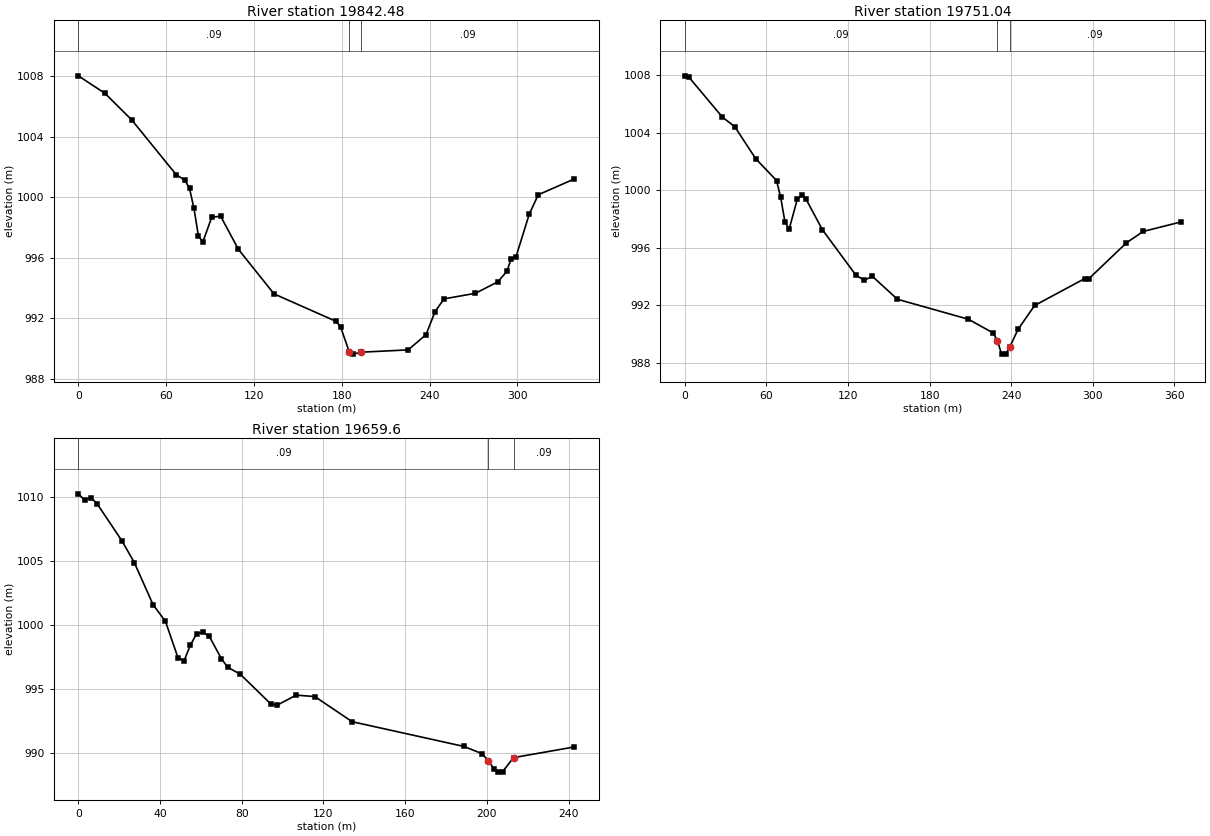
Type RM Length L Ch R = 1 ,19842.48,97.63,91.44,91.69
XS GIS Cut Line= 5
     643156.9316     4339812.726     643093.0517    4339983.5532
     643091.3833    4339994.4714     643090.0694    4340017.1958
643063.1022375024340136.86668015
#Sta/Elev= 30
       0 1008.02   18.24 1006.86   36.48 1005.11   66.87 1001.49   72.95 1001.11
   75.99 1000.58   79.03  999.26   82.07  997.44   85.11  997.05   91.19  998.68
   97.27  998.74  109.43  996.55  133.75  993.61   176.3  991.79  179.34   991.4
  185.14  989.78   187.9  989.63  193.43  989.76  225.39  989.91  237.65  990.92
  243.79  992.44  249.92  993.28  271.39  993.65  286.72  994.41  292.86   995.1
  295.92  995.94  298.99  996.02  308.19  998.89  314.32 1000.16  338.86  1001.2
#Mann= 3 , 0 , 0
       0     .09       0  185.14     .04       0  193.43     .09       0
Bank Sta=185.14,193.43
XS Rating Curve= 0 ,0
Exp/Cntr=0.3,0.1

Type RM Length L Ch R = 1 ,19751.04,93.06,91.44,87.94
XS GIS Cut Line= 4
     643090.7856    4339794.2051     643049.7416    4340004.8818
     643025.2078    4340031.9108642999.255488085  4340142.355735
#Sta/Elev= 30
       0 1007.97    3.07 1007.87    27.6  1005.1    36.8 1004.42   52.13  1002.2
   67.46 1000.68   70.52   999.5   73.59  997.82   76.66  997.27   82.79   999.4
   85.86  999.64   88.92  999.42  101.19  997.25  125.72   994.1  131.85  993.74
  137.98     994  156.38  992.41  208.51  991.02  226.81  990.06  229.85  989.53
  232.89  988.61  235.93  988.59  238.97  989.09  245.06  990.32  257.27  991.98
  294.07  993.85  297.13  993.84  324.73  996.34  336.99  997.13  364.59  997.79
#Mann= 3 , 0 , 0
       0     .09       0  229.85     .04       0  238.97     .09       0
Bank Sta=229.85,238.97
XS Rating Curve= 0 ,0
Exp/Cntr=0.3,0.1

Type RM Length L Ch R = 1 ,19659.6 ,93.49,93.83,100.15
XS GIS Cut Line= 6
     643043.1605    4339797.5124     642961.9039    4339964.6759
     642954.5198    4339985.2005     642954.1016    4339987.8301
     642954.3862    4339998.7208642949.7896123814340019.73460279
#Sta/Elev= 30
       0 1010.22    3.05 1009.73    6.09 1009.93    9.14 1009.46   21.33 1006.56
   27.42 1004.86   36.56 1001.59   42.66 1000.28   48.75  997.46    51.8  997.22
   54.85  998.42   57.89  999.32   60.94  999.42   63.99  999.15   70.08  997.36
   73.13   996.7   79.22  996.17   94.46  993.81    97.5  993.76  106.64  994.53
  115.79  994.42  134.07  992.46  188.84  990.53  197.75  989.96  200.73  989.42
   203.7  988.74  205.69  988.53  207.69  988.56  213.08  989.66  242.76  990.49
#Mann= 3 , 0 , 0
       0     .09       0  200.73     .04       0  213.08     .09       0
Bank Sta=200.73,213.08
XS Rating Curve= 0 ,0
Exp/Cntr=0.3,0.1