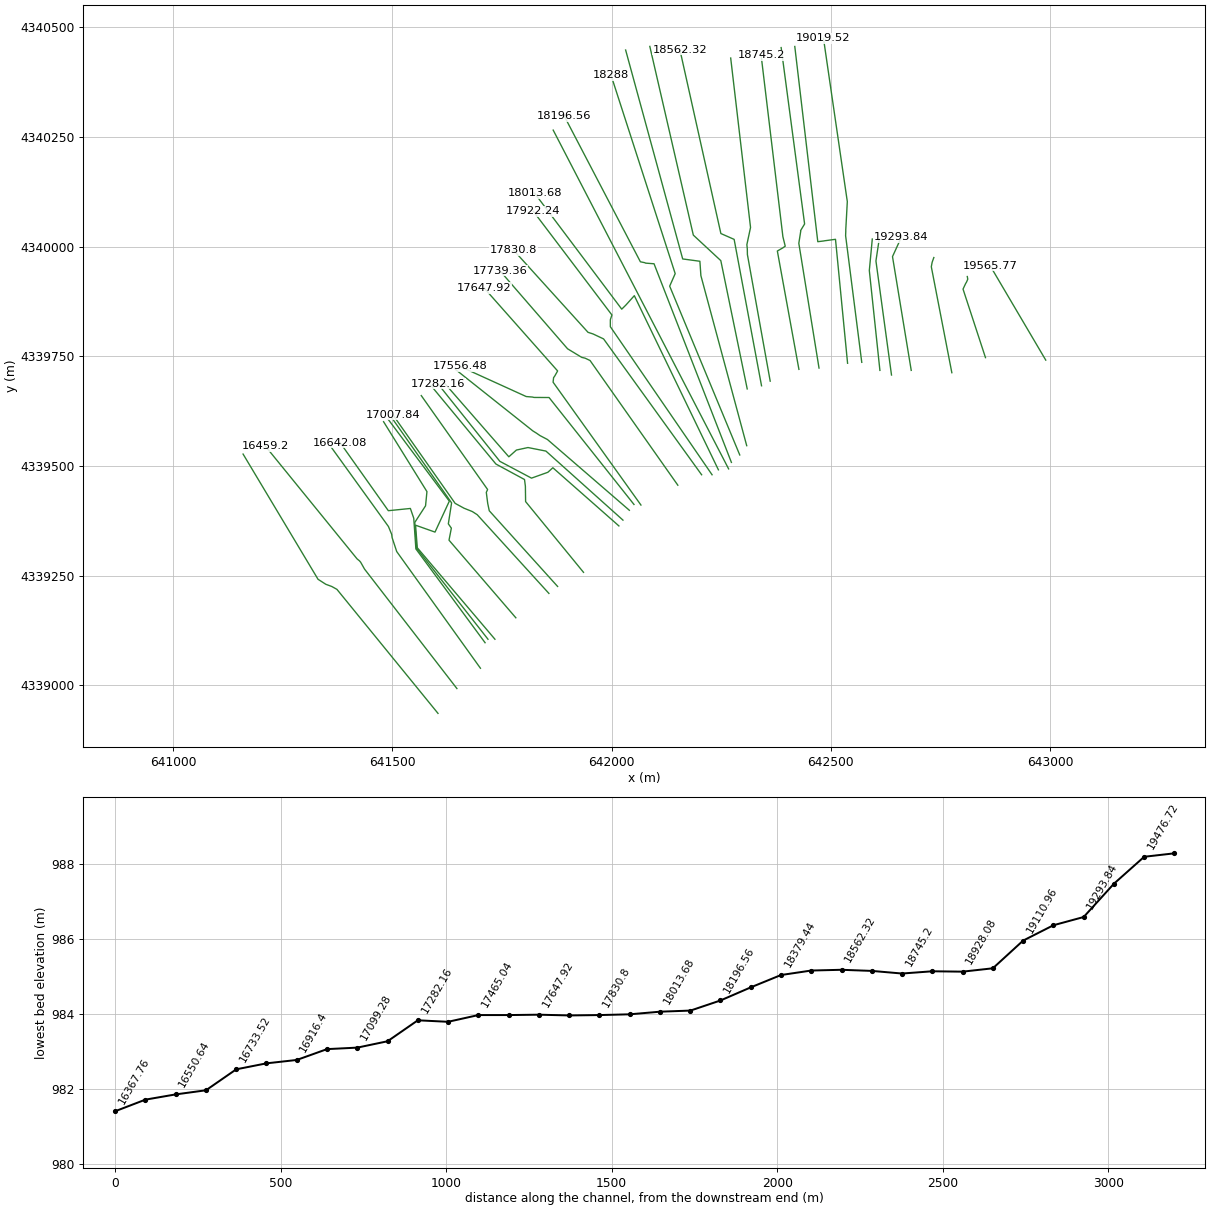
HEC-RAS study BeaverCreek.prj: BeaverCreek

--- BeaverCreek.g01 (geometry) --- (continued)

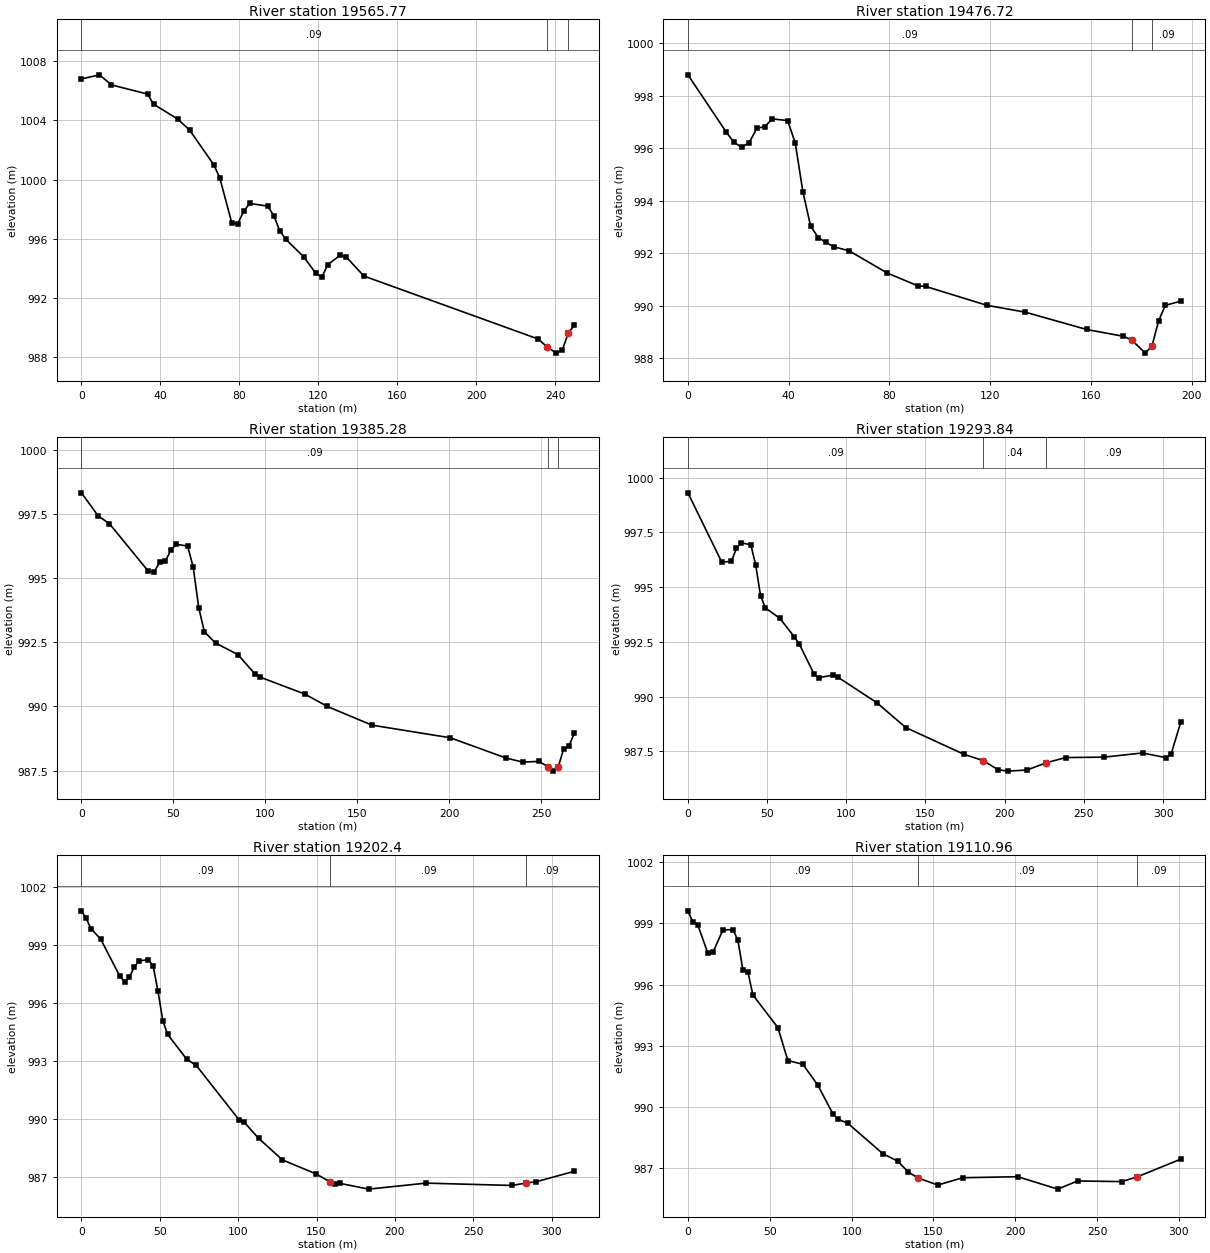
Type RM Length L Ch R = 1 ,19565.77,97.83,89.05,86.76
XS GIS Cut Line= 2
     642990.2437    4339741.2883642863.5361805664339956.26416226
#Sta/Elev= 30
       0 1006.79    9.13 1007.07   15.22 1006.39   33.48 1005.77   36.52 1005.09
   48.69 1004.09   54.78 1003.34   66.95 1001.01   69.99 1000.14   76.08   997.1
   79.12  997.02   82.17  997.87   85.21  998.39   94.34  998.21   97.38  997.57
  100.43  996.54  103.47  995.97   112.6  994.78  118.69  993.67  121.73  993.42
  124.77  994.27  130.86  994.88   133.9   994.8  143.03  993.49  231.29  989.24
  235.57  988.73  240.41  988.29  243.46   988.5   246.5  989.64  249.54  990.18
#Mann= 3 , 0 , 0
       0     .09       0  235.57     .04       0   246.5     .09       0
Bank Sta=235.57,246.5
XS Rating Curve= 0 ,0
Exp/Cntr=0.3,0.1

Type RM Length L Ch R = 1 ,19476.72,90.71,91.44,92.7
XS GIS Cut Line= 6
     642852.7924    4339746.9769     642801.6124    4339903.1998
     642807.5893    4339916.0775     642809.2663    4339918.5599
     642812.4074    4339925.8482642811.310510245 4339931.8782472
#Sta/Elev= 29
       0   998.8   15.22  996.62   18.27  996.23   21.31  996.04   24.35  996.22
    27.4  996.77   30.44  996.82   33.49  997.12   39.58  997.06   42.62   996.2
   45.66  994.34   48.71  993.04   51.75   992.6    54.8  992.42   57.84  992.25
   63.93   992.1   79.15  991.25   91.33  990.76   94.37  990.74  118.73  990.02
  133.95  989.76   158.3   989.1  172.91  988.84  176.14   988.7  181.59   988.2
  184.23  988.48  186.88  989.44  189.52  990.02  195.65  990.18
#Mann= 3 , 0 , 0
       0     .09       0  176.14     .04       0  184.23     .09       0
Bank Sta=176.14,184.23
XS Rating Curve= 0 ,0
Exp/Cntr=0.3,0.1

Type RM Length L Ch R = 1 ,19385.28,95.33,91.44,90.56
XS GIS Cut Line= 4
     642776.0631     4339712.581     642729.2672    4339954.1556
      642731.106    4339964.2369642735.0152691774339975.22008959
#Sta/Elev= 30
       0  998.32    9.11  997.42   15.19  997.12   36.45  995.26   39.49  995.23
   42.53  995.62   45.57  995.65   48.61  996.09   51.64  996.31   57.72  996.25
   60.76  995.43   63.79  993.84   66.83  992.91   72.91  992.47   85.06  992.02
   94.17  991.28   97.21  991.14  121.51  990.48  133.67     990  157.97  989.27
   200.5  988.78  230.88  987.99  239.99  987.83  248.63  987.86  253.75  987.65
  256.31  987.48  259.23  987.64  262.14  988.34  265.06  988.46  267.97  988.96
#Mann= 3 , 0 , 0
       0     .09       0  253.75     .04       0  259.23     .09       0
Bank Sta=253.75,259.23
XS Rating Curve= 0 ,0
Exp/Cntr=0.3,0.1

Type RM Length L Ch R = 1 ,19293.84,104.6,91.44,89.66
XS GIS Cut Line= 3
     642683.4588    4339717.8727     642640.7478    4339977.3491
642660.7980929934340021.24278764
#Sta/Elev= 30
       0  999.31    21.4  996.14   27.52  996.18   30.58  996.77   33.64  997.03
   39.75  996.93   42.81  996.01   45.87  994.61   48.92  994.05    58.1  993.57
   67.27  992.72   70.33   992.4    79.5  991.05   82.56  990.86   91.73  990.98
   94.79  990.88  119.25  989.72   137.6  988.58  174.29  987.36  186.52  987.07
   195.7  986.66  201.81  986.59  214.04  986.64  226.27  986.97  238.51  987.21
  262.97  987.23  287.09  987.42  302.17   987.2  305.19  987.39  311.22  988.83
#Mann= 3 ,-1 , 0
       0     .09       0  186.52     .04       0  226.27     .09       0
Bank Sta=186.52,226.27
XS Rating Curve= 0 ,0
Exp/Cntr=0.3,0.1

Type RM Length L Ch R = 1 ,19202.4 ,87.99,91.44,103.14
XS GIS Cut Line= 3
     642638.4795    4339707.2893     642602.9746    4339967.4477
642610.6905233414340018.73771093
#Sta/Elev= 30
       0 1000.75    3.05 1000.36    6.11  999.82   12.21   999.3   24.43  997.38
   27.48  997.09   30.53  997.32   33.58  997.83   36.64  998.16   42.74  998.23
    45.8  997.88   48.85  996.59    51.9  995.08   54.96  994.37   67.17  993.08
   73.28  992.76  100.75  989.93  103.81  989.83  112.97     989  128.23  987.88
   149.6  987.16  158.76  986.74  161.82  986.61  164.87  986.67  183.19  986.37
  219.83  986.68  274.78  986.56  283.93  986.69  290.03  986.75  314.44  987.29
#Mann= 3 , 0 , 0
       0     .09       0  158.76     .09       0  283.93     .09       0
Bank Sta=158.76,283.93
XS Rating Curve= 0 ,0
Exp/Cntr=0.3,0.1

Type RM Length L Ch R = 1 ,19110.96,95.41,91.44,89.94
XS GIS Cut Line= 3
     642612.0211    4339717.8727     642587.8898    4339945.6115
642594.6575010124340017.39429965
#Sta/Elev= 30
       0  999.62    3.05  999.07    6.11  998.91   12.21  997.54   15.27  997.58
   21.37  998.68   27.48   998.7   30.54  998.18   33.59  996.73   36.64  996.63
    39.7  995.49   54.96  993.89   61.07  992.27   70.23  992.09   79.39  991.06
   88.55  989.66   91.61   989.4   97.71  989.19  119.09   987.7  128.25  987.33
  134.35  986.82  140.46  986.51  152.68  986.16  167.94  986.52  201.53  986.57
  225.96  985.96  238.03  986.36  265.06  986.33  274.07  986.55  301.11  987.43
#Mann= 3 , 0 , 0
       0     .09       0  140.46     .09       0  274.07     .09       0
Bank Sta=140.46,274.07
XS Rating Curve= 0 ,0
Exp/Cntr=0.3,0.1

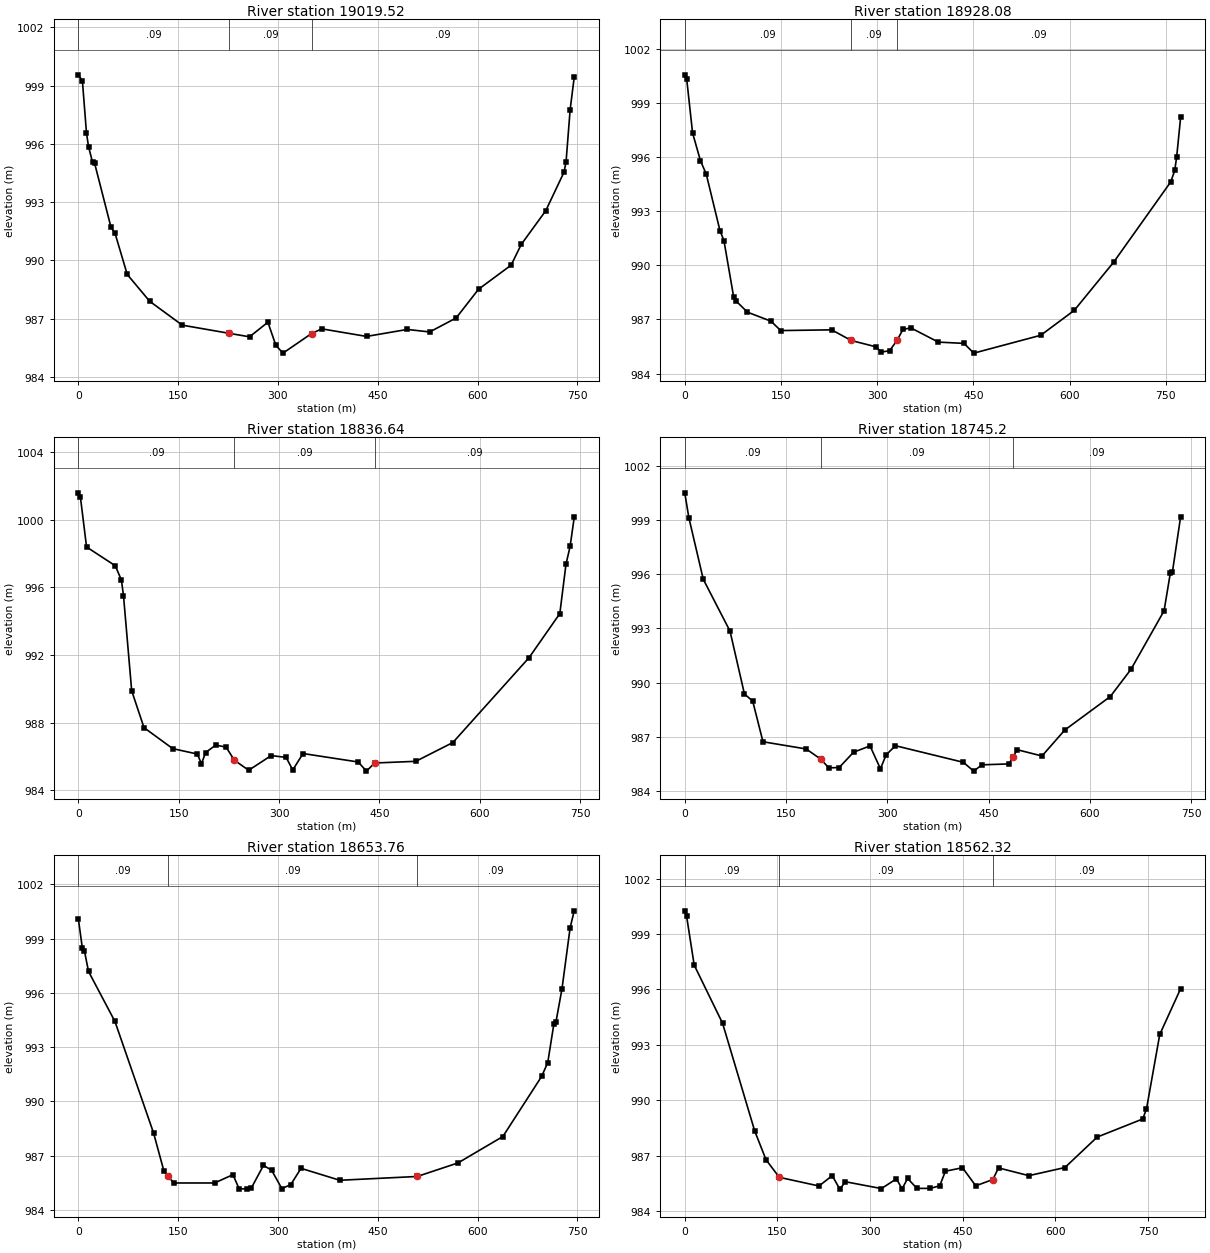
Type RM Length L Ch R = 1 ,19019.52,82.47,91.44,101.2
XS GIS Cut Line= 6
     642570.6456    4339736.2479     642533.8419    4340024.9089
     642534.2306    4340036.6533     642534.1684    4340038.3979
     642537.7034    4340102.7382642483.3303720294340475.10095943
#Sta/Elev= 30
       0  999.55    6.13  999.23   12.25  996.55   15.32  995.85   21.44  995.04
   24.51  994.99   49.01  991.71   55.14  991.39   73.52  989.27  107.21  987.89
  156.22  986.66  226.67  986.24   257.3  986.06  284.87  986.81  296.87  985.62
  307.56  985.22  350.52  986.23  365.86  986.47  433.18  986.08  494.37  986.44
  528.02  986.31  567.79  987.03  601.45  988.51   650.4  989.75   665.7  990.82
  702.41  992.55  729.94  994.54     733  995.08  739.12  997.76  745.24  999.43
#Mann= 3 , 0 , 0
       0     .09       0  226.67     .09       0  350.52     .09       0
Bank Sta=226.67,350.52
XS Rating Curve= 0 ,0
Exp/Cntr=0.3,0.1

Type RM Length L Ch R = 1 ,18928.08,104.8,91.44,81.29
XS GIS Cut Line= 6
     642538.2958    4339734.1185     642510.7671    4340016.7826
     642485.7978    4340013.4083     642484.1137    4340013.0606
     642470.3727    4340011.3238642417.9232434664340456.51773018
#Sta/Elev= 30
       0 1000.55    3.05 1000.32   12.22  997.33   24.43   995.8   33.59  995.04
   54.97  991.91   61.08  991.37   76.34  988.23    79.4  988.04   97.72   987.4
  134.37   986.9  149.64  986.38  229.03  986.42  259.57  985.83     298  985.48
   306.4  985.19  319.23  985.26  330.91  985.83  340.12  986.44   352.4  986.53
  395.39  985.74   435.3  985.67  450.65  985.13  555.05  986.12  607.24   987.5
  668.65  990.17  757.69  994.62  763.83  995.25   766.9  996.01  773.04  998.19
#Mann= 3 , 0 , 0
       0     .09       0  259.57     .09       0  330.91     .09       0
Bank Sta=259.57,330.91
XS Rating Curve= 0 ,0
Exp/Cntr=0.3,0.1

Type RM Length L Ch R = 1 ,18836.64,93.02,91.44,91.3
XS GIS Cut Line= 6
     642473.1751    4339723.1779     642427.1209    4340007.7379
       642431.47     4340035.184     642431.1149    4340036.5506
     642440.3027    4340051.7718642386.7998309314340454.01025301
#Sta/Elev= 30
       0 1001.59    3.07 1001.35   12.27  998.39    55.2  997.28    64.4  996.43
   67.47  995.52   79.73  989.89   98.13  987.71  141.06  986.47  177.86  986.15
     184  985.57  190.13  986.24  205.46  986.68   220.8  986.56  233.06  985.79
  254.53  985.19  288.26  986.06  310.49  985.95  320.43  985.21  335.78  986.18
  418.24  985.68  430.54  985.14  442.84  985.62  504.32  985.72  559.66  986.83
   673.4  991.84  719.51  994.45  728.73  997.37  734.88  998.42  741.03 1000.14
#Mann= 3 , 0 , 0
       0     .09       0  233.06     .09       0  442.84     .09       0
Bank Sta=233.06,442.84
XS Rating Curve= 0 ,0
Exp/Cntr=0.3,0.1

Type RM Length L Ch R = 1 ,18745.2 ,87.56,91.44,95.9
XS GIS Cut Line= 6
     642427.3375    4339720.1888     642378.1571    4339990.0547
     642391.4648    4339997.7817     642396.1166    4340001.1769
     642390.8249    4340022.5552642341.1602161274340436.18668154
#Sta/Elev= 30
       0 1000.53     6.1  999.15   27.43  995.73   67.05  992.85   88.39  989.36
  100.58  988.97  115.82  986.71  179.83  986.31  201.16  985.75  213.35  985.26
  228.59  985.28  249.93  986.13  274.31  986.48   289.7  985.21  298.21  985.99
  311.98  986.49  412.44  985.57  427.76  985.08  440.01  985.43  479.83  985.48
  485.96  985.86  492.09  986.27  528.85  985.92  562.54  987.36  629.93  989.22
  660.56  990.73  709.58  993.98  718.77  996.06  721.83  996.11  734.08   999.2
#Mann= 3 , 0 , 0
       0     .09       0  201.16     .09       0  485.96     .09       0
Bank Sta=201.16,485.96
XS Rating Curve= 0 ,0
Exp/Cntr=0.3,0.1

Type RM Length L Ch R = 1 ,18653.76,87.96,91.44,96.09
XS GIS Cut Line= 6
     642361.8618    4339693.2972     642309.8446     4339982.064
     642309.6465    4339994.4427     642308.6418    4340004.7409
     642317.0148    4340043.8046642271.7497078024340430.16649359
#Sta/Elev= 30
       0  1000.1    6.11  998.46    9.17  998.32   15.28  997.19   55.02  994.42
  113.09  988.25  128.37  986.18  134.48  985.86  143.65  985.49  204.78  985.49
  232.29  985.95  241.46  985.18  253.68  985.15  259.79   985.2  278.13  986.46
  290.36   986.2  305.79  985.18  319.22   985.4  334.58   986.3  392.85  985.64
  509.25  985.85  570.51   986.6   637.9  988.06  696.09  991.38  705.28  992.14
  714.47  994.27  717.54  994.37  726.73  996.23  738.98  999.61   745.1 1000.54
#Mann= 3 , 0 , 0
       0     .09       0  134.48     .09       0  509.25     .09       0
Bank Sta=134.48,509.25
XS Rating Curve= 0 ,0
Exp/Cntr=0.3,0.1

Type RM Length L Ch R = 1 ,18562.32,90.36,91.44,105.63
XS GIS Cut Line= 4
     642342.0921    4339682.7508      642279.609     4340016.631
     642249.3673     4340029.945 642155.844968234340449.42993724
#Sta/Elev= 30
       0 1000.26    3.06  999.96    15.3  997.32    61.2  994.17  113.23  988.33
  131.59  986.77  153.01  985.82  217.27  985.35  238.69  985.91  250.93  985.18
  260.11  985.58  318.26  985.21  342.68  985.74  351.69  985.19   360.7  985.76
  375.79  985.22  397.28  985.22  412.63  985.36  421.84  986.15  449.47  986.34
  470.95  985.36  498.58   985.7  507.79  986.33  556.91  985.91  615.24  986.35
  667.43     988   741.1  988.98  747.24  989.52  768.73  993.56   802.5  996.04
#Mann= 3 , 0 , 0
       0     .09       0  153.01     .09       0  498.58     .09       0
Bank Sta=153.01,498.58
XS Rating Curve= 0 ,0
Exp/Cntr=0.3,0.1

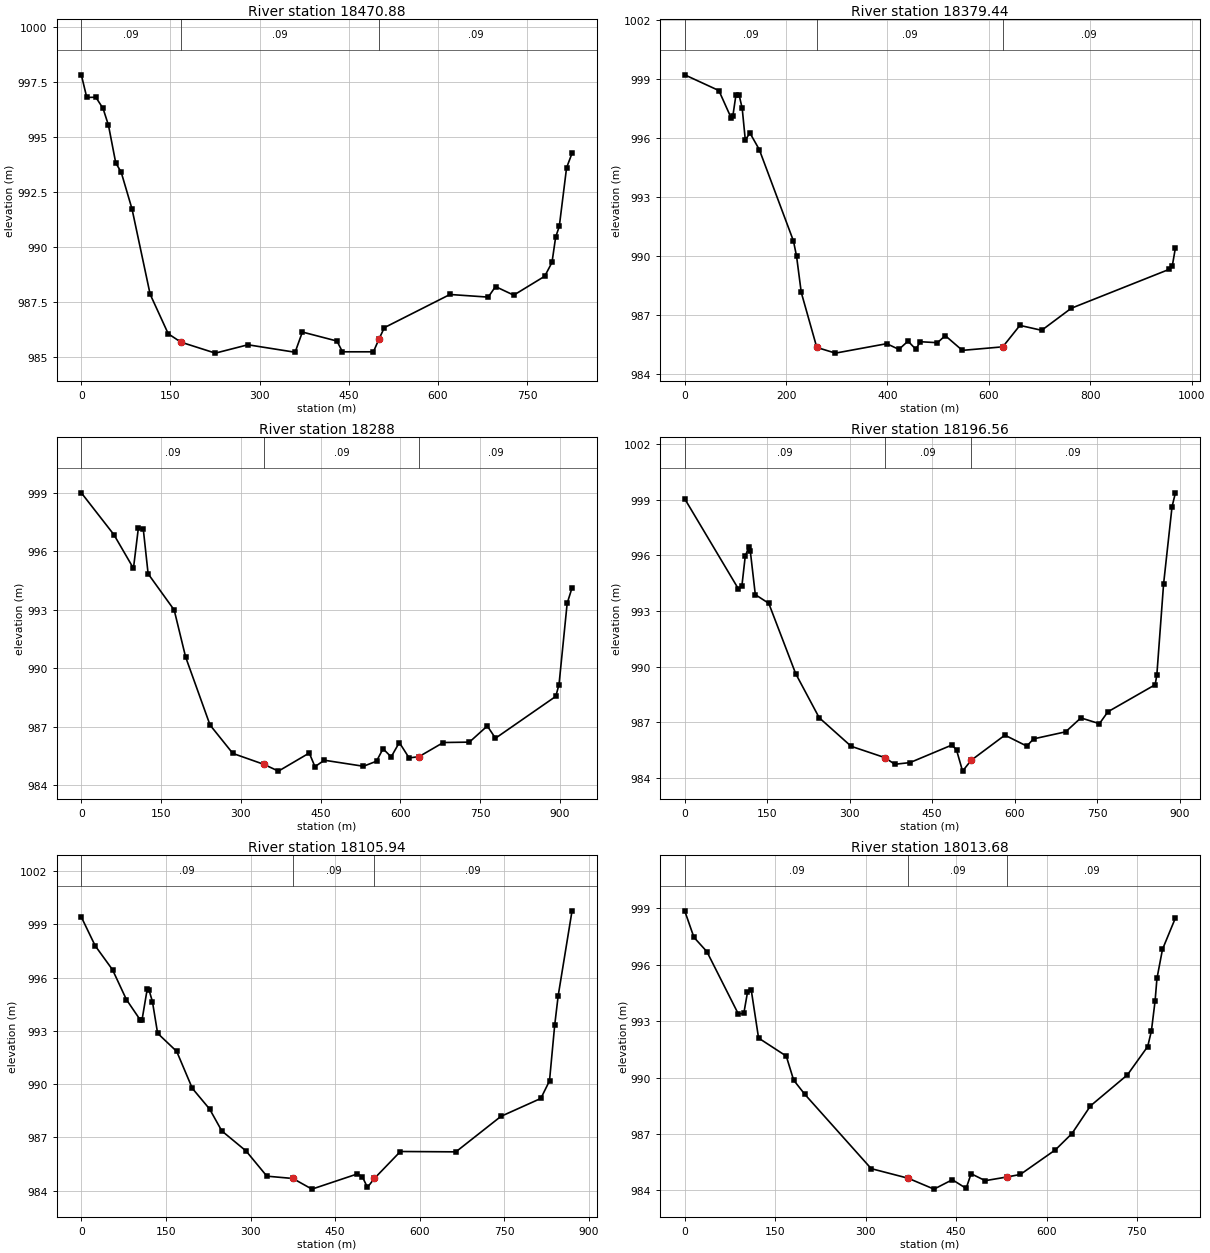
Type RM Length L Ch R = 1 ,18470.88,95.73,91.44,93.55
XS GIS Cut Line= 4
      642309.438    4339675.6071     642249.2209    4339968.1429
     642186.5241    4340026.3616642087.3109034724340456.70127207
#Sta/Elev= 30
       0  997.83    9.14   996.8   24.38  996.81   36.57   996.3   45.71  995.53
   57.91  993.82   67.05   993.4   85.33  991.72  115.81  987.84  146.29  986.04
  167.62  985.66  225.53  985.16  280.38  985.54  359.78   985.2  372.01  986.12
  430.23  985.71  439.43  985.22  491.57  985.22  500.77  985.79  509.97  986.32
  620.37  987.83  684.78  987.71  697.04  988.19  727.71   987.8  779.85  988.66
  792.11  989.29  798.25  990.44  804.38  990.93  816.65   993.6  825.85  994.26
#Mann= 3 , 0 , 0
       0     .09       0  167.62     .09       0  500.77     .09       0
Bank Sta=167.62,500.77
XS Rating Curve= 0 ,0
Exp/Cntr=0.3,0.1

Type RM Length L Ch R = 1 ,18379.44,96.98,91.44,89.18
XS GIS Cut Line= 5
     642308.2788    4339546.1577     642203.7931    4339933.8813
     642201.5292    4339966.7088     642162.2765    4339971.9939
 642032.15667302 4340448.4684051
#Sta/Elev= 30
       0  999.19   67.44  998.39   91.96  996.98   95.02   997.1  101.16  998.18
  107.29  998.17  113.42  997.49  119.55  995.88  128.74  996.23  147.13  995.39
  214.57  990.74   220.7  989.96   229.9  988.13  260.55  985.33  297.33  985.04
  398.49  985.52   422.5  985.23  440.55  985.65  455.79  985.24  464.93  985.62
  498.61  985.57  513.95  985.93   547.7  985.18  627.46  985.36  661.21  986.45
  704.16   986.2  762.45  987.32  955.72   989.3  961.86  989.48  967.99  990.39
#Mann= 3 , 0 , 0
       0     .09       0  260.55     .09       0  627.46     .09       0
Bank Sta=260.55,627.46
XS Rating Curve= 0 ,0
Exp/Cntr=0.3,0.1

Type RM Length L Ch R = 1 ,18288   ,80.59,91.44,101.31
XS GIS Cut Line= 4
     642292.4038     4339524.991     642132.6106    4339909.9273
     642145.1704    4339938.5158641999.0155627844340390.62530081
#Sta/Elev= 30
       0  999.01   61.29  996.86   98.07  995.13  107.26  997.19  116.45  997.17
  125.65  994.85  174.68  992.99  196.13  990.58   242.1  987.08  285.01  985.62
  343.24  985.06  370.82  984.71  428.78  985.64   439.5  984.94  457.21  985.27
  530.78  984.96   555.3  985.22  567.57  985.86  582.89  985.44  598.22  986.18
  616.61  985.39  635.01  985.45  680.99  986.18  730.04   986.2  763.76  987.03
  779.09   986.4  892.51  988.55  898.64  989.16  913.97  993.33  923.16  994.13
#Mann= 3 , 0 , 0
       0     .09       0  343.24     .09       0  635.01     .09       0
Bank Sta=343.24,635.01
XS Rating Curve= 0 ,0
Exp/Cntr=0.3,0.1

Type RM Length L Ch R = 1 ,18196.56,103.08,90.62,92.38
XS GIS Cut Line= 6
     642273.3538    4339508.0577     642096.9106    4339961.0263
     642077.7744    4339962.4438     642075.6358    4339963.5367
     642065.7933    4339965.5211      641892.353    4340297.5759
#Sta/Elev= 30
       0  999.05   97.84  994.18  103.95  994.33  110.06  995.94  116.18  996.43
  119.24  996.25  128.41  993.88  152.87  993.41  201.79  989.62  244.59  987.24
  302.68   985.7  363.83  985.09  382.17  984.73  409.69  984.82  486.12  985.77
  494.34   985.5  505.31  984.36  520.82  984.94  582.24   986.3  622.15  985.71
  634.44   986.1  692.78  986.48  720.42  987.23  754.19  986.92  769.55  987.56
  855.53  989.02   858.6  989.55  870.88  994.46  886.23  998.62  892.37  999.37
#Mann= 3 , 0 , 0
       0     .09       0  363.83     .09       0  520.82     .09       0
Bank Sta=363.83,520.82
XS Rating Curve= 0 ,0
Exp/Cntr=0.3,0.1

Type RM Length L Ch R = 1 ,18105.94,82.47,92.26,109.96
XS GIS Cut Line= 2
     642267.0038     4339493.241      641866.953    4340265.8259
#Sta/Elev= 30
       0  999.42   24.59   997.8   55.34  996.45   79.93  994.77  104.52  993.62
   107.6  993.62  116.82  995.36   119.9  995.32  126.04  994.66  135.27  992.87
  169.08  991.85  196.75  989.77   227.5   988.6  249.02  987.37  292.06  986.24
  328.95  984.82  375.06  984.69  408.88  984.09  488.81  984.94  498.03   984.8
  507.25  984.19  519.55  984.69  565.66  986.21  664.04  986.19  743.97  988.19
  814.68   989.2  830.05  990.19  839.27  993.33  845.42  994.98  870.02  999.77
#Mann= 3 , 0 , 0
       0     .09       0  375.06     .09       0  519.55     .09       0
Bank Sta=375.06,519.55
XS Rating Curve= 0 ,0
Exp/Cntr=0.3,0.1

Type RM Length L Ch R = 1 ,18013.68,111.12,91.44,76.62
XS GIS Cut Line= 5
     642243.7204    4339491.1243     642051.9542    4339888.2393
     642032.8583    4339866.9679     642023.2918    4339857.4937
     641824.6195    4340121.8922
#Sta/Elev= 30
       0  998.87   15.31  997.46   36.75   996.7   88.81  993.39      98  993.41
  104.12  994.53  110.25  994.68   122.5   992.1  168.43  991.14  180.68  989.86
  199.06  989.11  309.31  985.15  370.56  984.64  413.43  984.06  443.85  984.56
  466.72   984.1  474.96  984.88  498.35  984.51   535.1  984.71  556.54  984.84
  614.72  986.15  642.28  987.02   672.9  988.49  734.15  990.14  767.83  991.65
  773.96  992.48  780.08  994.08  783.14  995.27  792.33  996.82  813.77  998.49
#Mann= 3 , 0 , 0
       0     .09       0  370.56     .09       0   535.1     .09       0
Bank Sta=370.56,535.1
XS Rating Curve= 0 ,0
Exp/Cntr=0.3,0.1

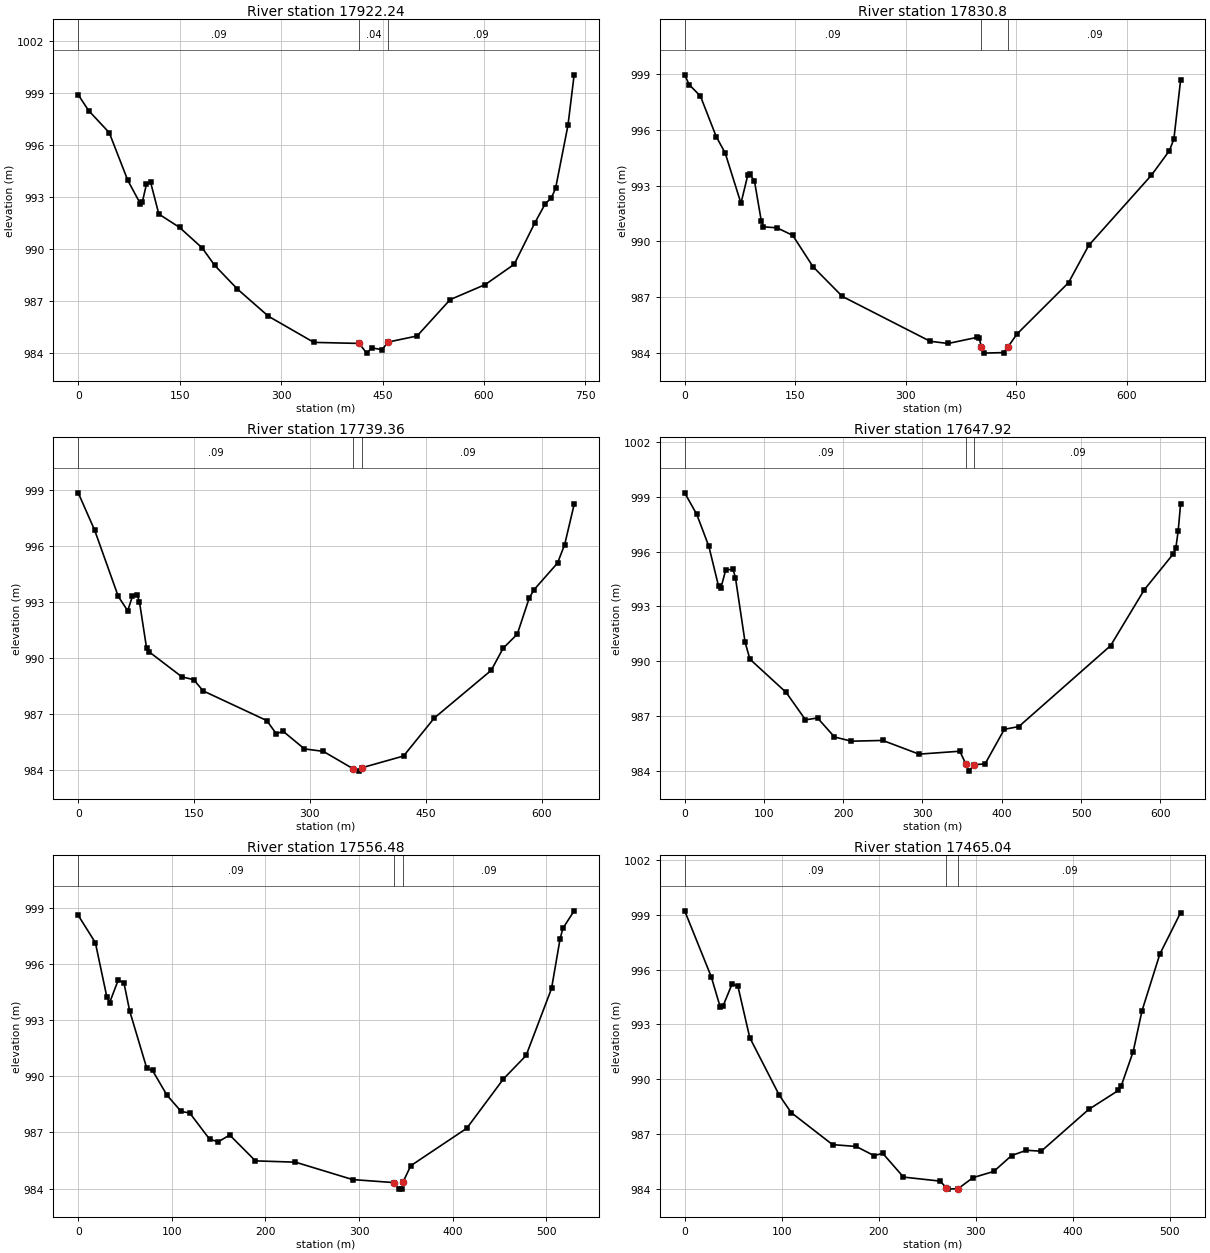
Type RM Length L Ch R = 1 ,17922.24,85.35,91.44,102.26
XS GIS Cut Line= 6
     642229.2565    4339479.8354     641997.3052    4339817.4842
     641997.2879    4339832.1541     641997.5575    4339834.2869
     642000.8771    4339844.2072     641821.7973    4340080.4408
#Sta/Elev= 30
       0  998.91   15.29     998   45.86  996.72   73.37  993.96   91.71  992.63
   94.77  992.71  100.88  993.74     107  993.86  119.22  992.02   149.8  991.25
  183.42  990.06  201.76  989.06  235.39  987.69  281.25  986.12   348.5  984.61
  415.51  984.55  426.46  983.99  434.31  984.29  449.15  984.19  458.32  984.63
   501.1  984.98     550  987.08  601.95  987.95  644.74  989.12   675.3  991.52
  690.58  992.61  699.75  992.96  705.86   993.5   724.2  997.14  733.36 1000.06
#Mann= 3 , 0 , 0
       0     .09       0  415.51     .04       0  458.32     .09       0
Bank Sta=415.51,458.32
XS Rating Curve= 0 ,0
Exp/Cntr=0.3,0.1

Type RM Length L Ch R = 1 ,17830.8 ,89.16,91.44,90.93
XS GIS Cut Line= 5
     642205.4439    4339479.8354      641981.881    4339789.6182
     641957.7908    4339800.9835     641946.3932    4339804.6442
      641776.818    4339991.8052
#Sta/Elev= 30
       0  998.98    6.11  998.45   21.39  997.83   42.79  995.65   55.01  994.76
   76.41  992.05   85.57  993.56   88.63  993.62   94.74  993.25  103.91  991.12
  106.97  990.78  125.31  990.73   146.7  990.32  174.21  988.63  213.94  987.03
  333.13  984.61  357.58  984.49  396.83  984.82  399.79  984.78  402.75   984.3
  405.71  983.97  432.81     984  438.89  984.31  451.06     985  521.05  987.77
  548.44  989.78  633.64  993.57  657.98  994.89  664.06  995.52  673.19   998.7
#Mann= 3 , 0 , 0
       0     .09       0  402.75     .04       0  438.89     .09       0
Bank Sta=402.75,438.89
XS Rating Curve= 0 ,0
Exp/Cntr=0.3,0.1

Type RM Length L Ch R = 1 ,17739.36,103.08,91.44,80.67
XS GIS Cut Line= 6
     642151.2042    4339456.0228     641951.0102    4339740.4032
     641939.6423    4339745.7525     641932.1912     4339747.472
     641899.7868    4339767.0733      641745.068     4339945.503
#Sta/Elev= 30
       0  998.87   21.35  996.86   51.86  993.32   64.06  992.55   70.17  993.32
   76.27  993.41   79.32  993.02   88.47  990.56   91.52  990.36  134.23  989.01
  149.48  988.86  161.69  988.26  244.05  986.67  256.26  985.97  265.41  986.09
  292.87  985.15  317.27  985.02  355.32   984.1  362.89  983.96  367.99  984.15
   421.2  984.77  461.07  986.81  534.68  989.36  550.01  990.54  568.42   991.3
  583.75  993.22  589.89  993.67  620.56  995.11  629.76   996.1  642.03  998.25
#Mann= 3 , 0 , 0
       0     .09       0  355.32     .04       0  367.99     .09       0
Bank Sta=355.32,367.99
XS Rating Curve= 0 ,0
Exp/Cntr=0.3,0.1

Type RM Length L Ch R = 1 ,17647.92,81.73,91.44,105.91
XS GIS Cut Line= 6
     642067.0665     4339410.779     641866.7287    4339690.9255
     641867.8979    4339701.3928       641870.28    4339704.5351
     641877.0474    4339716.5901     641709.3492    4339905.8154
#Sta/Elev= 30
       0  999.22   15.24  998.04   30.48  996.29   42.67  994.12   45.72  994.02
   51.81     995   60.96  995.03   64.01  994.58    76.2  991.04   82.29  990.11
  128.01  988.29  152.39  986.79  167.63  986.89  188.97  985.85   210.3  985.62
  249.92  985.66  295.64  984.91  347.04  985.07  354.94  984.35  358.88  983.98
  365.01  984.34  378.86  984.37  403.23  986.27  421.51  986.42  537.27  990.85
  579.92  993.92  616.47  995.88  619.52  996.18  622.57  997.14  625.61  998.63
#Mann= 3 , 0 , 0
       0     .09       0  354.94     .04       0  365.01     .09       0
Bank Sta=354.94,365.01
XS Rating Curve= 0 ,0
Exp/Cntr=0.3,0.1

Type RM Length L Ch R = 1 ,17556.48,96.18,91.44,77.28
XS GIS Cut Line= 6
     642051.1915    4339412.1019     641857.5266    4339655.9766
     641823.4481    4339656.1546     641819.4989    4339657.0475
      641805.456    4339658.2069     641654.3157    4339726.9567
#Sta/Elev= 30
       0   998.6   18.32  997.14   30.53  994.25   33.58  993.94   42.74  995.14
   48.85  994.99   54.96  993.49   73.27  990.42   79.38  990.31   94.65     989
  109.91  988.12  119.07  988.04  140.44  986.63   149.6   986.5  161.82  986.86
  189.29  985.48  232.04  985.41   293.1  984.48  336.98  984.32  342.66  983.97
   345.5  983.98  347.12  984.37  355.18  985.22  414.96  987.22   454.2  989.86
  478.36  991.11  505.53  994.69  514.58  997.32   517.6   997.9  529.68  998.84
#Mann= 3 , 0 , 0
       0     .09       0  336.98     .04       0  347.12     .09       0
Bank Sta=336.98,347.12
XS Rating Curve= 0 ,0
Exp/Cntr=0.3,0.1

Type RM Length L Ch R = 1 ,17465.04,60.56,91.44,94.49
XS GIS Cut Line= 6
     642040.6082    4339398.8727     641853.7338    4339560.3109
     641836.8303    4339569.1708     641828.5368    4339574.9053
     641820.9254    4339579.5726     641643.7324    4339720.3421
#Sta/Elev= 30
       0  999.23   27.44  995.61   36.59  993.96   39.63  994.02   48.78  995.21
   54.88   995.1   67.07  992.28   97.56  989.12  109.76  988.17  152.44  986.41
  176.83  986.31  195.12  985.81  204.27  985.93  225.61  984.63  263.31  984.41
  269.95  984.04  271.67  983.97  282.09     984   297.3   984.6   318.7  984.94
  337.05  985.81  352.34   986.1  367.64  986.05  416.57  988.34  447.15  989.38
  450.21  989.64  462.44  991.51  471.61  993.76  489.96  996.86  511.37  999.13
#Mann= 3 , 0 , 0
       0     .09       0  269.95     .04       0  282.09     .09       0
Bank Sta=269.95,282.09
XS Rating Curve= 0 ,0
Exp/Cntr=0.3,0.1

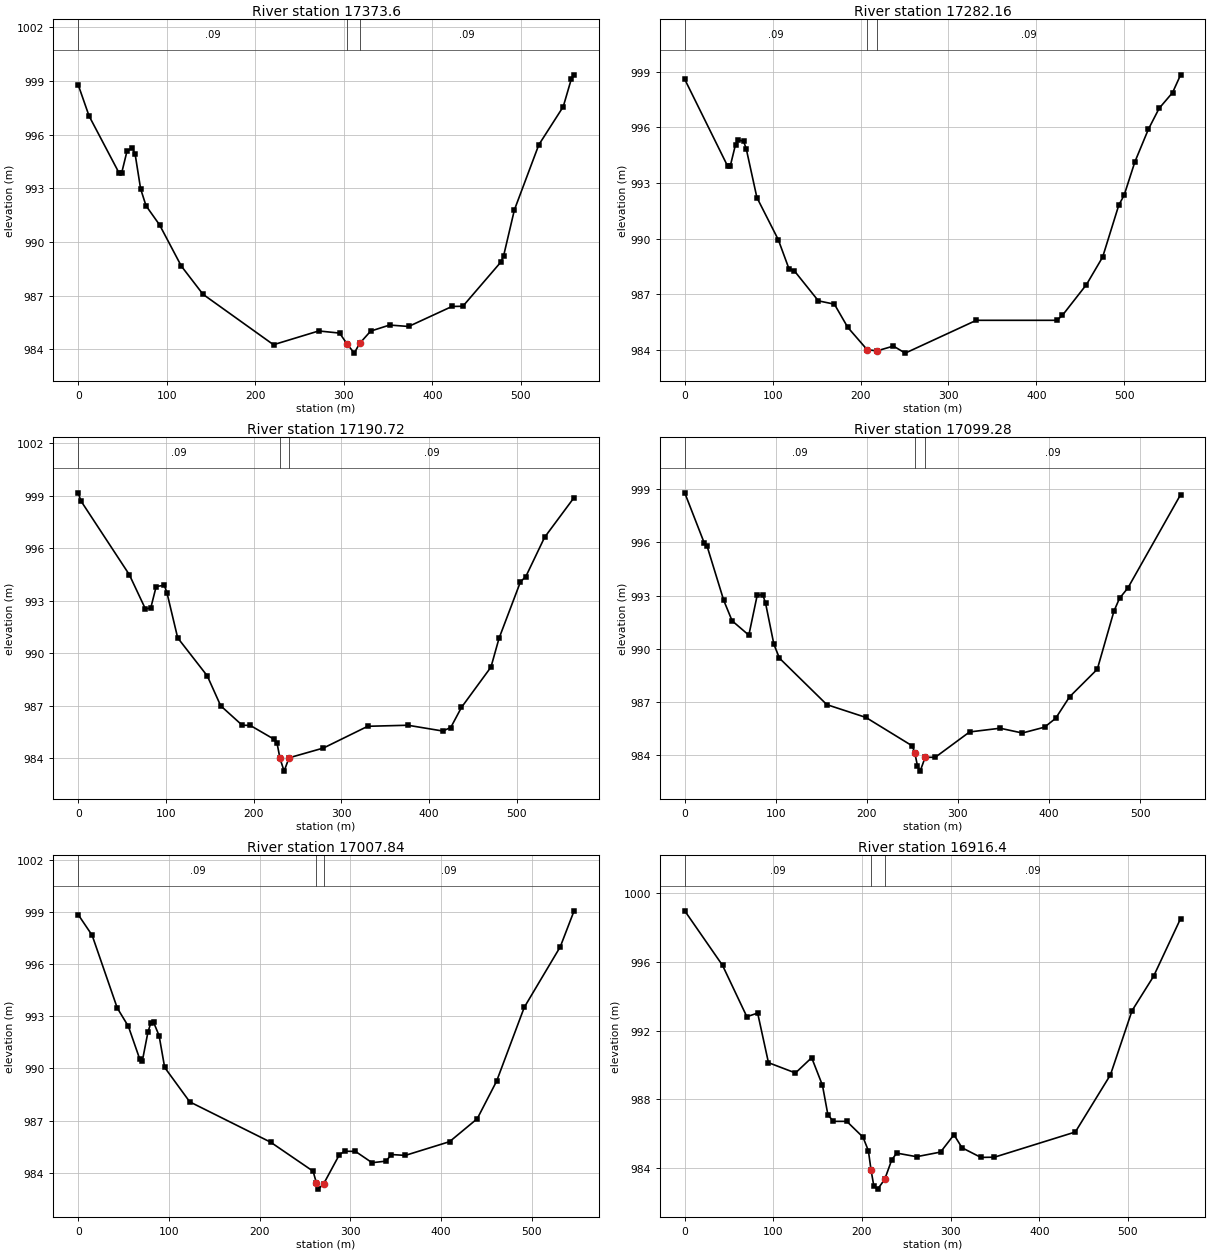
Type RM Length L Ch R = 1 ,17373.6 ,73.17,91.44,74.06
XS GIS Cut Line= 6
      642026.056    4339376.3831     641850.4022    4339533.8173
     641809.4446    4339541.9135     641783.0921    4339536.1985
     641765.7883    4339520.7997     641614.6281    4339693.8837
#Sta/Elev= 30
       0  998.79   12.25  997.05   45.95  993.88   49.01  993.85   55.14  995.09
   61.27  995.26   64.33   994.9   70.46  992.98   76.58  992.03    91.9  990.96
  116.41  988.66  140.92  987.08  220.56  984.26  271.67  985.03  295.21  984.91
  303.97  984.28  311.77  983.79  317.83  984.33  330.25  985.02   351.7  985.36
  373.15  985.28  422.17   986.4  434.43  986.41  477.32  988.88  480.39  989.22
  492.64   991.8  520.22  995.44   547.8  997.57  556.99  999.13  560.05  999.35
#Mann= 3 , 0 , 0
       0     .09       0  303.97     .04       0  317.83     .09       0
Bank Sta=303.97,317.83
XS Rating Curve= 0 ,0
Exp/Cntr=0.3,0.1

Type RM Length L Ch R = 1 ,17282.16,121.49,91.44,27.67
XS GIS Cut Line= 6
     642016.7956    4339363.1539     641866.1912    4339495.8197
     641854.7305    4339485.4523     641817.5078    4339472.1394
     641745.4072    4339510.3631     641604.0448    4339687.2691
#Sta/Elev= 30
       0   998.6   48.66  993.93    51.7   993.9   57.78  995.08   60.82  995.33
    66.9  995.26   69.94  994.86   82.11  992.22  106.43  989.95   118.6  988.38
  124.68  988.27  152.05  986.65  170.29  986.47   185.5  985.22  207.47  984.02
  218.68  983.95  237.42  984.21  250.89  983.83  331.76   985.6  423.49   985.6
  429.61  985.86  457.15  987.53  475.51  989.01  493.87  991.81  499.99  992.35
  512.23  994.15  527.53   995.9  539.77  997.03  555.07  997.88  564.25  998.84
#Mann= 3 , 0 , 0
       0     .09       0  207.47     .04       0  218.68     .09       0
Bank Sta=207.47,218.68
XS Rating Curve= 0 ,0
Exp/Cntr=0.3,0.1

Type RM Length L Ch R = 1 ,17190.72,89.72,91.44,90.76
XS GIS Cut Line= 6
     641936.0975    4339257.3204     641804.0502    4339418.6598
     641803.5603    4339453.3718     641801.5914    4339468.9596
     641736.3696    4339504.2791     641588.1698    4339683.3004
#Sta/Elev= 30
       0  999.16    3.07   998.7   58.25  994.49   76.65  992.53   82.78  992.59
   88.91  993.81   98.11  993.88  101.18  993.46  113.44  990.88  147.17  988.71
   162.5     987  187.03  985.89  196.22  985.88  223.71  985.08  226.75  984.87
  230.11     984  234.83  983.27  240.44  984.03  279.73  984.59  330.17  985.83
  375.95  985.89   415.7  985.56  424.87  985.76  437.11  986.91  470.74  989.21
  479.92  990.85  504.38  994.08   510.5  994.38   531.9  996.62  565.54  998.89
#Mann= 3 , 0 , 0
       0     .09       0  230.11     .04       0  240.44     .09       0
Bank Sta=230.11,240.44
XS Rating Curve= 0 ,0
Exp/Cntr=0.3,0.1

Type RM Length L Ch R = 1 ,17099.28,55.19,91.44,83.67
XS GIS Cut Line= 6
     641877.0071    4339225.1293     641721.1931    4339397.7153
      641717.652     4339414.429     641714.4198    4339439.6254
     641717.3831    4339446.1871     641566.1211    4339660.3698
#Sta/Elev= 30
       0   998.8   21.42  995.97   24.48   995.8   42.83  992.73   52.01  991.58
   70.37  990.77   79.55  993.02   85.66  993.05   88.72  992.58    97.9  990.25
  104.02  989.47  156.03  986.85  198.86  986.13   249.6  984.53  252.56  984.15
  255.52  983.39  258.48   983.1     264  983.88  275.04  983.88  312.73  985.31
  346.27  985.52  370.66  985.25  395.05  985.58  407.25  986.08   422.5  987.29
  452.98  988.85  471.28  992.13  477.38  992.85  486.52  993.43  544.45   998.7
#Mann= 3 , 0 , 0
       0     .09       0  252.56     .04       0     264     .09       0
Bank Sta=252.56,264
XS Rating Curve= 0 ,0
Exp/Cntr=0.3,0.1

Type RM Length L Ch R = 1 ,17007.84,93.91,91.44,52.06
XS GIS Cut Line= 6
     641857.1633    4339209.2543     641693.6499    4339388.7873
     641682.6013    4339395.8875     641663.6381    4339403.5488
      641643.379    4339414.5842     641501.2981    4339616.7134
#Sta/Elev= 30
       0  998.85   15.37  997.66   43.03  993.48   55.33  992.42   67.62  990.57
    70.7  990.44   76.85  992.09   79.92   992.6   82.99  992.67   89.14  991.89
   95.29  990.06  122.95  988.08   212.1  985.76  258.89  984.09  262.57  983.41
  264.73  983.06  270.58  983.37  287.96  985.05  293.72  985.24  305.59  985.23
  323.89  984.58  339.14  984.67  345.24  985.05  360.49     985   409.3  985.79
   439.8  987.11  461.15  989.27  491.66  993.52  531.31     997  546.56  999.07
#Mann= 3 , 0 , 0
       0     .09       0  262.57     .04       0  270.58     .09       0
Bank Sta=262.57,270.58
XS Rating Curve= 0 ,0
Exp/Cntr=0.3,0.1

Type RM Length L Ch R = 1 ,16916.4 ,129.33,91.44,21.6
XS GIS Cut Line= 6
     641781.7569    4339153.6917       641629.37    4339330.6438
     641634.7236    4339358.0819     641627.8444    4339367.8715
     641635.2527     4339415.706     641498.6522    4339610.0988
#Sta/Elev= 30
       0  998.99   42.66  995.81   70.08  992.82   82.27  993.03   94.46  990.14
  124.93  989.54  143.21  990.43   155.4  988.82   161.5  987.11  167.59  986.72
  182.83  986.72  201.11   985.8   207.2  985.01  210.25  983.87   213.3  982.97
  217.66  982.77  225.63  983.34   233.6  984.48  239.19  984.87  261.55  984.66
  288.65  984.93  303.77  985.94  312.85  985.18  334.11  984.62  349.34  984.63
  440.72   986.1  480.32  989.43  504.68  993.17  529.05  995.18  559.51  998.54
#Mann= 3 , 0 , 0
       0     .09       0  210.25     .04       0  225.63     .09       0
Bank Sta=210.25,225.63
XS Rating Curve= 0 ,0
Exp/Cntr=0.3,0.1

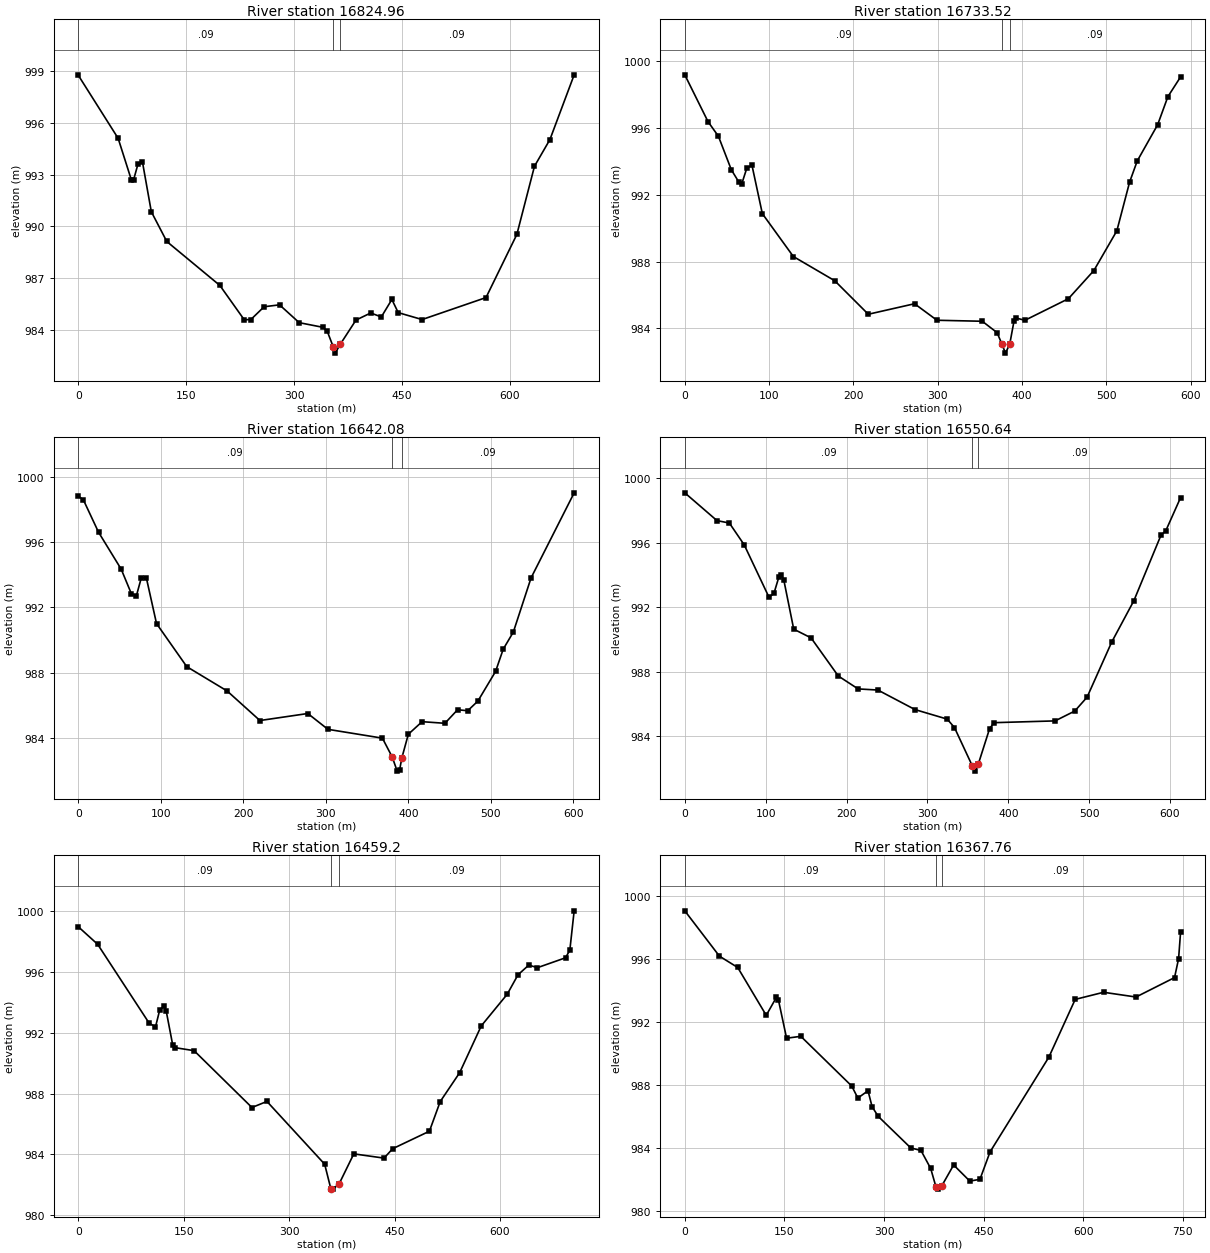
Type RM Length L Ch R = 1 ,16824.96,30.18,91.44,92.11
XS GIS Cut Line= 6
     641734.1319    4339104.7437     641557.0726    4339313.3121
     641553.0688    4339364.8045     641597.4305    4339349.0838
     641630.0978    4339419.6748     641490.7147    4339606.1301
#Sta/Elev= 30
       0  998.73   55.33  995.09   73.78  992.68   76.85   992.7      83  993.62
   89.15  993.72  101.44  990.85  122.96  989.13  196.74  986.59  230.55  984.61
  239.77  984.62  258.22  985.36  279.66  985.47  307.01  984.44  340.13  984.17
  346.09  983.93  354.61  983.01  356.98  982.68  364.21   983.2   385.9  984.59
  406.42     985  421.11  984.77   435.8  985.78  444.61  985.02  477.81  984.62
  566.64  985.89  609.52  989.54  634.02  993.48  655.47  995.02  689.16  998.76
#Mann= 3 , 0 , 0
       0     .09       0  354.61     .04       0  364.21     .09       0
Bank Sta=354.61,364.21
XS Rating Curve= 0 ,0
Exp/Cntr=0.3,0.1

Type RM Length L Ch R = 1 ,16733.52,15.39,91.44,99.1
XS GIS Cut Line= 6
     641718.2568    4339104.7437     641555.4785    4339312.1655
     641551.3157    4339371.1236     641575.8691    4339409.0121
     641579.0441    4339441.3971     641480.1313    4339600.8384
#Sta/Elev= 30
       0   999.2   27.59  996.39   39.86  995.52   55.19  993.51   64.38  992.75
   67.45  992.65   73.58  993.61   79.71  993.77   91.98  990.88  128.77  988.31
  177.82  986.86  217.68  984.85  272.53  985.48  299.13  984.49  352.87  984.43
  370.39  983.75  376.31  983.05  380.34  982.52  385.42  983.05  390.47  984.43
  392.99  984.62  403.55  984.49     455  985.78  485.26  987.47   512.5  989.85
  527.63  992.77  536.71  994.04  560.92  996.21  573.03  997.89  588.16  999.08
#Mann= 3 , 0 , 0
       0     .09       0  376.31     .04       0  385.42     .09       0
Bank Sta=376.31,385.42
XS Rating Curve= 0 ,0
Exp/Cntr=0.3,0.1

Type RM Length L Ch R = 1 ,16642.08,92.23,91.44,53.24
XS GIS Cut Line= 6
     641711.6422    4339096.8062     641553.8068    4339310.7995
     641548.9649     4339380.729     641541.2733     4339402.982
      641491.021    4339397.8741     641380.9124    4339553.2133
#Sta/Elev= 30
       0  998.81    6.11  998.58   24.45   996.6   51.96  994.33   64.18  992.84
    70.3  992.69   76.41  993.82   82.52  993.78   94.75     991  131.42  988.36
  180.33  986.87  220.06  985.06   278.1  985.49  302.48  984.52  368.49  983.98
  380.42  982.82  386.39  981.96  389.37  982.04     392  982.76   399.9  984.22
   416.6  984.99  444.23  984.89  459.59  985.72  471.87  985.66  484.16  986.25
  505.66  988.07  514.87  989.43  527.15  990.48  548.65   993.8  600.86  999.01
#Mann= 3 , 0 , 0
       0     .09       0  380.42     .04       0     392     .09       0
Bank Sta=380.42,392
XS Rating Curve= 0 ,0
Exp/Cntr=0.3,0.1

Type RM Length L Ch R = 1 ,16550.64,89.18,91.44,99.95
XS GIS Cut Line= 6
     641701.0589    4339038.5977      641510.103    4339304.6992
     641499.6115    4339336.4795     641498.6371    4339343.9156
     641491.2435    4339361.8274     641359.4811     4339544.482
#Sta/Elev= 30
       0  999.08   39.79  997.36    55.1  997.21   73.46  995.86  104.07  992.62
   110.2  992.85  116.32  993.87  119.38     994  122.44  993.68  134.68  990.64
  156.11   990.1  189.78  987.74  214.27  986.94  238.76  986.87  284.67  985.66
  324.47  985.07  333.42  984.55  355.48  982.18  358.24  981.85  362.82  982.27
  376.81  984.47  382.34  984.85  457.88  984.96  482.23  985.57  497.45  986.43
  527.88  989.84  555.27   992.4  588.75  996.45  594.84  996.74   613.1  998.79
#Mann= 3 , 0 , 0
       0     .09       0  355.48     .04       0  362.82     .09       0
Bank Sta=355.48,362.82
XS Rating Curve= 0 ,0
Exp/Cntr=0.3,0.1

Type RM Length L Ch R = 1 ,16459.2 ,86.34,91.44,94.87
XS GIS Cut Line= 6
     641647.3748    4338992.2955     641436.5745    4339264.9395
     641427.8895    4339280.3988     641425.0693    4339283.6264
      641419.747    4339287.9583     641210.2558    4339545.5404
#Sta/Elev= 30
       0  998.97   27.45  997.82  100.64  992.64  109.79  992.38  115.89  993.51
  121.99  993.75  125.04  993.43  134.19  991.22  137.24  991.02  164.69  990.82
  247.04  987.08  268.39  987.48  350.54  983.35   359.4  981.72   362.4  981.71
  371.26  982.07  391.99  984.03  435.03  983.75  447.33  984.37  499.59  985.52
  514.96  987.47  542.63  989.37  573.37  992.45  610.27  994.53  625.64  995.81
  641.01  996.45  653.31  996.28  693.27  996.93  699.42  997.43  705.57 1000.02
#Mann= 3 , 0 , 0
       0     .09       0   359.4     .04       0  371.26     .09       0
Bank Sta=359.4,371.26
XS Rating Curve= 0 ,0
Exp/Cntr=0.3,0.1

Type RM Length L Ch R = 1 ,16367.76,88.23,91.44,62.58
XS GIS Cut Line= 6
     641604.2476    4338935.6746     641373.7755    4339218.4918
     641361.8683    4339225.1038      641348.445    4339230.0574
     641330.6484    4339241.5106     641159.7467    4339527.0195
#Sta/Elev= 30
       0  999.03   52.12  996.16   79.71  995.44  122.63  992.41  137.96  993.55
  141.03  993.38  153.29  990.96  174.75  991.08   251.4  987.93  260.59  987.17
  275.92  987.63  282.06  986.62  291.25  986.01  340.31  984.01  355.64  983.85
  370.28  982.71  378.45  981.51  381.31   981.4  387.04  981.61  404.85  982.93
  429.19  981.91  444.45  982.02  459.72  983.76  548.25  989.76  587.93  993.42
  630.67  993.87  679.51  993.57  737.52   994.8  743.62     996  746.68  997.72
#Mann= 3 , 0 , 0
       0     .09       0  378.45     .04       0  387.04     .09       0
Bank Sta=378.45,387.04
XS Rating Curve= 0 ,0
Exp/Cntr=0.3,0.1