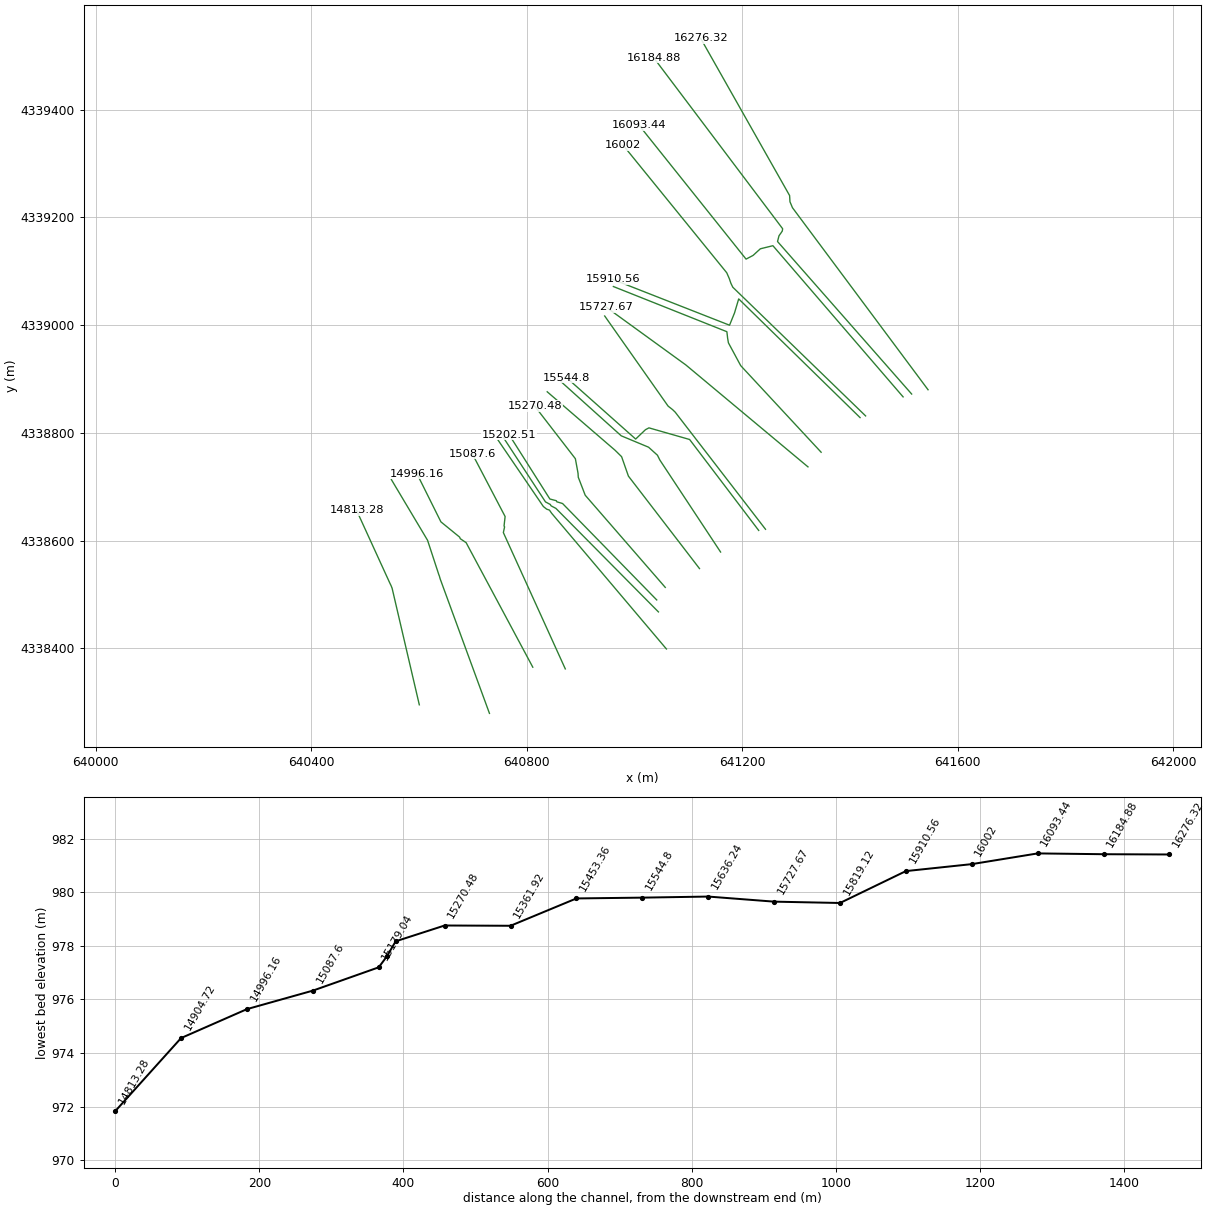
HEC-RAS study BeaverCreek.prj: BeaverCreek

--- BeaverCreek.g01 (geometry) --- (continued)

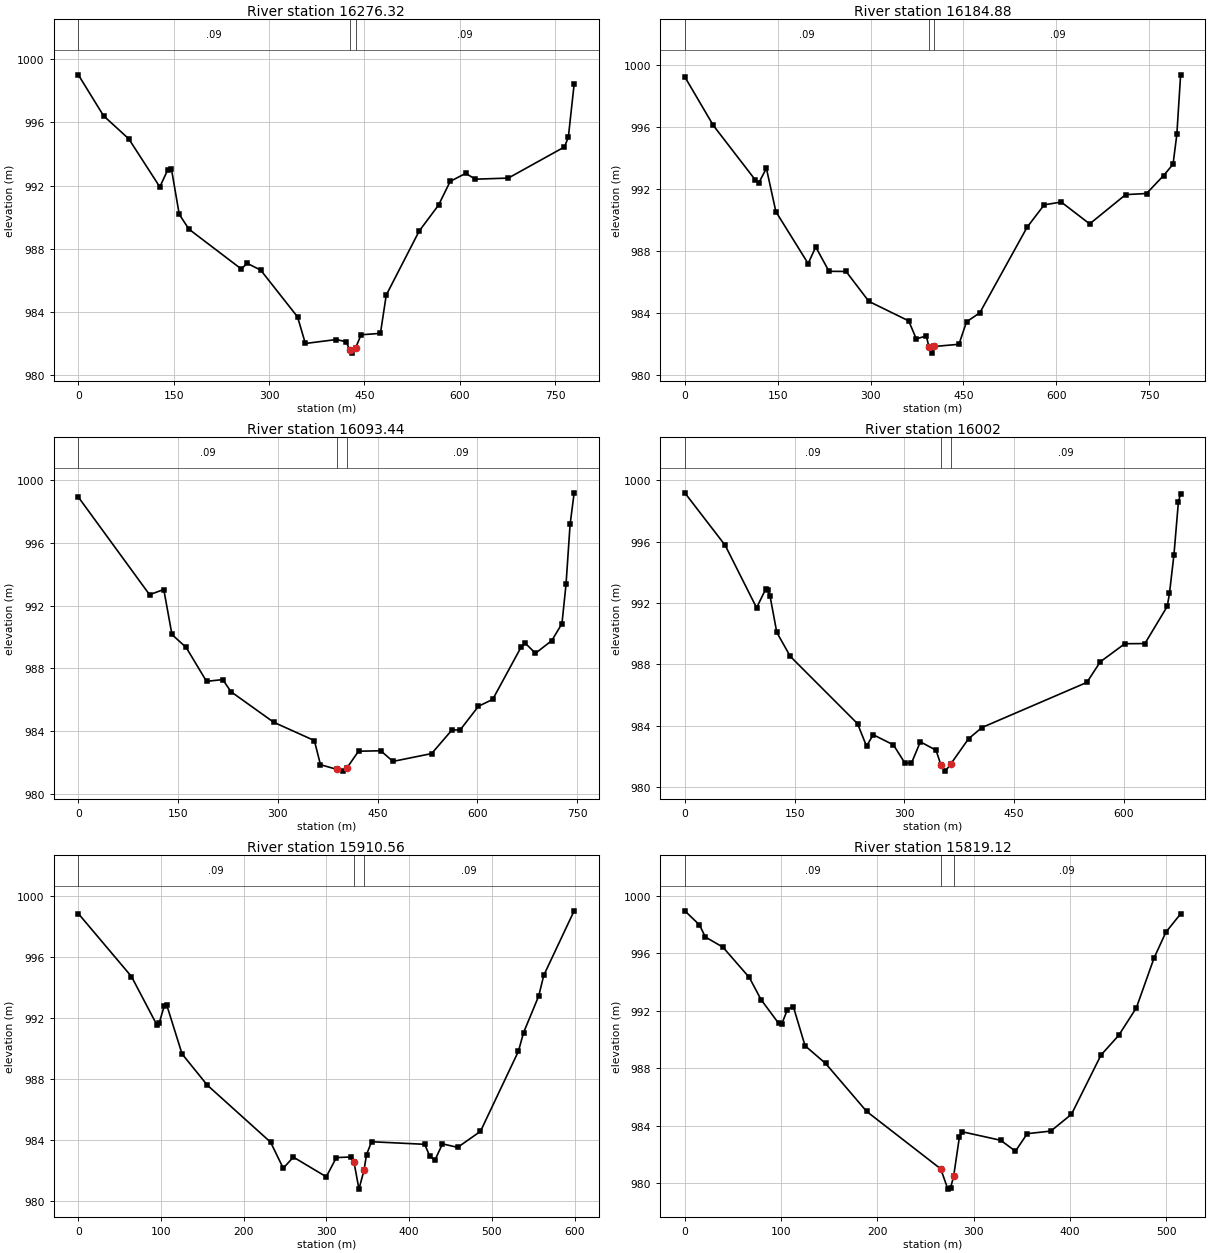
Type RM Length L Ch R = 1 ,16276.32,80.5,91.44,51.23
XS GIS Cut Line= 5
     641544.7163     4338880.112     641293.1052    4339217.9199
     641288.4477    4339229.0098     641287.7858    4339240.5206
      641122.705    4339532.3112
#Sta/Elev= 30
       0  999.01   39.68  996.42   79.36  994.96   128.2  991.92  140.41  992.98
  146.51  993.05  158.72  990.19  173.98  989.25  256.39  986.73  265.55  987.09
  286.91  986.66  344.91   983.7  357.12  982.02  405.95  982.27  421.22  982.13
  427.23   981.6  430.24  981.41  436.13  981.73  444.77  982.57  475.25  982.66
  484.39  985.08  536.21  989.13  566.68  990.77  584.97  992.27  609.35  992.78
  624.59  992.41   676.4  992.48  764.79  994.45  770.88  995.07  780.02  998.43
#Mann= 3 , 0 , 0
       0     .09       0  427.23     .04       0  436.13     .09       0
Bank Sta=427.23,436.13
XS Rating Curve= 0 ,0
Exp/Cntr=0.3,0.1

Type RM Length L Ch R = 1 ,16184.88,44.57,91.44,95.38
XS GIS Cut Line= 6
     641514.2891    4338872.1745     641265.3464    4339155.2263
     641268.0865     4339165.863     641274.1252    4339174.4835
     641274.8714     4339178.933     641035.3923    4339496.5924
#Sta/Elev= 30
       0  999.25   45.97  996.12  113.39  992.62  119.52  992.41  131.78  993.35
   147.1  990.55   199.2   987.2  211.46  988.27  232.91   986.7  260.49  986.69
  297.27  984.76  361.63   983.5  373.88  982.34  390.09  982.53  394.33  981.81
  398.47  981.42  402.98  981.85  442.76  981.99     455  983.44  476.43  984.02
  552.93  989.55  580.47  990.99  608.01  991.17  653.91  989.76  712.05  991.65
  745.72  991.72  773.26  992.88  788.56  993.61  794.68  995.53   800.8  999.38
#Mann= 3 , 0 , 0
       0     .09       0  394.33     .04       0  402.98     .09       0
Bank Sta=394.33,402.98
XS Rating Curve= 0 ,0
Exp/Cntr=0.3,0.1

Type RM Length L Ch R = 1 ,16093.44,103.46,91.44,64.16
XS GIS Cut Line= 6
     641498.4141    4338866.8828     641256.7901     4339147.466
     641233.4675    4339141.7171     641219.9822    4339129.4305
     641206.9395    4339122.5789     641008.1402    4339371.3119
#Sta/Elev= 30
       0  998.94  107.11  992.71  128.53  993.04  140.77  990.17  162.19  989.34
  192.79  987.18  217.27  987.29  229.51  986.52  293.78  984.57  354.98   983.4
  364.16  981.86   388.3  981.57  397.34  981.45  403.42  981.62  421.39  982.72
  454.83  982.75   473.2  982.07  531.38  982.57  561.99  984.08  574.24  984.08
   601.8  985.59  623.23  986.03  666.09  989.38  672.22  989.61  687.52  988.97
  712.02  989.78  727.33  990.86  733.45  993.36  739.57  997.19   745.7  999.21
#Mann= 3 , 0 , 0
       0     .09       0   388.3     .04       0  403.42     .09       0
Bank Sta=388.3,403.42
XS Rating Curve= 0 ,0
Exp/Cntr=0.3,0.1

Type RM Length L Ch R = 1 ,16002   ,67.92,91.44,113.14
XS GIS Cut Line= 6
     641428.8285    4338831.5608     641182.3227    4339070.4461
     641178.8171    4339077.7026      641175.811    4339086.5307
     641171.0778    4339097.3014     640978.7714    4339334.0056
#Sta/Elev= 30
       0  999.18   55.17  995.76   98.08  991.69  110.34  992.89   113.4  992.87
  116.47  992.45  125.66  990.09  144.05  988.53     236  984.14  248.25  982.68
  257.45  983.42  285.03  982.76  300.36   981.6  309.55  981.56  321.81  982.96
  343.27  982.41   349.9  981.45  355.99  981.05  363.59  981.53  387.66  983.16
  405.96  983.89   549.3  986.83   567.6  988.17  601.15  989.35  628.59  989.36
  659.09  991.78  662.14  992.63  668.24  995.13  674.34  998.58  677.39  999.13
#Mann= 3 , 0 , 0
       0     .09       0   349.9     .04       0  363.59     .09       0
Bank Sta=349.9,363.59
XS Rating Curve= 0 ,0
Exp/Cntr=0.3,0.1

Type RM Length L Ch R = 1 ,15910.56,115.95,91.44,66.71
XS GIS Cut Line= 5
     641418.5098    4338828.4652     641193.3065    4339048.7229
      641185.509    4339022.6179      641176.314    4338999.9112
     640959.7213     4339084.847
#Sta/Elev= 30
       0  998.87   64.22  994.74   94.81  991.58   97.87  991.71  103.98  992.83
  107.04  992.84  125.39  989.66  155.97  987.61  232.43  983.87  247.72  982.16
  259.96  982.89  299.72   981.6  311.95  982.86  330.14   982.9  333.17  982.59
  339.23  980.79  345.31  982.02  348.38  983.05   354.5   983.9  418.79  983.73
  424.91  982.94  431.04  982.69  440.22  983.76  458.59  983.53  486.14  984.58
  532.05  989.84  538.18  991.05  556.54  993.46  562.67  994.82   599.4  999.05
#Mann= 3 , 0 , 0
       0     .09       0  333.17     .04       0  345.31     .09       0
Bank Sta=333.17,345.31
XS Rating Curve= 0 ,0
Exp/Cntr=0.3,0.1

Type RM Length L Ch R = 1 ,15819.12,87.63,91.45,99.27
XS GIS Cut Line= 6
     641346.2784    4338764.1713     641197.0413    4338924.8723
     641174.2108     4338967.223     641172.7519    4338975.8159
     641171.3662    4338987.8448     640960.7135    4339071.6839
#Sta/Elev= 30
       0  998.97   15.23  997.99   21.32  997.15    39.6  996.44   67.01  994.33
   79.19  992.79   97.47  991.14  100.52  991.06  106.61   992.1   112.7  992.31
  124.88  989.58  146.21  988.35  188.85  985.01   265.8  981.01  273.24   979.6
  276.14  979.71  279.23   980.5  285.25  983.24  288.26  983.59  328.09     983
   343.4  982.24  355.66  983.46  380.17  983.64  401.62  984.81  432.26  988.93
  450.64   990.3  469.02  992.22   487.4  995.69  499.66  997.48  514.98  998.76
#Mann= 3 , 0 , 0
       0     .09       0   265.8     .04       0  279.23     .09       0
Bank Sta=265.8,279.23
XS Rating Curve= 0 ,0
Exp/Cntr=0.3,0.1

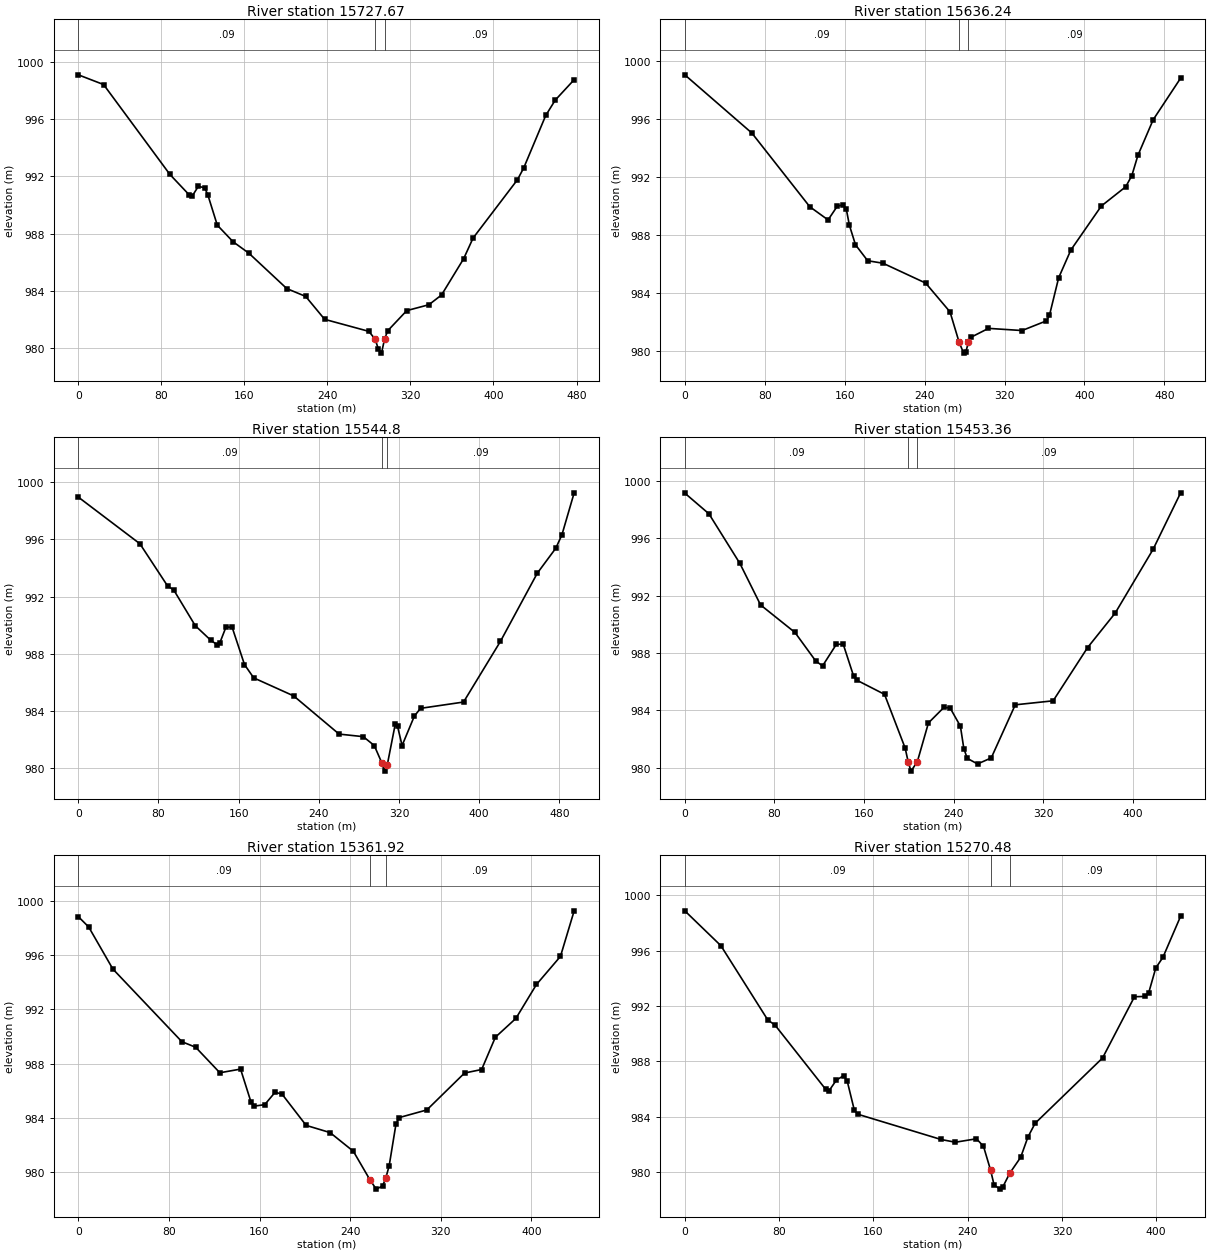
Type RM Length L Ch R = 1 ,15727.67,101.44,91.43,84.01
XS GIS Cut Line= 3
     641321.8705    4338736.9853     641095.2833    4338926.1078
     640947.4843    4339033.3193
#Sta/Elev= 30
       0  999.09   24.34  998.41   88.24  992.13  106.49  990.73  109.54   990.6
  115.62   991.3  121.71   991.2  124.75  990.71  133.88  988.59  149.09  987.43
  164.31  986.63  200.82  984.16  219.07  983.61  237.33  982.01  279.93  981.17
  286.01  980.62  289.06  979.94   292.1  979.65  295.14  980.66  298.19  981.22
  316.44  982.62  337.75  983.03  349.92  983.71  371.22  986.24  380.35  987.69
  422.96  991.75  429.04  992.57  450.34  996.25  459.47  997.32  477.73  998.75
#Mann= 3 , 0 , 0
       0     .09       0  286.01     .04       0  295.14     .09       0
Bank Sta=286.01,295.14
XS Rating Curve= 0 ,0
Exp/Cntr=0.3,0.1

Type RM Length L Ch R = 1 ,15636.24,69.08,91.44,105.46
XS GIS Cut Line= 5
     641243.0686    4338621.1858      641075.376    4338838.6372
     641070.5285    4338843.3116     641062.3085    4338849.7422
      640944.618    4339017.0032
#Sta/Elev= 30
       0  999.06   67.12  995.04   125.1  989.95   143.4  989.04  152.56  989.98
  158.66  990.09  161.71  989.76  164.76  988.67  170.86  987.32  183.07  986.22
  198.32  986.05  241.04  984.68  265.45  982.69   274.6  980.59  279.09  979.84
  281.34  979.94  283.94  980.59  286.55  980.94  303.98  981.55  337.56   981.4
  361.98  982.07  365.03  982.46  374.19  985.04   386.4  986.96  416.92     990
  441.34  991.33  447.45   992.1  453.55   993.5  468.82  995.96  496.29  998.83
#Mann= 3 , 0 , 0
       0     .09       0   274.6     .04       0  283.94     .09       0
Bank Sta=274.6,283.94
XS Rating Curve= 0 ,0
Exp/Cntr=0.3,0.1

Type RM Length L Ch R = 1 ,15544.8 ,108.61,91.44,43.32
XS GIS Cut Line= 6
     641230.3686    4338619.0691     641102.1974    4338787.8146
     641026.6852    4338809.4152     641020.1764    4338805.9227
     641002.0789    4338788.6189     640873.7095     4338902.703
#Sta/Elev= 30
       0  998.96   61.42   995.7   89.06  992.75    95.2  992.47   116.7  989.97
  132.06  988.96   138.2  988.65  141.27  988.78  147.41  989.88  153.55  989.85
  165.84  987.25  175.05  986.32  214.92  985.06  260.24  982.39   284.4  982.21
  295.37  981.59  302.89  980.38  305.65   979.8  308.41  980.26  316.34   983.1
   318.6  982.93  323.13  981.59   335.4  983.65  341.53  984.19  384.47  984.63
  421.27  988.87  458.07  993.64  476.47  995.38   482.6  996.31  494.87  999.26
#Mann= 3 , 0 , 0
       0     .09       0  302.89     .04       0  308.41     .09       0
Bank Sta=302.89,308.41
XS Rating Curve= 0 ,0
Exp/Cntr=0.3,0.1

Type RM Length L Ch R = 1 ,15453.36,87.32,91.44,83.11
XS GIS Cut Line= 6
     641159.6718    4338578.9582     641047.0714    4338749.5325
      641042.483    4338758.6596     641026.0788    4338773.4763
     640975.2787     4338794.643     640863.3379    4338895.4005
#Sta/Elev= 30
       0  999.14   21.51   997.7   49.16  994.24   67.59  991.35   98.31  989.43
  116.75  987.45  122.89   987.1  135.18   988.6  141.32  988.62  150.54  986.41
  153.61   986.1  178.19  985.12  196.63  981.37  199.22  980.44  201.81  979.77
  207.43  980.42  217.38  983.13   231.2  984.21  236.72  984.17   245.9   982.9
  248.95  981.34  252.01  980.66  261.18  980.27  273.41  980.69  294.83  984.39
  328.64  984.67  359.38  988.38  383.97  990.78  417.78  995.22  442.37  999.16
#Mann= 3 , 0 , 0
       0     .09       0  199.22     .04       0  207.43     .09       0
Bank Sta=199.22,207.43
XS Rating Curve= 0 ,0
Exp/Cntr=0.3,0.1

Type RM Length L Ch R = 1 ,15361.92,97.44,91.44,83.3
XS GIS Cut Line= 5
     641120.5134    4338548.2665       640988.62    4338719.8564
       640975.99    4338755.9227     640963.9848     4338767.731
     640837.9378    4338876.3505
#Sta/Elev= 30
       0  998.84    9.14  998.08   30.48  994.98   91.45  989.62  103.64  989.21
  124.98  987.33  143.27   987.6  152.41  985.19  155.46  984.87   164.6  984.98
  173.75  985.89  179.84  985.76  201.18  983.45   222.3  982.92  242.88  981.54
  257.44  979.45  263.06  978.75  268.67  978.98  271.48  979.56   274.5  980.47
  280.55  983.57  283.58  984.03  307.78  984.59  341.06  987.31  356.18  987.57
  368.29  989.95  386.44  991.34  404.59  993.84  425.77  995.91  437.87  999.27
#Mann= 3 , 0 , 0
       0     .09       0  257.44     .04       0  271.48     .09       0
Bank Sta=257.44,271.48
XS Rating Curve= 0 ,0
Exp/Cntr=0.3,0.1

Type RM Length L Ch R = 1 ,15270.48,59.46,67.97,76.41
XS GIS Cut Line= 6
     641057.0132    4338513.3414     640908.4387    4338684.3913
      640895.574    4338717.8112     640895.1378    4338725.0809
     640890.1556    4338752.2024     640814.6544    4338849.8921
#Sta/Elev= 30
       0  998.88   30.62  996.36   70.42  990.99   76.54  990.62  119.41  985.99
  122.47  985.88  128.59  986.64  134.72  986.96  137.78  986.58   143.9  984.45
  146.96  984.17  217.38  982.35  229.55  982.15  247.46   982.4  253.42  981.86
  259.39  980.15  262.38  979.08  267.23  978.76  269.66  978.89  275.79  979.92
  284.98  981.06  291.11  982.52  297.24  983.52  354.45  988.24  381.55  992.67
  390.59  992.69   393.6  992.95  399.62  994.75  405.64  995.51   420.7  998.49
#Mann= 3 , 0 , 0
       0     .09       0  259.39     .04       0  275.79     .09       0
Bank Sta=259.39,275.79
XS Rating Curve= 0 ,0
Exp/Cntr=0.3,0.1

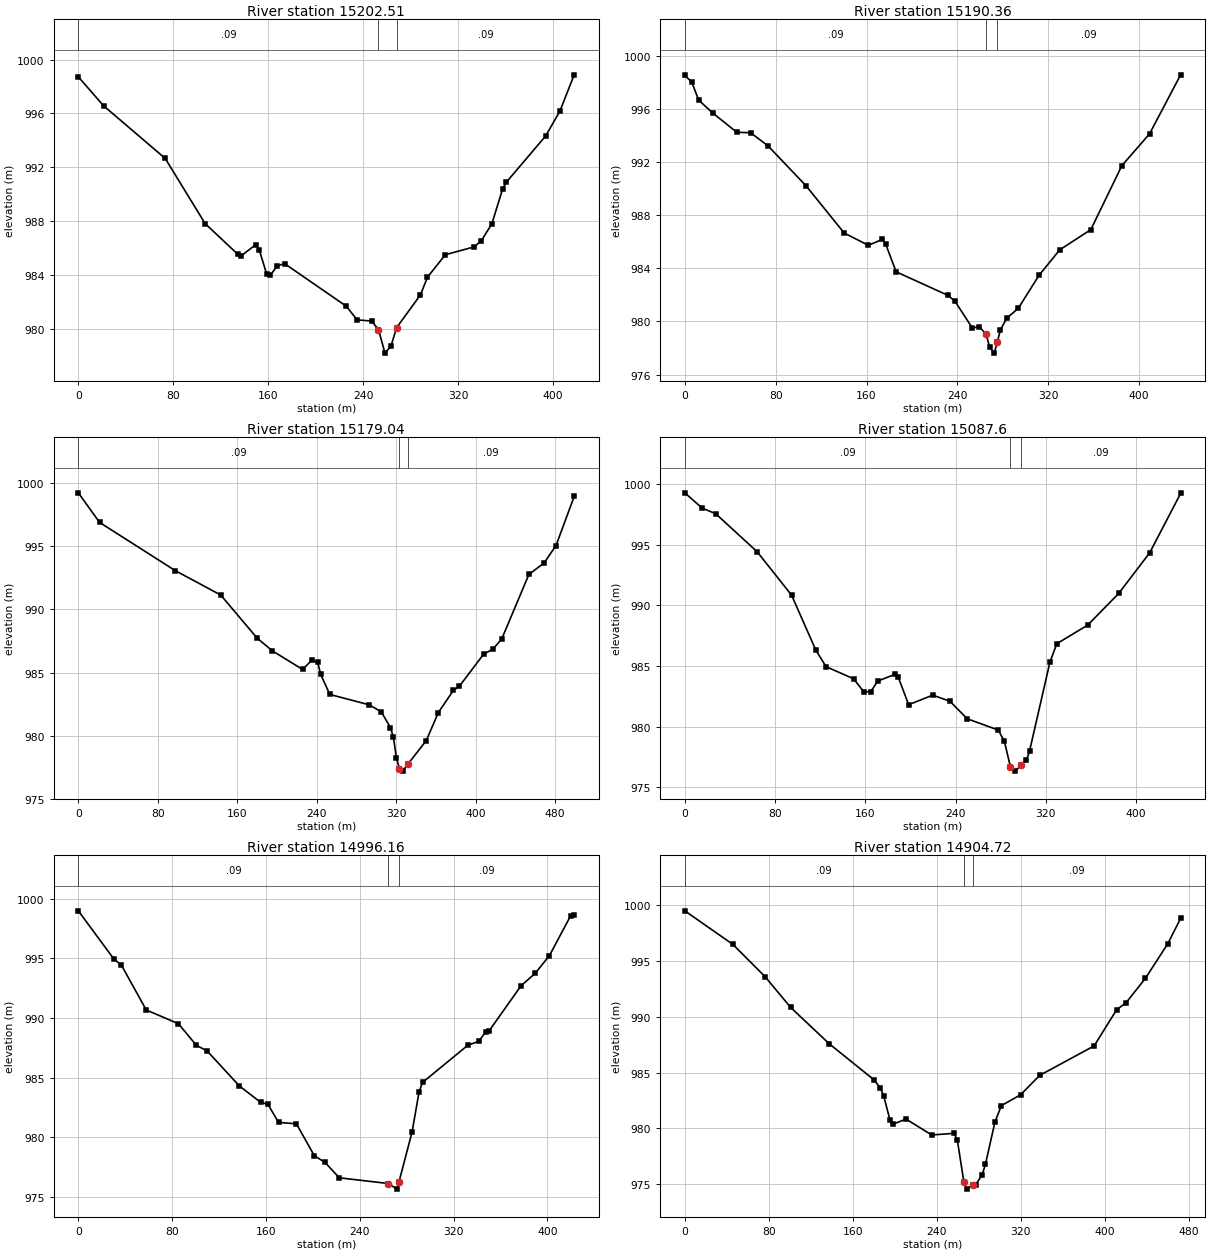
Type RM Length L Ch R = 1 ,15202.51,14.16,12.14,10.66
XS GIS Cut Line= 6
     641041.1382     4338490.058      640866.387    4338669.0048
     640855.7739    4338672.1673     640854.9272    4338674.1781
     640842.8622    4338677.3531     640767.0293    4338796.9753
#Sta/Elev= 30
       0  998.72   21.35  996.56   73.21  992.65  106.76  987.81  134.21  985.53
  137.26  985.41  149.46  986.24  152.51  985.81  158.61  984.07  161.66  983.95
  167.76  984.68  173.86  984.82  225.72  981.66  234.87  980.64  247.07  980.56
  252.85  979.92  258.31  978.17   263.4  978.71  268.15  980.07  288.09  982.49
  294.12  983.82  309.18  985.49  333.29  986.07  339.32  986.51  348.36  987.79
   357.4  990.38  360.41  990.87  393.56  994.31  405.61  996.16  417.67  998.87
#Mann= 3 , 0 , 0
       0     .09       0  252.85     .04       0  268.15     .09       0
Bank Sta=252.85,268.15
XS Rating Curve= 0 ,0
Exp/Cntr=0.3,0.1

Type RM Length L Ch R = 1 ,15190.36,11.92,11.32,11.3
XS GIS Cut Line= 6
     641044.3132     4338467.833     640854.0627     4338659.956
     640845.0668    4338664.7186      640843.691    4338667.1527
     640834.6952    4338672.0211      640756.446    4338791.6836
#Sta/Elev= 30
       0   998.5     6.1  998.01    12.2  996.65    24.4  995.69   45.76  994.23
   57.96  994.19   73.21  993.21  106.76   990.2  140.32  986.65  161.67  985.72
  173.87  986.17  176.92  985.81  186.07  983.73  231.83  981.95  237.93  981.51
  253.18   979.5  259.28   979.6  265.38  979.03  268.44  978.04   272.5  977.61
   275.2  978.47  277.89  979.35  283.38  980.23  293.61  980.98  311.86  983.46
  330.11  985.38  357.49   986.9  384.87  991.72  409.21  994.11  436.58  998.55
#Mann= 3 , 0 , 0
       0     .09       0  265.38     .04       0   275.2     .09       0
Bank Sta=265.38,275.2
XS Rating Curve= 0 ,0
Exp/Cntr=0.3,0.1

Type RM Length L Ch R = 1 ,15179.04,94.25,91.44,79.78
XS GIS Cut Line= 6
     641059.1299    4338399.0412     640846.4242    4338650.5558
     640842.0495    4338656.7792     640836.9852    4338658.4893
     640830.7939    4338663.4105      640746.921     4338786.392
#Sta/Elev= 30
       0  999.23   21.35  996.89    97.6  993.07  143.35  991.14  179.95  987.73
   195.2  986.73   225.7  985.25  234.85  985.96  240.95  985.81     244  984.85
  253.15  983.27   292.8  982.45     305  981.89  314.15  980.65   317.2  979.87
  320.25  978.23   323.3  977.38  326.35   977.2  331.93  977.77  350.26  979.62
  362.41  981.84   377.6   983.6  383.68  983.93  407.98  986.46  417.09  986.84
  426.21  987.66  453.55  992.77  468.74  993.67  480.89  995.06  499.12  998.94
#Mann= 3 , 0 , 0
       0     .09       0   323.3     .04       0  331.93     .09       0
Bank Sta=323.3,331.93
XS Rating Curve= 0 ,0
Exp/Cntr=0.3,0.1

Type RM Length L Ch R = 1 ,15087.6 ,84.47,91.44,97
XS GIS Cut Line= 6
      640871.487      4338362.07      640756.526     4338615.033
     640758.8271    4338625.6522     640757.8252    4338627.2162
     640759.7796     4338644.861     640698.9784    4338761.0625
#Sta/Elev= 30
       0  999.29   15.27  998.04   27.48  997.56   64.12  994.43   94.66  990.85
  116.03  986.34  125.19  984.95  149.62  983.95  158.78  982.87  164.88  982.89
  170.99  983.76  186.26  984.31  189.31  984.06  198.47  981.81  219.85   982.6
  235.11  982.09  250.38  980.65  277.86  979.72  283.29  978.81  288.73  976.67
  292.96  976.33   298.5  976.86  302.86  977.21  305.65  977.99  323.69  985.31
  329.79  986.84  357.24  988.38  384.69  990.99  412.14  994.34  439.59  999.24
#Mann= 3 , 0 , 0
       0     .09       0  288.73     .04       0   298.5     .09       0
Bank Sta=288.73,298.5
XS Rating Curve= 0 ,0
Exp/Cntr=0.3,0.1

Type RM Length L Ch R = 1 ,14996.16,97.23,91.44,87.97
XS GIS Cut Line= 6
     640811.1619     4338365.245     640687.4485    4338596.3401
      640676.662    4338603.6569     640675.2777    4338606.7118
     640640.6311    4338634.9502     640596.3198    4338724.0207
#Sta/Elev= 30
       0  998.99   30.48  994.92   36.58  994.46   57.91  990.67   85.34  989.52
  100.58  987.71  109.73  987.24  137.16  984.31  155.45  982.92  161.54  982.77
  170.69  981.24  185.93  981.12  201.17  978.45  210.31  977.88   222.5  976.59
  264.37  976.11  271.51  975.64  273.35  976.24  284.51  980.42  290.46  983.77
  293.44  984.59  332.29  987.73  341.33  988.03  347.36  988.84  350.37  988.94
  377.51  992.71  389.56  993.75  401.62  995.23  419.71  998.57  422.73  998.62
#Mann= 3 , 0 , 0
       0     .09       0  264.37     .04       0  273.35     .09       0
Bank Sta=264.37,273.35
XS Rating Curve= 0 ,0
Exp/Cntr=0.3,0.1

Type RM Length L Ch R = 1 ,14904.72,92.78,91.44,94.47
XS GIS Cut Line= 6
     640730.7284    4338279.5198      640639.262    4338529.1122
     640637.8932    4338534.0533     640636.7131     4338537.128
     640615.8851    4338600.7109     640548.6947    4338713.4374
#Sta/Elev= 30
       0  999.49   45.83  996.48   76.39   993.6  100.83  990.84   137.5  987.59
  180.27  984.35  186.38  983.61  189.44  982.93  195.55  980.72   198.6  980.39
  210.83  980.83  235.27  979.41  256.66  979.56  259.71  978.92  265.82  975.24
  268.39  974.56  274.24  974.92  277.29  974.97  283.37  975.86  286.41  976.78
  295.53  980.59  301.62  982.04  319.86  983.01  338.11  984.75  389.98  987.39
  411.35  990.62   420.5  991.27  438.81  993.44  460.18  996.55  472.38  998.81
#Mann= 3 , 0 , 0
       0     .09       0  265.82     .04       0  274.24     .09       0
Bank Sta=265.82,274.24
XS Rating Curve= 0 ,0
Exp/Cntr=0.3,0.1

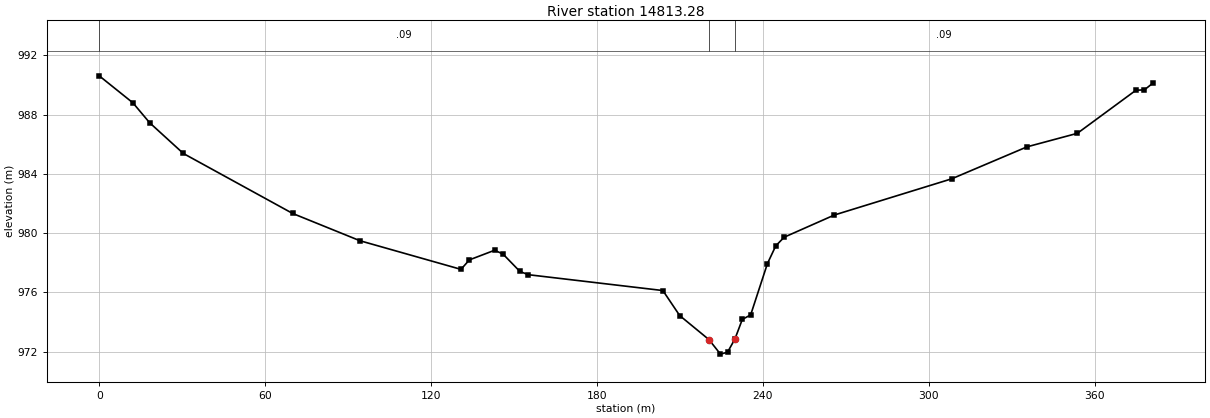
Type RM Length L Ch R = 1 ,14813.28,91.7,91.44,97.55
XS GIS Cut Line= 5
     640600.5532    4338295.3949     640550.0817    4338511.7168
     640548.1924    4338516.4732     640545.8672    4338521.2833
     640484.1363    4338656.2873
#Sta/Elev= 30
       0  990.61   12.17  988.79   18.26  987.44   30.43  985.37   69.99  981.32
   94.33  979.48  130.84  977.55  133.89  978.19  143.02  978.84  146.06  978.58
  152.15  977.41  155.19  977.19  203.87  976.12  209.96  974.43  220.53  972.81
  224.69  971.83  227.25  971.96  229.92  972.85  232.59  974.17  235.62  974.48
  241.68  977.94  244.71  979.14  247.74  979.72  265.92  981.22  308.33  983.66
   335.6  985.82  353.77  986.73  374.98  989.64  378.01  989.66  381.04  990.11
#Mann= 3 , 0 , 0
       0     .09       0  220.53     .04       0  229.92     .09       0
Bank Sta=220.53,229.92
XS Rating Curve= 0 ,0
Exp/Cntr=0.3,0.1