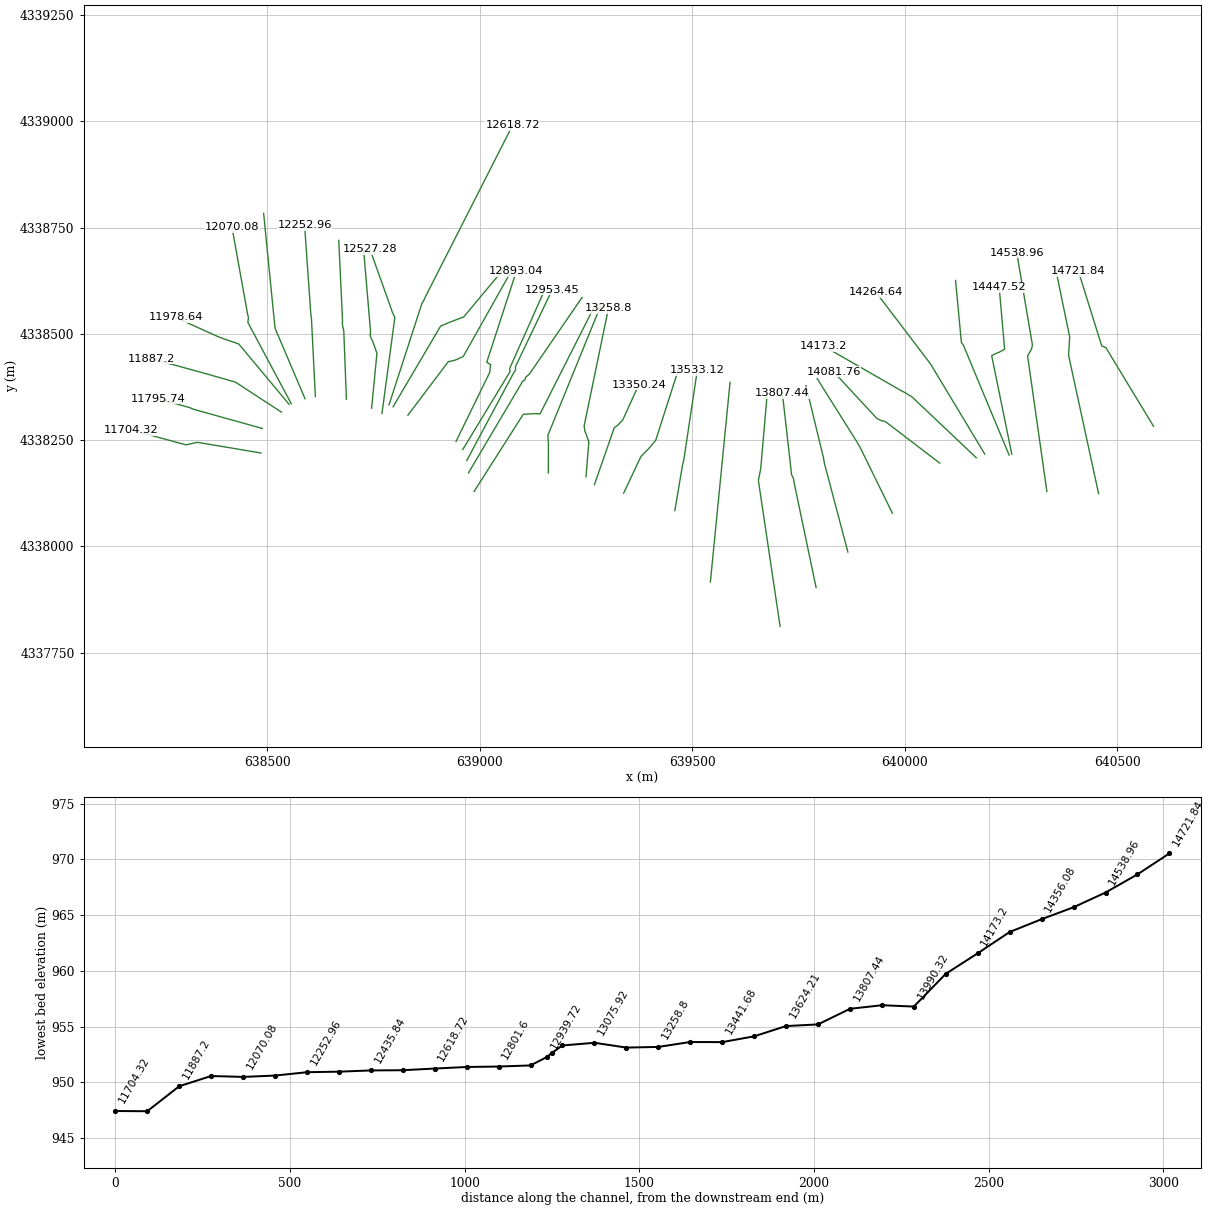
HEC-RAS study BeaverCreek.prj: BeaverCreek

--- BeaverCreek.g01 (geometry) --- (continued)

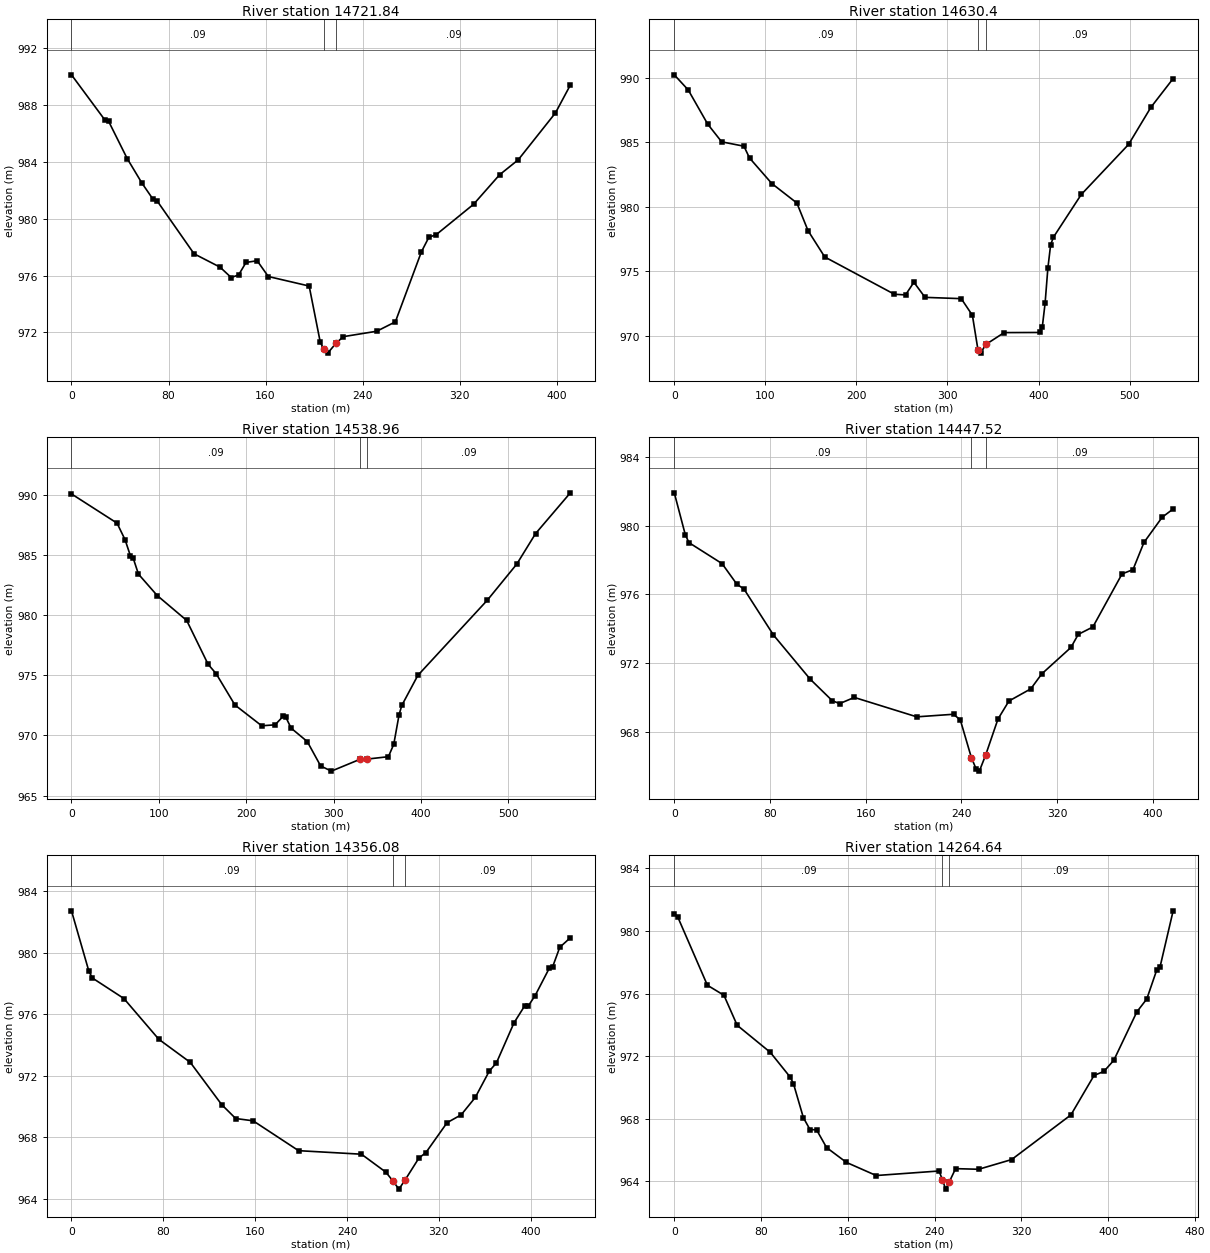
Type RM Length L Ch R = 1 ,14721.84,93.16,91.44,81.4
XS GIS Cut Line= 6
      640585.053    4338282.6287     640475.5766    4338463.3305
     640474.9971    4338465.0542      640473.803    4338467.0365
     640463.1454    4338471.9133     640408.3109    4338647.7544
#Sta/Elev= 30
       0  990.12   27.56  986.94   30.62  986.85   45.93  984.23   58.18  982.49
   67.36  981.35   70.43  981.27  101.05  977.53  122.48  976.59  131.67  975.86
  137.79  976.04  143.91  976.92   153.1  977.04  162.29  975.93  195.97  975.26
  205.15   971.3  208.22   970.8  211.28  970.54  218.34  971.26   224.2   971.7
  251.69  972.08  267.04  972.74  288.53  977.67  294.67  978.69  300.81  978.88
  331.51  981.01     353  983.09  368.34  984.14  399.04  987.44  411.32   989.4
#Mann= 3 , 0 , 0
       0     .09       0  208.22     .04       0  218.34     .09       0
Bank Sta=208.22,218.34
XS Rating Curve= 0 ,0
Exp/Cntr=0.3,0.1

Type RM Length L Ch R = 1 ,14630.4 ,94.97,91.44,89.32
XS GIS Cut Line= 4
      640455.936    4338123.8784     640385.2085    4338449.7609
     640387.8262    4338492.7977     640353.2775    4338660.4544
#Sta/Elev= 30
       0  990.22    15.3  989.05   36.71   986.4   52.01  985.03   76.48  984.69
    82.6  983.78  107.08   981.8  134.61  980.29  146.85  978.15  165.21  976.11
  241.69  973.22  253.93  973.17   263.1  974.15  275.34  972.98  315.11  972.88
  327.35  971.59  333.47  968.91  336.34  968.66  342.09  969.33  362.21  970.25
  401.04  970.26   404.1  970.69  407.15  972.51  410.21  975.24  413.27  977.06
  416.32  977.64  446.89  980.95  498.86  984.83  523.31   987.7  547.77  989.93
#Mann= 3 , 0 , 0
       0     .09       0  333.47     .04       0  342.09     .09       0
Bank Sta=333.47,342.09
XS Rating Curve= 0 ,0
Exp/Cntr=0.3,0.1

Type RM Length L Ch R = 1 ,14538.96,102.42,91.44,83.3
XS GIS Cut Line= 5
     640334.2275    4338129.1701     640288.8878    4338447.9459
     640298.1894    4338464.4354     640300.2499    4338473.7804
      640263.319    4338691.1462
#Sta/Elev= 30
       0  990.08   52.13  987.65   61.33  986.27   67.46  984.93   70.53  984.76
   76.66  983.41   98.13  981.63  131.86  979.56  156.39  975.91  165.59  975.13
  187.06  972.53  217.72   970.8  233.06  970.88  242.25  971.59  245.32  971.51
  251.45   970.6  269.85  969.49  285.19  967.46  297.45  967.03   330.1  968.01
  338.21  968.03  362.73  968.23  368.86  969.26  374.98  971.73  378.05  972.49
  396.42  974.99  476.04  981.25  509.72  984.25  531.16  986.78  570.97  990.17
#Mann= 3 , 0 , 0
       0     .09       0   330.1     .04       0  338.21     .09       0
Bank Sta=330.1,338.21
XS Rating Curve= 0 ,0
Exp/Cntr=0.3,0.1

Type RM Length L Ch R = 1 ,14447.52,79.87,91.44,101.21
XS GIS Cut Line= 6
     640251.6773    4338217.0119     640204.3592    4338448.6722
     640213.6193    4338453.4462     640221.1209    4338456.4084
     640234.8117    4338463.8089     640222.0439    4338609.6543
#Sta/Elev= 30
       0  981.91    9.21  979.47   12.28  979.01   39.92  977.79    52.2   976.6
   58.34   976.3   82.91  973.63  113.62  971.06  132.04  969.81  138.18  969.64
  150.46     970  202.67  968.87  233.37  969.02  239.05  968.69  248.27   966.5
  252.43  965.81  254.95  965.71  260.14  966.63  270.51  968.74  279.66  969.79
  297.96   970.5  307.11  971.37  331.51  972.91  337.61  973.67  349.81   974.1
  374.21  977.19  383.36  977.44  392.51  979.02  407.76  980.49  416.91  980.97
#Mann= 3 , 0 , 0
       0     .09       0  248.27     .04       0  260.14     .09       0
Bank Sta=248.27,260.14
XS Rating Curve= 0 ,0
Exp/Cntr=0.3,0.1

Type RM Length L Ch R = 1 ,14356.08,90.65,91.44,91.85
XS GIS Cut Line= 5
     640245.3273    4338214.8952      640137.815    4338473.3756
      640136.176    4338476.0963     640133.1718    4338478.9508
     640119.3854    4338625.5294
#Sta/Elev= 30
       0  982.73   15.21  978.79   18.26  978.36   45.64  977.03   76.07  974.38
  103.46  972.88  130.85  970.13  143.02  969.23  158.23  969.08  197.79  967.14
  252.56  966.91  273.86  965.74  279.95  965.17   285.2  964.64  290.34  965.21
   302.6  966.66  308.74  967.02  327.14  968.96  339.41  969.47  351.68   970.6
  363.95  972.32  370.08  972.84  385.42  975.45  394.62  976.54  397.69  976.53
  403.82  977.22  416.09  978.99  419.16  979.11  425.29  980.36  434.49  980.98
#Mann= 3 , 0 , 0
       0     .09       0  279.95     .04       0  290.34     .09       0
Bank Sta=279.95,290.34
XS Rating Curve= 0 ,0
Exp/Cntr=0.3,0.1

Type RM Length L Ch R = 1 ,14264.64,89.17,91.44,95.22
XS GIS Cut Line= 3
     640188.1772    4338217.0119     640060.8059    4338428.7486
       639932.06    4338598.0127
#Sta/Elev= 30
       0  981.07    3.05  980.92   30.51  976.53   45.76  975.89   57.96  973.97
   88.47  972.24  106.77  970.66  109.82  970.24  118.97  968.06  125.07   967.3
  131.17  967.28  140.33  966.15  158.63   965.2  186.08  964.36  244.04  964.65
  247.09  964.09  250.13  963.49  253.43  963.95  259.25   964.8  280.51  964.76
  310.89  965.38  365.58  968.24  386.85  970.76  395.96  971.02  405.07  971.73
  426.34  974.83  435.45  975.65  444.57  977.49  447.61  977.68  459.76  981.29
#Mann= 3 , 0 , 0
       0     .09       0  247.09     .04       0  253.43     .09       0
Bank Sta=247.09,253.43
XS Rating Curve= 0 ,0
Exp/Cntr=0.3,0.1

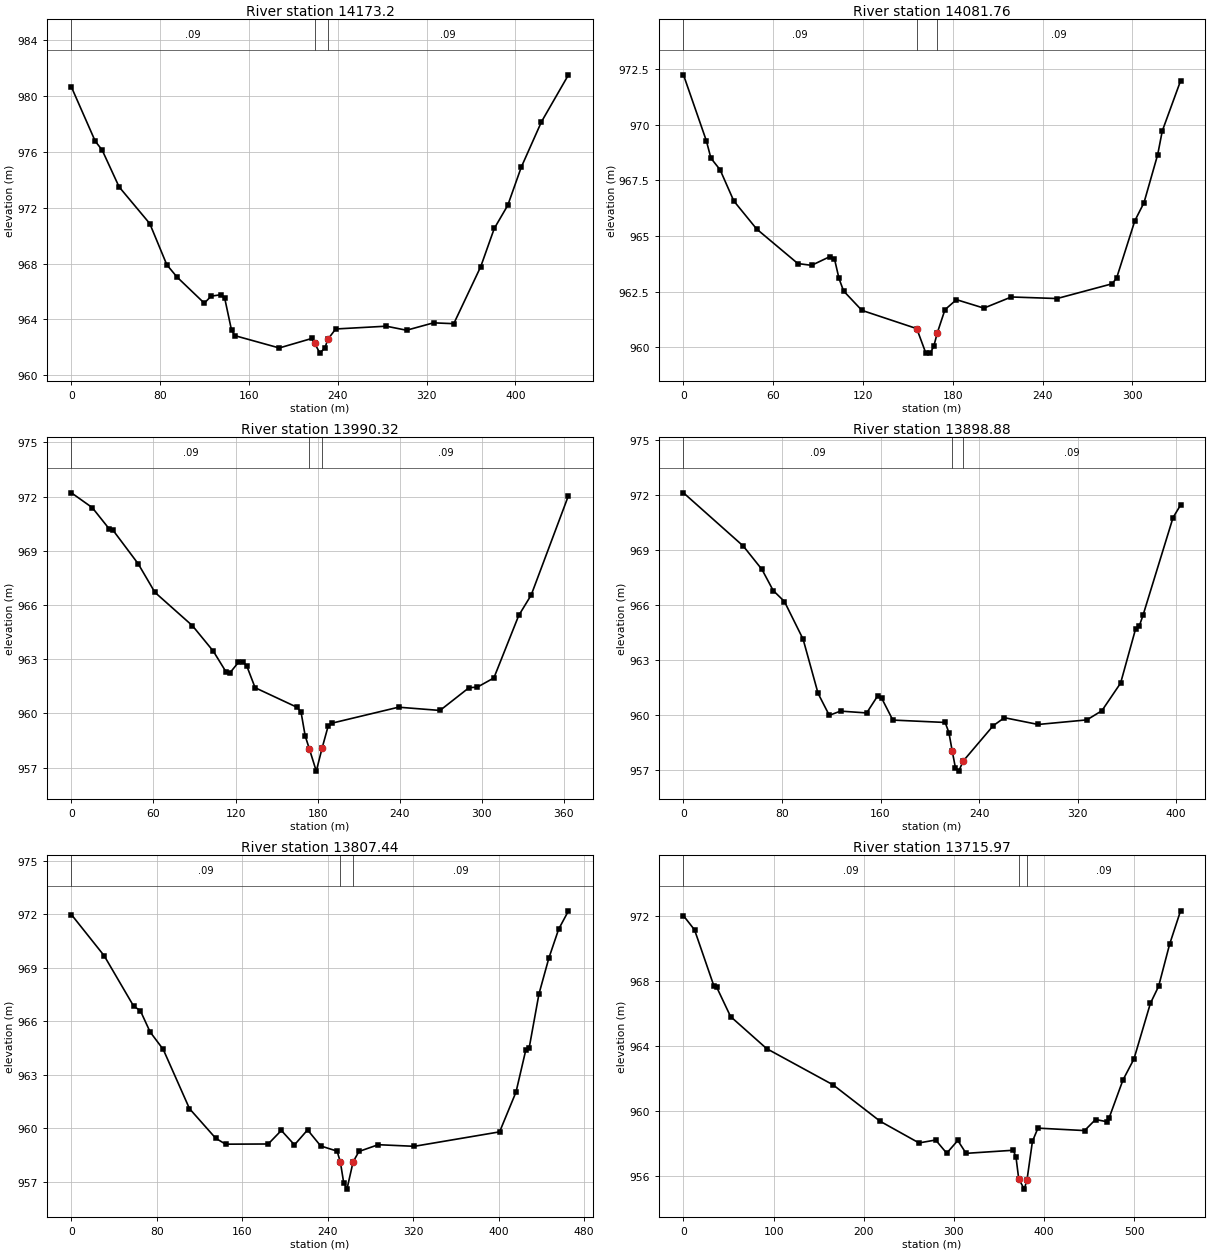
Type RM Length L Ch R = 1 ,14173.2 ,88.72,91.44,89.92
XS GIS Cut Line= 6
     640168.0688    4338208.5452     640016.5062    4338352.0533
     640005.3269    4338358.5612     640001.8735    4338361.1518
      639993.752    4338365.0426     639809.2931    4338471.0124
#Sta/Elev= 30
       0  980.65   21.49  976.76   27.63  976.14   42.97  973.49    70.6  970.86
   85.95  967.91   95.15  967.03  119.71  965.16  125.85  965.66  135.06  965.77
  138.13   965.5  144.27  963.21  147.33  962.83  187.24  961.95  216.49  962.63
  219.07  962.29  223.82  961.58  228.44  961.97   230.9  962.56  238.04  963.31
  283.63  963.51  301.86  963.22  326.18  963.75  344.41  963.69  368.72  967.78
  380.88  970.51  393.04  972.17  405.19   974.9  423.43  978.16  447.74  981.52
#Mann= 3 , 0 , 0
       0     .09       0  219.07     .04       0   230.9     .09       0
Bank Sta=219.07,230.9
XS Rating Curve= 0 ,0
Exp/Cntr=0.3,0.1

Type RM Length L Ch R = 1 ,14081.76,93.38,91.44,79.96
XS GIS Cut Line= 6
     640082.3436    4338195.8452     639958.4421    4338290.4799
     639950.6235    4338294.9856     639945.9236    4338295.2583
     639934.4234    4338300.8612     639832.5765    4338410.6873
#Sta/Elev= 30
       0  972.23   15.29  969.27   18.34  968.49   24.46  967.97   33.63  966.57
   48.91  965.31   76.43  963.76    85.6  963.68   97.82  964.07  100.88  963.98
  103.94  963.09     107  962.53  119.22  961.66  155.91  960.84  161.92  959.75
  164.93  959.74  167.29  960.05  169.64  960.65  174.76  961.69  182.43  962.14
  200.77  961.76  219.11  962.26  249.68  962.19  286.36  962.85  289.42   963.1
  301.65  965.68  307.76  966.49  316.93  968.65  319.99  969.71  332.21  971.96
#Mann= 3 , 0 , 0
       0     .09       0  155.91     .04       0  169.64     .09       0
Bank Sta=155.91,169.64
XS Rating Curve= 0 ,0
Exp/Cntr=0.3,0.1

Type RM Length L Ch R = 1 ,13990.32,93.04,91.44,89.96
XS GIS Cut Line= 5
     639970.8127    4338078.0172     639894.2442    4338234.1792
     639890.2115    4338240.6074     639888.8613    4338243.3628
     639793.8061    4338394.7241
#Sta/Elev= 30
       0  972.21   15.26  971.39   27.46  970.23   30.51  970.13   48.82  968.28
   61.03   966.7   88.49  964.85  103.74  963.44   112.9  962.31  115.95  962.25
  122.05  962.82   125.1  962.87  128.15  962.63  134.26  961.42  164.77  960.34
  167.82  960.08  170.87  958.75  173.92  958.03  178.98   956.8  183.32   958.1
  187.61  959.28  190.64  959.46  239.11  960.34   269.4  960.16  290.61  961.42
  296.67  961.45  308.79  961.96  326.96  965.42  336.05  966.55  363.31  972.06
#Mann= 3 , 0 , 0
       0     .09       0  173.92     .04       0  183.32     .09       0
Bank Sta=173.92,183.32
XS Rating Curve= 0 ,0
Exp/Cntr=0.3,0.1

Type RM Length L Ch R = 1 ,13898.88,89.85,91.44,93.09
XS GIS Cut Line= 5
     639866.0375    4337986.7357     639810.9917    4338195.1151
     639809.5172    4338202.9481     639809.1361    4338206.5398
       639767.48    4338378.0553
#Sta/Elev= 30
       0  972.13   48.57  969.22   63.75  967.94   72.85  966.79   81.96  966.19
   97.14  964.13  109.28  961.17  118.39  959.97   127.5   960.2  148.74   960.1
  157.85  961.05  160.89  960.91  169.99  959.71  212.49  959.58  215.53  959.02
  218.18  958.03  220.84  957.09   223.5  956.92  227.11  957.47  251.45   959.4
  260.58  959.84  287.97  959.47  327.53  959.72  339.71  960.22  354.92  961.73
  367.09  964.69  370.14  964.86  373.18  965.45  397.52  970.78  403.61  971.46
#Mann= 3 , 0 , 0
       0     .09       0  218.18     .04       0  227.11     .09       0
Bank Sta=218.18,227.11
XS Rating Curve= 0 ,0
Exp/Cntr=0.3,0.1

Type RM Length L Ch R = 1 ,13807.44,88.3,91.47,84.99
XS GIS Cut Line= 5
     639791.2926    4337903.1272     639738.9851    4338152.6666
     639738.3747    4338158.7704     639733.6519     4338168.564
     639711.9174    4338360.8573
#Sta/Elev= 30
       0  971.99   30.72  969.68   58.36  966.85   64.51  966.61   73.72  965.41
   86.01  964.43  110.59  961.11  135.16  959.45  144.38  959.12  184.31  959.13
   196.6  959.89  208.89  959.08  221.17  959.92  233.46  959.02  248.82  958.73
  251.89  958.11  254.96  956.97  258.03   956.6  263.82  958.13  269.25  958.71
  287.33  959.09  321.12     959  400.98  959.81  416.34  962.04  425.56  964.41
  428.63   964.5  437.84  967.54  447.06  969.54  456.27  971.17  465.49   972.2
#Mann= 3 , 0 , 0
       0     .09       0  251.89     .04       0  263.82     .09       0
Bank Sta=251.89,263.82
XS Rating Curve= 0 ,0
Exp/Cntr=0.3,0.1

Type RM Length L Ch R = 1 ,13715.97,90.97,91.76,91.81
XS GIS Cut Line= 4
     639706.6257    4337811.8458     639655.4894    4338155.3678
     639661.0547    4338182.4062     639676.1986    4338358.2115
#Sta/Elev= 30
       0  972.01   12.29  971.14   33.81  967.68   36.88  967.61   52.25  965.81
   92.21  963.84  165.97  961.61  218.22  959.37  261.25  958.04  279.69  958.22
  291.98  957.41  304.28  958.19   313.5   957.4  365.71  957.59  368.78  957.19
  371.84  955.84  377.95   955.2     381  955.75  387.08  958.14  393.17  958.95
  444.89   958.8  457.06  959.48  469.23  959.35  472.27   959.6  487.48  961.91
  499.65   963.2   517.9  966.62  527.03  967.67   539.2  970.25  551.37  972.31
#Mann= 3 , 0 , 0
       0     .09       0  371.84     .04       0     381     .09       0
Bank Sta=371.84,381
XS Rating Curve= 0 ,0
Exp/Cntr=0.3,0.1

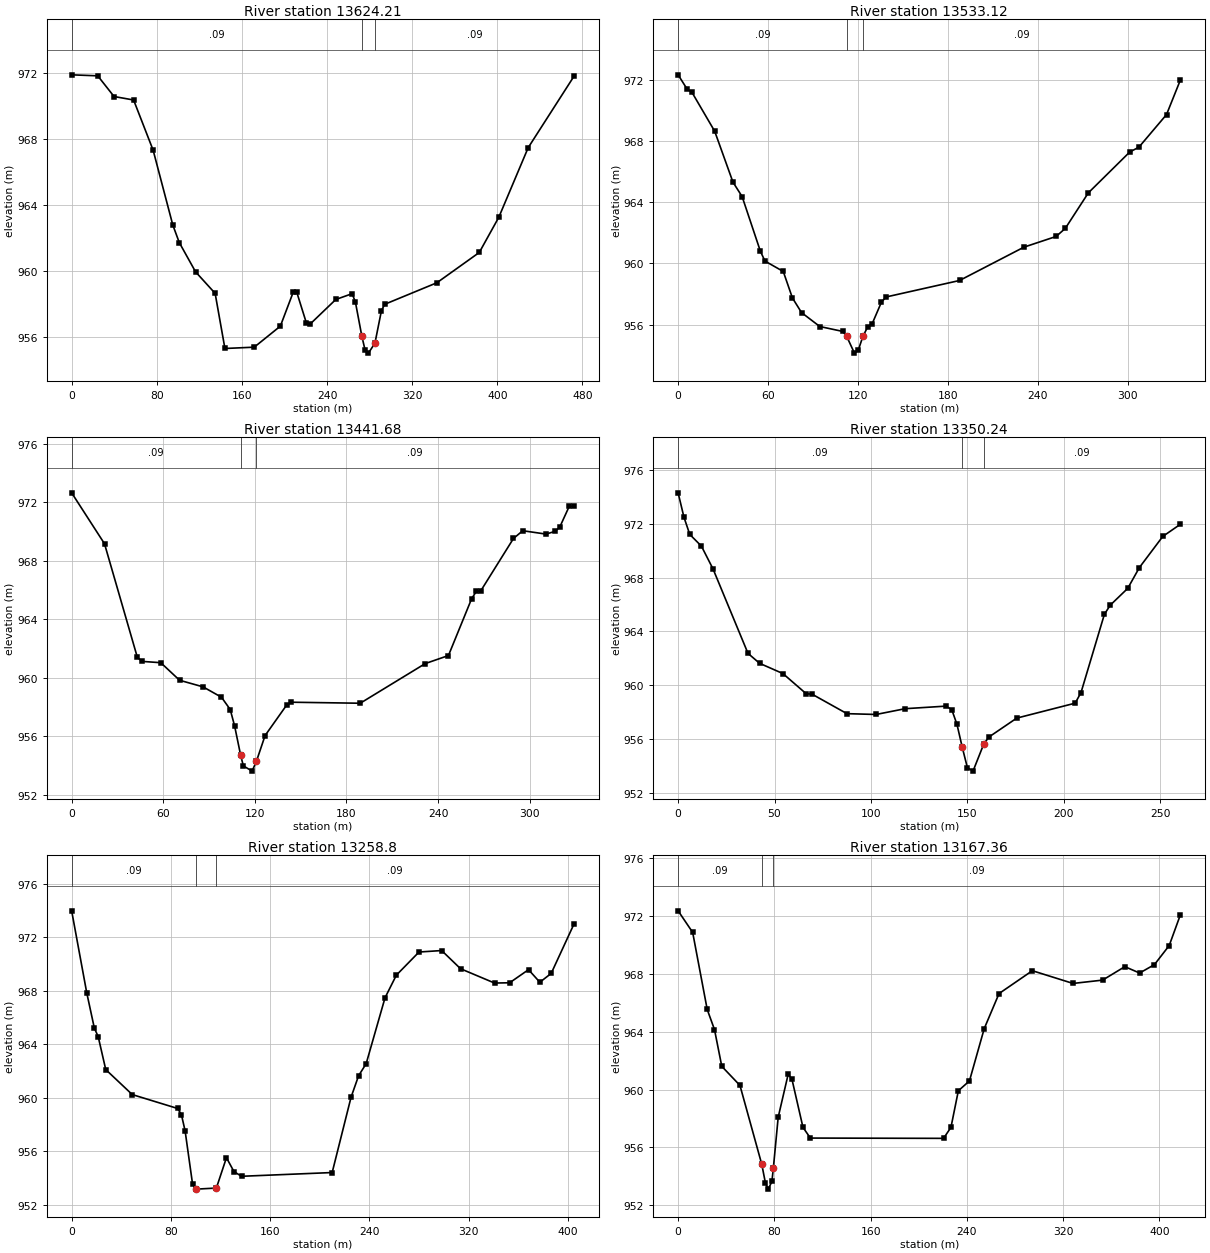
Type RM Length L Ch R = 1 ,13624.21,92.48,91.09,90.17
XS GIS Cut Line= 2
     639542.5837    4337916.3564     639588.8859    4338385.9928
#Sta/Elev= 30
       0  971.86   24.51   971.8   39.84  970.55   58.22  970.34   76.61   967.3
      95   962.8  101.12  961.73  116.45  959.96  134.83  958.66  144.03  955.33
   171.6  955.41  196.12  956.68  208.38  958.76  211.44  958.75  220.63  956.86
   223.7  956.78  248.21  958.29  263.54  958.64   266.6  958.15  272.73  956.06
  275.79  955.22  278.86  955.05  284.99  955.65  291.12  957.62  294.18     958
  343.21   959.3  383.05  961.13  401.43  963.26  429.01  967.46  471.91  971.76
#Mann= 3 , 0 , 0
       0     .09       0  272.73     .04       0  284.99     .09       0
Bank Sta=272.73,284.99
XS Rating Curve= 0 ,0
Exp/Cntr=0.3,0.1

Type RM Length L Ch R = 1 ,13533.12,96.3,91.44,86.85
XS GIS Cut Line= 4
     639459.0193    4338084.2569     639477.2941    4338192.5054
     639479.9536    4338202.6117     639511.9361    4338414.9868
#Sta/Elev= 30
       0  972.33     6.1  971.38    9.15   971.2    24.4  968.64   36.59  965.31
   42.69  964.37   54.89  960.79   57.94  960.15   70.14  959.47   76.24  957.74
   82.34  956.78   94.53  955.87  109.78  955.55  112.39  955.24  117.62  954.13
  120.23  954.34   123.3  955.23  126.37  955.83  129.44  956.05  135.57  957.45
  138.64   957.8  187.73  958.88  230.68  961.06  252.16  961.76   258.3  962.29
  273.64  964.61  301.25  967.28  307.39   967.6   325.8  969.73     335  971.98
#Mann= 3 , 0 , 0
       0     .09       0  112.39     .04       0   123.3     .09       0
Bank Sta=112.39,123.3
XS Rating Curve= 0 ,0
Exp/Cntr=0.3,0.1

Type RM Length L Ch R = 1 ,13441.68,93.04,91.44,90.79
XS GIS Cut Line= 5
     639338.6337    4338125.2674     639379.2371     4338211.475
     639397.3505    4338229.8187      639413.811    4338249.1293
     639469.6027    4338422.9243
#Sta/Elev= 30
       0  972.63   21.52  969.15   43.03  961.39   46.11  961.11    58.4  961.02
    70.7  959.82   86.07  959.37   98.16  958.66  103.88  957.82  106.75   956.7
  110.74  954.68  112.48  953.97  118.21  953.61  121.07  954.29  126.71  956.04
  140.81  958.12  143.63  958.32  189.04  958.25  231.63  960.96  246.84  961.51
  262.05   965.4  265.09  965.89  268.13  965.95  289.43  969.51  295.51  970.04
  310.72  969.81  316.81     970  319.85  970.31  325.93   971.7  328.98   971.7
#Mann= 3 , 0 , 0
       0     .09       0  110.74     .04       0  121.07     .09       0
Bank Sta=110.74,121.07
XS Rating Curve= 0 ,0
Exp/Cntr=0.3,0.1

Type RM Length L Ch R = 1 ,13350.24,67.78,91.44,96.42
XS GIS Cut Line= 6
     639269.8419    4338145.1112     639316.5143    4338279.1424
       639323.14    4338283.7908     639327.4181    4338287.7955
     639336.6862    4338297.8908     639374.3525    4338380.5909
#Sta/Elev= 30
       0   974.3    3.02  972.49    6.04  971.21   12.08  970.34   18.12  968.64
   36.24  962.37   42.28  961.63   54.35  960.87   66.43  959.37   69.45  959.34
   87.57  957.89  102.67  957.83  117.77  958.26  138.91  958.45  141.92  958.19
  144.62   957.1  147.32  955.42  150.02  953.88  152.95  953.62  158.62  955.67
  161.36  956.17  175.64  957.56  205.93  958.67  208.96  959.46  221.08  965.27
  224.11  965.95  233.19   967.2  239.25  968.75  251.37  971.06  260.46  971.96
#Mann= 3 , 0 , 0
       0     .09       0  147.32     .04       0  158.62     .09       0
Bank Sta=147.32,158.62
XS Rating Curve= 0 ,0
Exp/Cntr=0.3,0.1

Type RM Length L Ch R = 1 ,13258.8 ,93.58,91.44,96.39
XS GIS Cut Line= 6
     639249.9981    4338163.6321     639256.7128    4338245.8059
      639250.809    4338262.8473     639247.4376    4338270.7236
     639245.6003     4338283.271     639302.9148    4338560.5079
#Sta/Elev= 30
       0  973.99   12.21  967.84   18.32  965.21   21.38  964.59   27.48  962.12
   48.86  960.25   85.45  959.21   88.46  958.76   91.47  957.53   97.48  953.55
  100.48  953.18  116.66  953.26  124.78  955.53  130.86  954.49  136.95  954.14
  210.01  954.42  225.23  960.05  231.32  961.66  237.41  962.56  252.63  967.49
  261.76  969.18  280.02  970.91  298.29  971.02  313.51  969.66   340.9  968.59
  353.08  968.61   368.3  969.59  377.43  968.65  386.57  969.31  404.83  972.98
#Mann= 3 , 0 , 0
       0     .09       0  100.48     .04       0  116.66     .09       0
Bank Sta=100.48,116.66
XS Rating Curve= 0 ,0
Exp/Cntr=0.3,0.1

Type RM Length L Ch R = 1 ,13167.36,98.72,91.44,72.64
XS GIS Cut Line= 6
     639161.3625    4338172.8925     639161.5934    4338245.4458
     639161.3276    4338247.7799      639160.658    4338250.7481
     639160.2883    4338261.1755      639284.394    4338565.7996
#Sta/Elev= 30
       0  972.36   12.09  970.87   24.18  965.54   30.23  964.15   36.28  961.61
   51.39  960.29   69.53  954.83   72.55  953.54    74.9  953.12   77.95  953.65
   79.18  954.61   83.16  958.09   91.45  961.06   94.53  960.74  103.75  957.39
   109.9  956.65  220.57  956.63  226.72  957.39  232.86  959.92  242.09   960.6
  254.38  964.22  266.68  966.64  294.35  968.22  328.16  967.34  352.76  967.57
   371.2   968.5   383.5  968.06   395.8  968.64  408.09  969.96  417.31  972.07
#Mann= 3 , 0 , 0
       0     .09       0   69.53     .04       0   79.18     .09       0
Bank Sta=69.53,79.18
XS Rating Curve= 0 ,0
Exp/Cntr=0.3,0.1

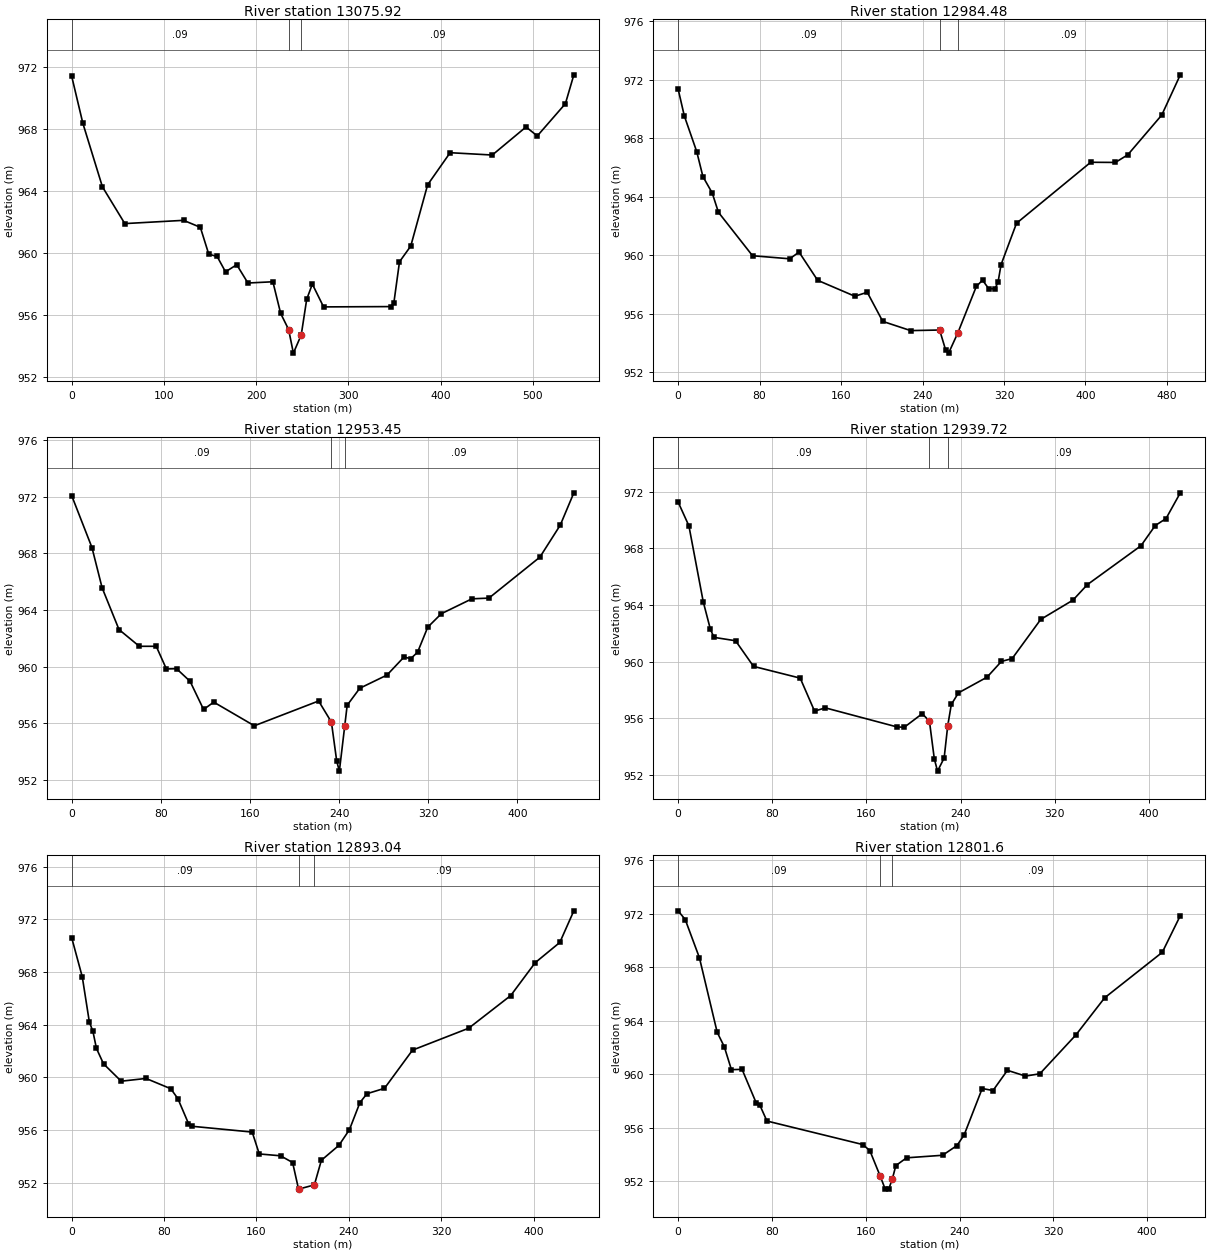
Type RM Length L Ch R = 1 ,13075.92,83.22,91.44,104.55
XS GIS Cut Line= 6
     638986.7371    4338129.2362      639102.426    4338310.7973
     639124.8594    4338311.8878     639129.9499    4338312.4231
     639141.7961    4338311.4323     639272.4877    4338569.7683
#Sta/Elev= 30
       0  971.41   12.13  968.37   33.35  964.27   57.61   961.9  121.29  962.11
  139.48  961.66  148.58  959.93  157.67  959.78  166.77  958.79   178.9  959.25
  191.03  958.07  218.09  958.15  226.52  956.11  235.16  955.07  240.31  953.55
  248.81  954.72  254.75  957.02  260.85     958  273.04  956.53  346.18  956.55
  349.23   956.8  355.32  959.44  367.51  960.45   385.8   964.4  410.18  966.47
  455.89  966.32  492.46  968.13  504.65  967.55  535.12  969.63  544.27  971.49
#Mann= 3 , 0 , 0
       0     .09       0  235.16     .04       0  248.81     .09       0
Bank Sta=235.16,248.81
XS Rating Curve= 0 ,0
Exp/Cntr=0.3,0.1

Type RM Length L Ch R = 1 ,12984.48,30.59,31.03,38.32
XS GIS Cut Line= 6
     638973.5079    4338172.8925     639100.6445    4338387.7471
     639106.3595    4338392.0334     639107.9349    4338397.6034
     639116.9606    4338405.5877     639240.7376    4338585.6434
#Sta/Elev= 30
       0  971.37    6.09  969.53   18.27  967.09   24.36  965.38   33.49  964.26
   39.58  962.94   73.07  959.97   109.6  959.76  118.74  960.22     137  958.29
  173.54   957.2  185.72  957.47  200.94  955.48  228.34  954.85   256.8  954.89
  262.58  953.55   265.6  953.31  274.64  954.69  292.84  957.87  298.91   958.3
  304.98  957.72  311.05  957.71  314.09  958.14  317.12  959.36  332.29  962.19
  405.13  966.36   429.4  966.35  441.54  966.87  474.92  969.59  493.13  972.34
#Mann= 3 , 0 , 0
       0     .09       0   256.8     .04       0  274.64     .09       0
Bank Sta=256.8,274.64
XS Rating Curve= 0 ,0
Exp/Cntr=0.3,0.1

Type RM Length L Ch R = 1 ,12953.45,10.42,13.73,12.13
XS GIS Cut Line= 6
     638969.5392    4338201.9968     639078.3365    4338405.4947
     639083.3835    4338413.5546     639084.4061    4338416.3852
     639083.9126    4338422.5505     639170.6229    4338604.1642
#Sta/Elev= 30
       0  972.08   18.22  968.41   27.33  965.57   42.51  962.62   60.73  961.44
   75.91  961.44   85.02  959.84   94.12  959.86  106.27  958.97  118.41  956.98
  127.52   957.5  163.96  955.83  221.65  957.58  233.13  956.09  237.89  953.34
  240.27  952.63  245.09  955.82  247.28  957.28  258.61  958.48  283.01  959.41
  298.25  960.68  304.35  960.57  310.45  961.02   319.6  962.79  331.79  963.74
  359.24  964.79  374.48  964.84  420.22  967.73  438.52  969.99  450.71  972.27
#Mann= 3 , 0 , 0
       0     .09       0  233.13     .04       0  245.09     .09       0
Bank Sta=233.13,245.09
XS Rating Curve= 0 ,0
Exp/Cntr=0.3,0.1

Type RM Length L Ch R = 1 ,12939.72,50.34,46.68,57.82
XS GIS Cut Line= 6
     638960.1553    4338227.9083     639070.9282    4338410.3895
     639070.9282     4338414.517     639070.4519    4338417.2158
     639070.9282    4338419.7558     639153.8307    4338605.7341
#Sta/Elev= 30
       0  971.28    9.15   969.6   21.35  964.23   27.45  962.28    30.5  961.72
   48.79  961.48   64.04  959.67  103.69  958.84  115.88  956.51  125.03  956.74
  186.02  955.39  192.12  955.37  207.37  956.33  213.47  955.79   217.6  953.14
  220.34  952.27  225.96   953.2     229  955.48  232.04  956.98  238.12   957.8
  262.43  958.91  274.59  960.02  283.71  960.22  308.02  962.99  335.37  964.35
  347.53  965.44  393.11  968.19  405.27  969.62  414.39  970.11  426.54  971.93
#Mann= 3 , 0 , 0
       0     .09       0  213.47     .04       0     229     .09       0
Bank Sta=213.47,229
XS Rating Curve= 0 ,0
Exp/Cntr=0.3,0.1

Type RM Length L Ch R = 1 ,12893.04,100.11,91.44,72.32
XS GIS Cut Line= 6
     638944.2802    4338246.9584     639023.6418    4338409.4584
     639025.0724    4338425.0083     639025.9701    4338427.3443
     639016.5509    4338433.3768     639086.0972    4338647.0092
#Sta/Elev= 30
       0  970.61     9.2  967.63   15.33   964.2   18.39   963.5   21.46   962.2
   27.59  961.03   42.91  959.71   64.37  959.92   85.82  959.14   91.95  958.39
  101.15   956.5  104.22  956.29  156.32  955.85  162.45  954.19  180.84  954.05
  191.32  953.54  196.46  951.52  210.15  951.84  216.22  953.71   231.4  954.84
  240.51  956.03  249.62  958.09  255.69  958.76  270.87  959.17  295.16  962.07
  343.74  963.73  380.17  966.21  401.42  968.71  422.67  970.24  434.82  972.64
#Mann= 3 , 0 , 0
       0     .09       0  196.46     .04       0  210.15     .09       0
Bank Sta=196.46,210.15
XS Rating Curve= 0 ,0
Exp/Cntr=0.3,0.1

Type RM Length L Ch R = 1 ,12801.6 ,90.07,91.41,88.83
XS GIS Cut Line= 6
     638831.0383    4338308.6593     638925.9795    4338434.4131
     638940.4608    4338437.6494     638944.3798    4338439.0578
     638961.0633    4338446.4781     639075.5138    4338649.9725
#Sta/Elev= 30
       0  972.22    6.06  971.57   18.18  968.71   33.33  963.14   39.39  962.06
   45.45  960.35   54.54  960.37   66.66  957.85   69.69   957.7   75.75  956.51
  157.57  954.75   163.5   954.3  172.41  952.38  176.57  951.43  179.61  951.42
  182.66  952.17   185.7  953.18  194.83  953.76  225.55  953.95  237.84  954.68
  243.98  955.48  259.34  958.94  268.56  958.79  280.85   960.3  296.21  959.87
  308.49  960.04  339.21  962.94  363.79  965.72  412.94  969.12   428.3  971.86
#Mann= 3 , 0 , 0
       0     .09       0  172.41     .04       0  182.66     .09       0
Bank Sta=172.41,182.66
XS Rating Curve= 0 ,0
Exp/Cntr=0.3,0.1

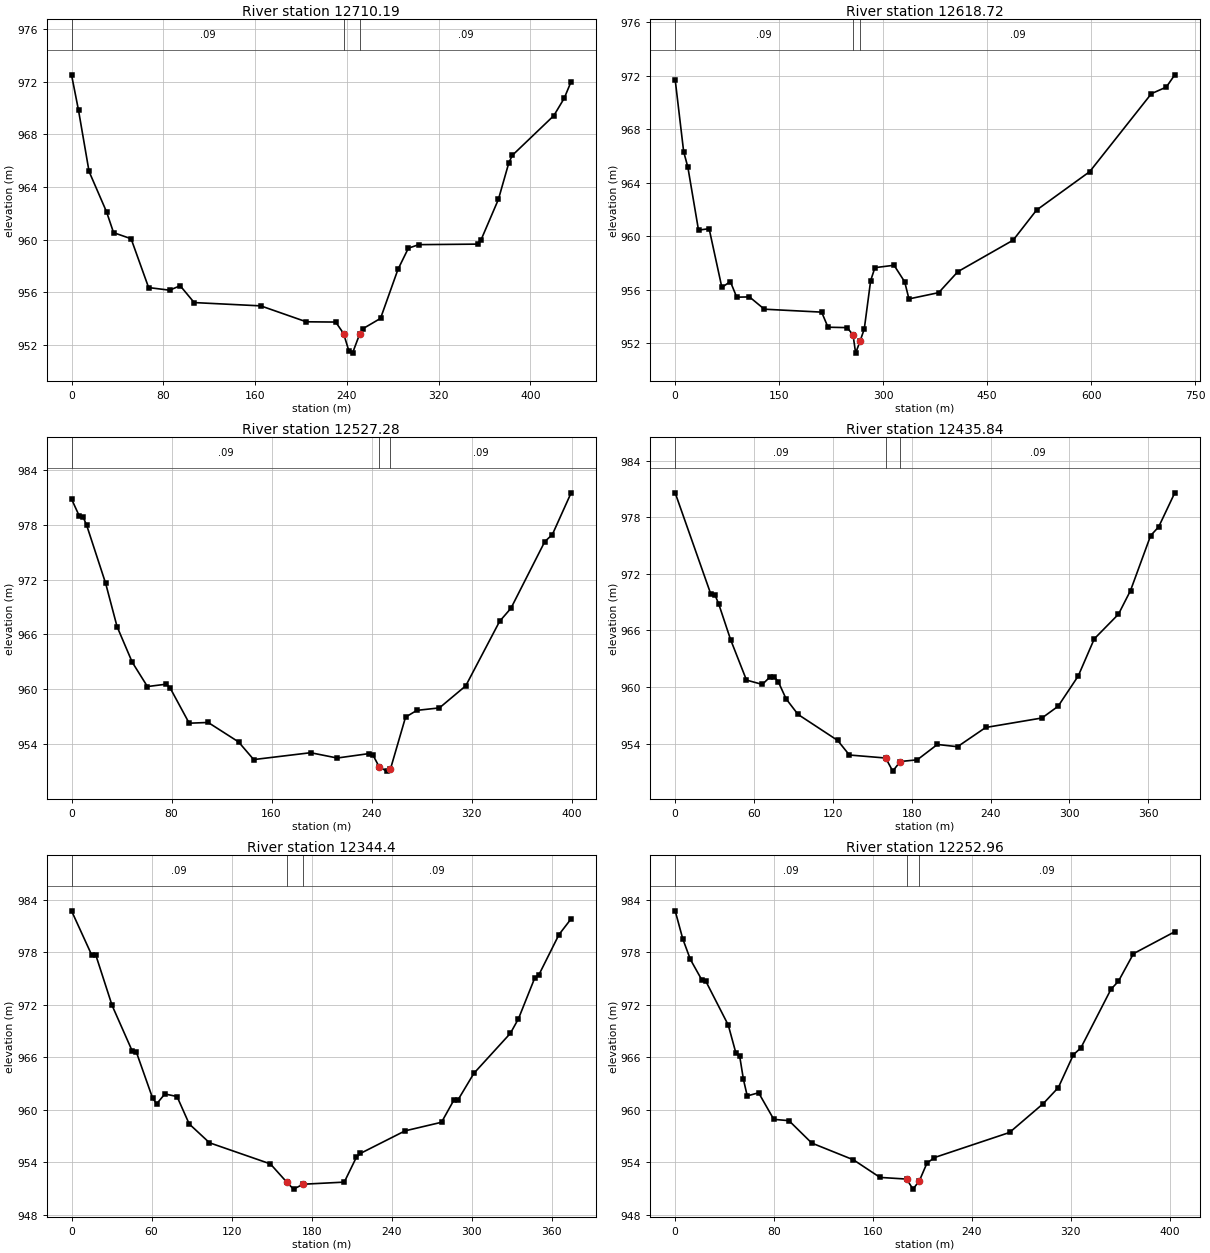
Type RM Length L Ch R = 1 ,12710.19,84.4,91.47,93.94
XS GIS Cut Line= 6
     638796.2125    4338328.5031     638907.8687    4338518.0269
     638922.1558    4338524.0602     638925.1651    4338525.6658
     638962.2464    4338539.7724      639062.913    4338660.2913
#Sta/Elev= 30
       0  972.52    6.11  969.82   15.28  965.18   30.55  962.11   36.66  960.53
   51.94  960.07   67.21  956.36   85.54  956.16   94.71   956.5  106.93  955.22
  164.98  954.97  204.69  953.76  230.31  953.74  237.18  952.87  241.94  951.51
  244.99  951.38   251.1   952.8  254.15  953.24  269.41  954.02   284.6  957.74
  293.66  959.35  302.72  959.62  354.06  959.66  357.08  959.99  372.18  963.06
  381.24  965.83  384.26   966.4  420.49  969.42  429.55  970.74  435.59  972.01
#Mann= 3 , 0 , 0
       0     .09       0  237.18     .04       0   251.1     .09       0
Bank Sta=237.18,251.1
XS Rating Curve= 0 ,0
Exp/Cntr=0.3,0.1

Type RM Length L Ch R = 1 ,12618.72,79.33,91.44,95.33
XS GIS Cut Line= 6
     638786.6875    4338333.2656     638864.1665    4338572.1052
     638867.2804    4338576.5842     638869.1192    4338579.8899
     638870.0932     4338583.006     639077.2005    4338990.4919
#Sta/Elev= 30
       0  971.72   12.25  966.33   18.37  965.15   33.68  960.45   48.99  960.56
   67.37  956.16   79.61   956.6    88.8  955.43  107.17  955.45  128.61  954.53
  211.29  954.31  220.47  953.18  248.03  953.15  256.55  952.61  260.33  951.24
  266.66  952.13   272.8  953.05     282  956.67  288.14  957.64  315.75  957.82
  331.09  956.58  337.22   955.3  380.17  955.77  407.78  957.34  487.54   959.7
  521.29  961.95  597.98  964.83  686.95  970.67  708.42  971.16  720.69  972.08
#Mann= 3 , 0 , 0
       0     .09       0  256.55     .04       0  266.66     .09       0
Bank Sta=256.55,266.66
XS Rating Curve= 0 ,0
Exp/Cntr=0.3,0.1

Type RM Length L Ch R = 1 ,12527.28,89.95,91.44,85.95
XS GIS Cut Line= 6
     638770.0187    4338312.6281     638800.2938    4338538.3115
     638793.6597    4338552.7679     638791.2314    4338560.8624
      638790.078    4338563.7177     638741.3907    4338699.7672
#Sta/Elev= 30
       0  980.79    6.07  978.97    9.11  978.87   12.14  977.91   27.32  971.57
   36.43  966.86   48.58  962.97   60.72  960.32    75.9  960.58   78.94  960.15
   94.12  956.32   109.3   956.4  133.59  954.28  145.73  952.35  191.27   953.1
  212.52  952.52  238.31  953.01  240.96  952.89  246.09  951.55  252.06  951.09
  255.14  951.33  267.18  956.98  276.21  957.72  294.28  957.99  315.35   960.4
  342.44  967.44  351.47  968.86  378.57  976.14  384.59   976.9  399.64  981.46
#Mann= 3 , 0 , 0
       0     .09       0  246.09     .04       0  255.14     .09       0
Bank Sta=246.09,255.14
XS Rating Curve= 0 ,0
Exp/Cntr=0.3,0.1

Type RM Length L Ch R = 1 ,12435.84,81.8,91.44,82.23
XS GIS Cut Line= 6
     638745.6241    4338325.1164      638758.162    4338454.1764
     638748.4589    4338481.7633     638742.0553    4338495.6183
     638743.1137    4338505.5402      638726.574    4338700.8255
#Sta/Elev= 30
       0   980.6   27.14  969.85   30.16  969.81   33.17   968.8   42.22  965.01
   54.28  960.73   66.34  960.27   72.37  961.09   75.39  961.06    78.4  960.58
   84.43  958.74   93.48  957.09  123.64  954.33  132.59  952.78  160.23  952.46
  165.59  951.07  171.34  952.09  184.25  952.27  199.56   953.9  214.88  953.66
  236.31   955.7  279.18  956.71  291.43  957.95  306.74  961.16  318.99  965.11
  337.37  967.72  346.55  970.23  361.86  976.06  367.99  976.99  380.24   980.6
#Mann= 3 , 0 , 0
       0     .09       0  160.23     .04       0  171.34     .09       0
Bank Sta=160.23,171.34
XS Rating Curve= 0 ,0
Exp/Cntr=0.3,0.1

Type RM Length L Ch R = 1 ,12344.4 ,87.91,91.44,84.22
XS GIS Cut Line= 6
     638686.3573    4338346.2832     638680.1582    4338507.3916
     638677.7317    4338517.0628     638676.4439    4338526.7907
     638677.3427    4338528.7627     638668.3656    4338719.8756
#Sta/Elev= 30
       0  982.72   15.21  977.65   18.25  977.65   30.42  971.92   45.63  966.68
   48.67  966.57   60.84  961.32   63.88   960.7   69.97  961.82   79.09  961.53
   88.22   958.4  103.43  956.25  149.06  953.84  161.23  951.78  166.42  950.96
  173.71  951.52  204.49  951.76   213.6  954.61  216.64  955.04  250.05  957.61
  277.38  958.59  286.49  961.08  289.53  961.09  301.67  964.18     329  968.74
  335.08  970.41  347.23  975.04  350.26  975.38  365.45  980.01  374.56  981.81
#Mann= 3 , 0 , 0
       0     .09       0  161.23     .04       0  173.71     .09       0
Bank Sta=161.23,173.71
XS Rating Curve= 0 ,0
Exp/Cntr=0.3,0.1

Type RM Length L Ch R = 1 ,12252.96,89.15,91.44,89.68
XS GIS Cut Line= 5
     638613.3321    4338352.6332     638603.9422    4338539.5593
     638602.8679    4338544.6657     638602.3749    4338549.8112
     638587.9321     4338755.859
#Sta/Elev= 30
       0  982.74    6.14  979.54   12.27  977.19   21.48  974.86   24.55  974.76
   42.96  969.67   49.09  966.49   52.16  966.14   55.23  963.45    58.3  961.57
    67.5  961.93   79.77  958.89   92.05  958.74  110.46  956.18  144.21  954.26
  165.68  952.25  187.16  952.06  192.38  950.91  197.55  951.87  203.62  953.87
   209.7  954.52  270.45  957.39  297.79   960.7  309.94  962.53  322.09  966.28
  328.16  967.07  352.46  973.76  358.54  974.69  370.69  977.84   404.1  980.35
#Mann= 3 , 0 , 0
       0     .09       0  187.16     .04       0  197.55     .09       0
Bank Sta=187.16,197.55
XS Rating Curve= 0 ,0
Exp/Cntr=0.3,0.1

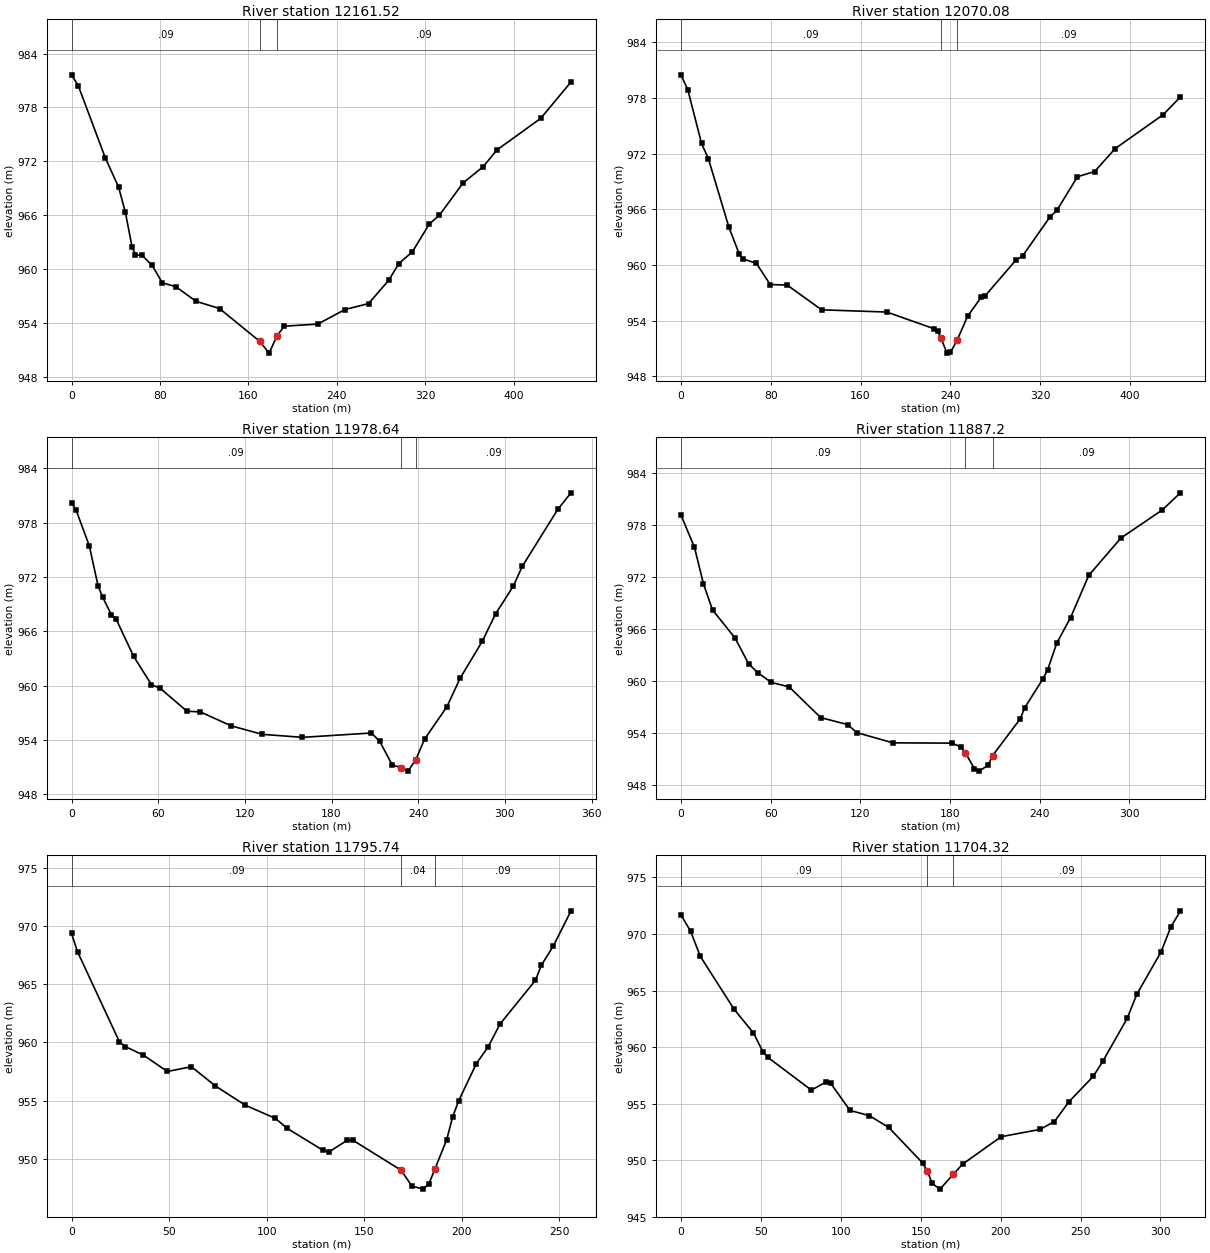
Type RM Length L Ch R = 1 ,12161.52,86.74,91.44,82.33
XS GIS Cut Line= 4
     638588.9904    4338347.3415     638519.9923    4338509.7033
     638518.1444    4338516.1306     638491.6235    4338783.3757
#Sta/Elev= 30
       0  981.63    6.08  980.43   30.42  972.41   42.58  969.11   48.67  966.32
   54.75  962.45   57.79  961.57   63.87   961.5      73  960.38   82.12  958.44
   94.29  958.02  112.54  956.39  133.83  955.58  170.33  951.91  178.64  950.61
  185.86  952.53  192.26  953.61  222.78  953.85  247.19  955.47  268.55  956.13
  286.86  958.73  296.02   960.6  308.23   961.9  323.48     965  332.64  965.98
     354  969.57  372.31   971.4  384.52  973.24  424.19  976.77  451.66  980.83
#Mann= 3 , 0 , 0
       0     .09       0  170.33     .04       0  185.86     .09       0
Bank Sta=170.33,185.86
XS Rating Curve= 0 ,0
Exp/Cntr=0.3,0.1

Type RM Length L Ch R = 1 ,12070.08,78.69,91.44,99.15
XS GIS Cut Line= 5
     638556.7641    4338335.3029     638454.5609    4338526.7706
     638455.8734    4338538.3695     638453.8236    4338546.4753
     638417.0638    4338751.2288
#Sta/Elev= 30
       0   980.5    6.11  978.89   18.34   973.1   24.45  971.46    42.8  964.04
   51.97  961.17   55.02  960.66   67.25  960.17   79.48  957.89   94.76  957.82
  125.33  955.16  183.41  954.92  225.79  953.11  228.71  952.93   231.5  952.17
  237.07  950.49  240.13  950.56  246.25  951.93  255.43  954.47  267.66  956.53
  270.72  956.62  298.26  960.49  304.37  960.96  328.85  965.18  334.97  965.88
  353.32  969.51  368.62  970.07  386.97  972.55   429.8  976.21   445.1  978.12
#Mann= 3 , 0 , 0
       0     .09       0   231.5     .04       0  246.25     .09       0
Bank Sta=231.5,246.25
XS Rating Curve= 0 ,0
Exp/Cntr=0.3,0.1

Type RM Length L Ch R = 1 ,11978.64,90.88,91.44,92.65
XS GIS Cut Line= 6
     638551.2078    4338334.5092      638433.127    4338476.1994
     638394.8682    4338489.2963     638389.6088    4338491.5372
      638385.222    4338493.0182     638284.5073    4338538.5033
#Sta/Elev= 30
       0  980.23    3.07  979.44    12.3  975.45   18.44  970.99   21.52  969.79
   27.67  967.82   30.74   967.4   43.04  963.23   55.33  960.12   61.48   959.7
   79.93  957.18   89.15  957.11  110.67  955.56  132.18  954.63  159.85   954.3
  207.55  954.78  213.33  953.86  221.99  951.26  227.74  950.96  232.91  950.57
   238.3  951.84  244.44  954.12  259.79  957.66     269  960.83  284.34  964.91
  293.55  967.94  305.83     971  311.97  973.17  336.53  979.46  345.74   981.3
#Mann= 3 , 0 , 0
       0     .09       0  227.74     .04       0   238.3     .09       0
Bank Sta=227.74,238.3
XS Rating Curve= 0 ,0
Exp/Cntr=0.3,0.1

Type RM Length L Ch R = 1 ,11887.2 ,90.4,91.46,89.2
XS GIS Cut Line= 4
     638533.7232    4338315.7458     638425.0585    4338386.5324
     638352.2093    4338407.2777     638228.1289    4338441.4231
#Sta/Elev= 30
       0  979.19    9.05  975.45   15.08  971.23   21.11  968.24   36.19     965
   45.24  962.03   51.27  961.02   60.32  959.89   72.38  959.36    93.5  955.82
  111.59  955.01  117.62  954.09  141.81  952.91  181.19  952.88  187.25  952.44
  190.28  951.76  196.34  949.93  199.37  949.65  205.43  950.32   208.5  951.45
  226.88  955.66  229.95  956.96   242.2   960.3  245.27  961.33  251.39  964.41
  260.59  967.34  272.84  972.23  294.29  976.52  321.87  979.75  334.13  981.74
#Mann= 3 , 0 , 0
       0     .09       0  190.28     .04       0   208.5     .09       0
Bank Sta=190.28,208.5
XS Rating Curve= 0 ,0
Exp/Cntr=0.3,0.1

Type RM Length L Ch R = 1 ,11795.74,81.91,91.42,95.45
XS GIS Cut Line= 4
      638488.744    4338277.3811     638326.0279    4338322.7275
     638318.5811     4338326.112      638242.681    4338347.4958
#Sta/Elev= 30
       0  969.36    3.07  967.79   24.57  960.05   27.64  959.64   36.85  958.91
   49.14  957.51   61.42  957.92   73.71  956.27   89.07  954.61  104.42  953.49
  110.56  952.62  128.99  950.73  132.06  950.62  141.28   951.6  144.35  951.59
  168.92  949.03  174.37  947.68  180.13  947.41  183.16  947.87   186.2  949.13
  192.26  951.66  195.29  953.61  198.33  954.97  207.43  958.18  213.49  959.62
  219.56  961.58  237.75  965.34  240.79  966.64  246.85  968.27  255.95   971.3
#Mann= 3 , 0 , 0
       0     .09       0  168.92     .04       0   186.2     .09       0
Bank Sta=168.92,186.2
XS Rating Curve= 0 ,0
Exp/Cntr=0.3,0.1

Type RM Length L Ch R = 1 ,11704.32,97.96,91.44,79.63
XS GIS Cut Line= 6
      638485.128    4338219.7239     638336.0887    4338244.7811
      638327.757    4338243.3128     638323.0525    4338241.8554
     638308.7439    4338238.9073     638180.0628    4338273.9636
#Sta/Elev= 30
       0  971.69    6.05  970.24   12.09  968.03   33.25  963.34   45.34  961.25
   51.38  959.55   54.41  959.08   81.61  956.19   90.68   956.9    93.7  956.79
  105.79  954.39  117.88  953.93  129.97  952.89  151.13  949.75  154.17  949.01
   157.2  947.93  162.06  947.43  170.37  948.74  176.21  949.64  200.35  952.07
   224.6  952.71  233.69  953.41  242.79  955.17  257.94   957.4  264.01  958.76
  279.16  962.53  285.22  964.67  300.38  968.42  306.44   970.6   312.5  972.05
#Mann= 3 , 0 , 0
       0     .09       0  154.17     .04       0  170.37     .09       0
Bank Sta=154.17,170.37
XS Rating Curve= 0 ,0
Exp/Cntr=0.3,0.1