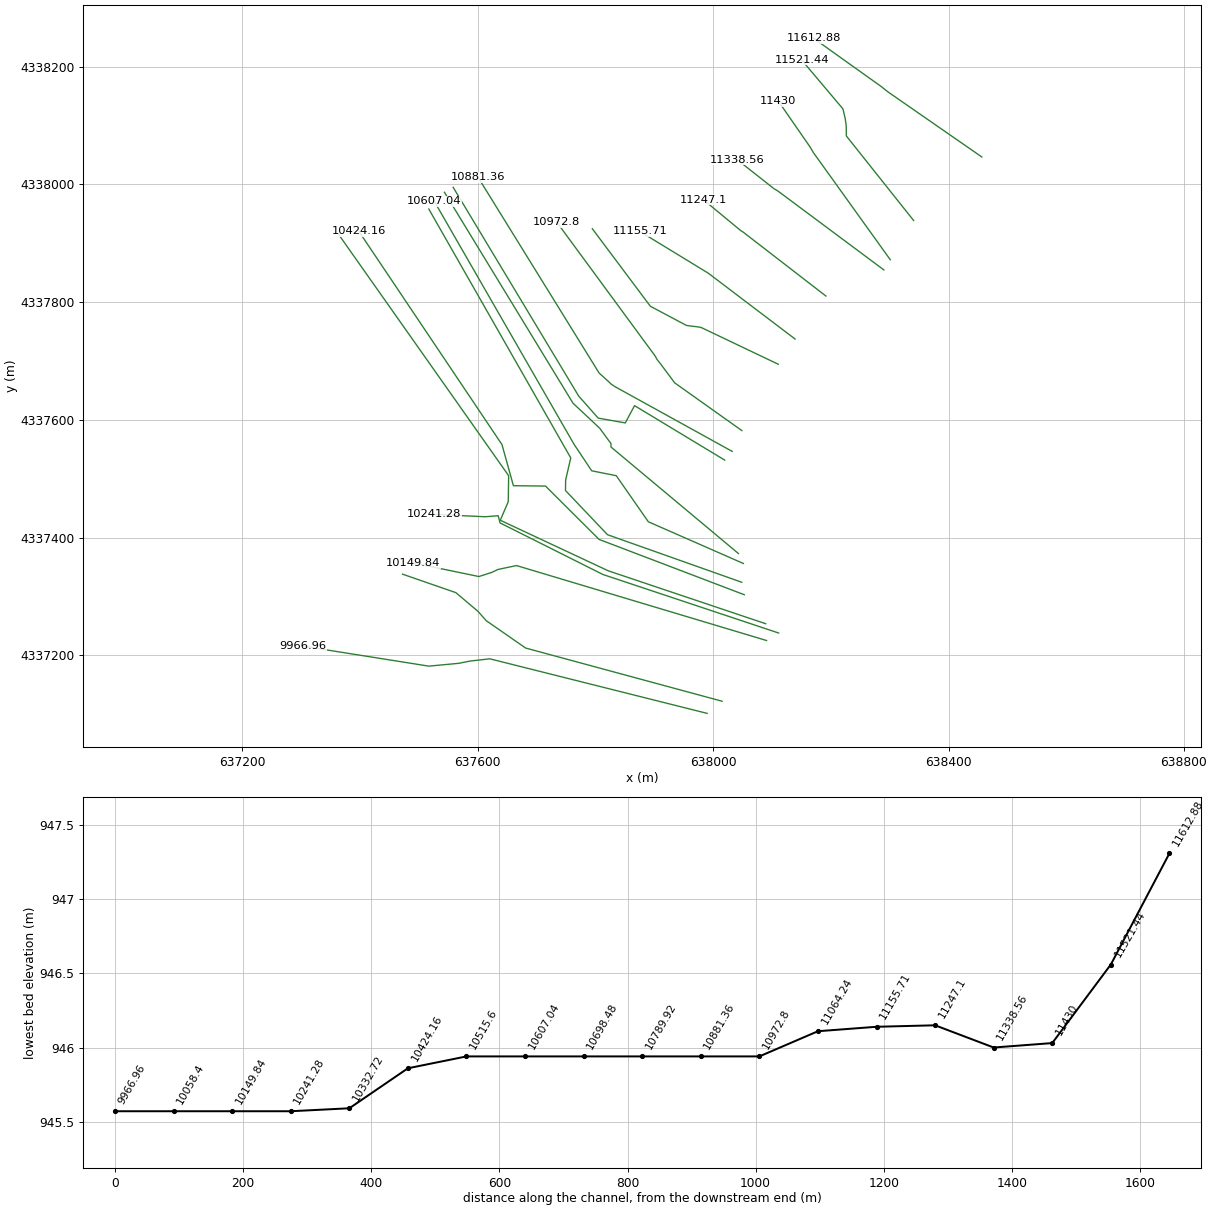
HEC-RAS study BeaverCreek.prj: BeaverCreek

--- BeaverCreek.g01 (geometry) --- (continued)

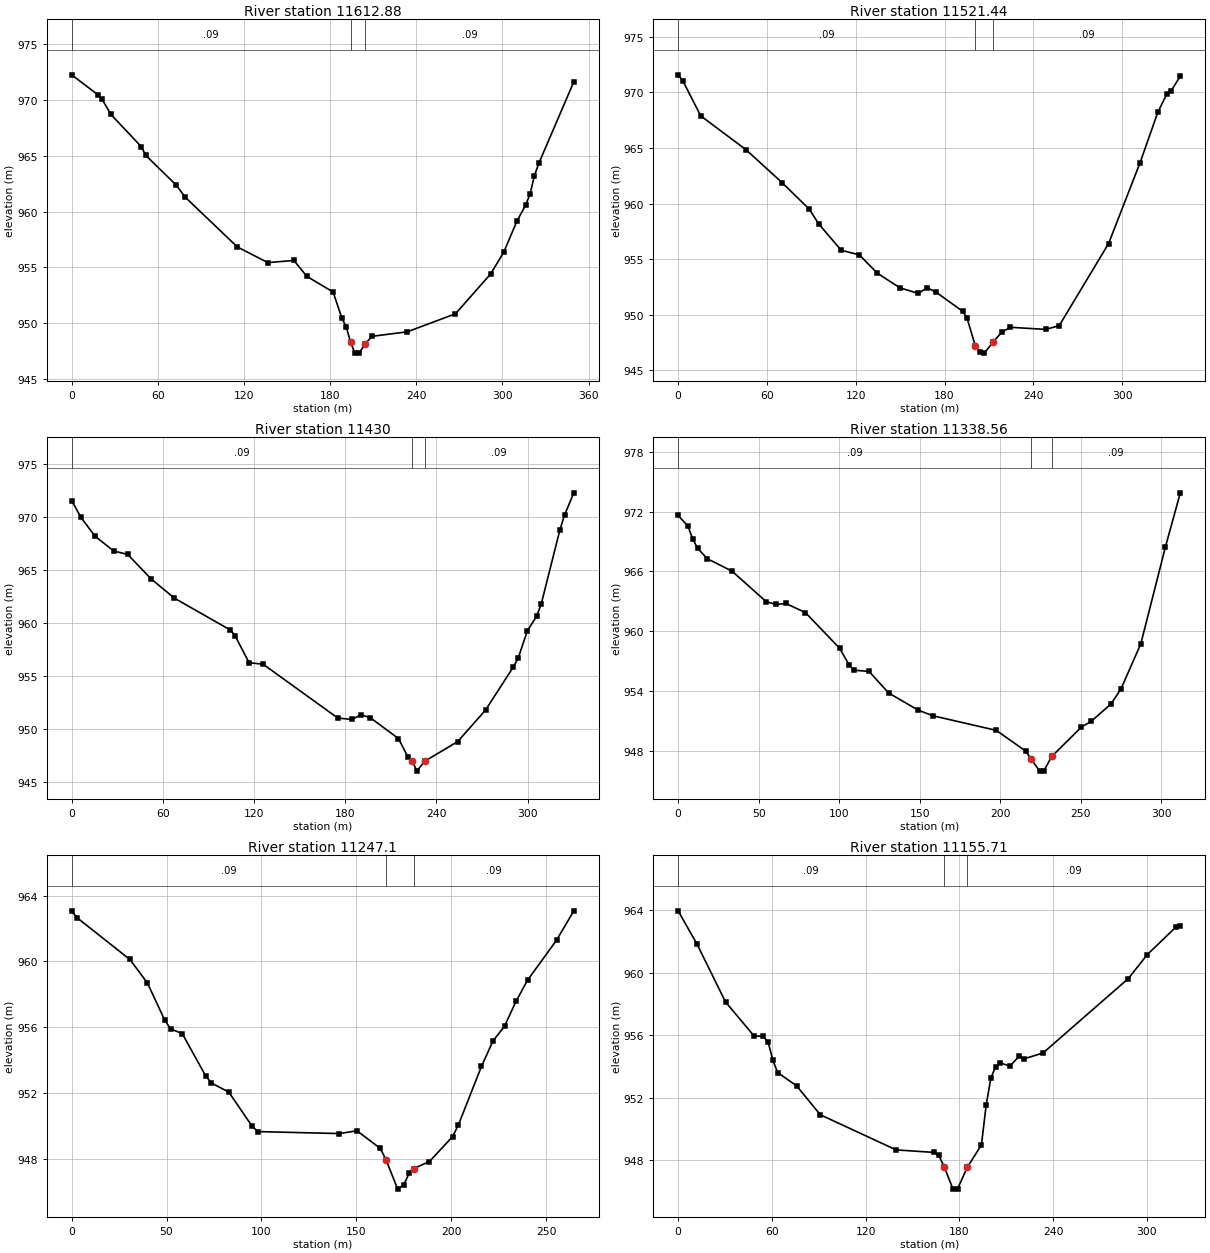
Type RM Length L Ch R = 1 ,11612.88,99.74,91.44,81.4
XS GIS Cut Line= 4
      638456.553     4338046.686     638296.9413    4338157.3565
     638285.1321    4338166.7391     638170.8024    4338248.2989
#Sta/Elev= 30
       0  972.27   18.21  970.49   21.24  970.07   27.31  968.72   48.56  965.82
   51.59  965.05   72.83  962.38    78.9  961.32  115.32  956.84  136.57  955.43
  154.77  955.62  163.88  954.19  182.09  952.79  188.16  950.46  191.19  949.68
  194.23   948.3  197.24  947.32  200.26  947.31  204.28  948.13  209.31  948.82
  233.73  949.22  267.32  950.84  291.74   954.4   300.9  956.35  310.06  959.14
  316.17  960.59  319.22  961.56  322.27  963.22  325.32  964.32  349.75  971.65
#Mann= 3 , 0 , 0
       0     .09       0  194.23     .04       0  204.28     .09       0
Bank Sta=194.23,204.28
XS Rating Curve= 0 ,0
Exp/Cntr=0.3,0.1

Type RM Length L Ch R = 1 ,11521.44,79.32,91.44,89.39
XS GIS Cut Line= 6
     638340.6652    4337938.7358     638226.3327     4338082.406
     638226.1101    4338099.5732     638224.4379    4338111.6959
     638220.5118    4338128.4436     638150.1648    4338211.7864
#Sta/Elev= 30
       0  971.56    3.06  971.05    15.3  967.87    45.9  964.83   70.38  961.86
   88.75  959.47   94.87  958.19  110.17   955.8  122.41  955.39  134.65  953.73
  149.95  952.42  162.19  951.93  168.31  952.43  174.43  952.02   192.2  950.32
  195.06  949.76  200.78  947.22  203.84  946.64   206.9  946.56  213.02   947.6
  218.75  948.45  224.49  948.88   248.4  948.69  257.48  949.03  290.81   956.4
  312.02  963.64  324.13  968.21  330.19  969.84  333.22  970.14  339.28  971.45
#Mann= 3 , 0 , 0
       0     .09       0  200.78     .04       0  213.02     .09       0
Bank Sta=200.78,213.02
XS Rating Curve= 0 ,0
Exp/Cntr=0.3,0.1

Type RM Length L Ch R = 1 ,11430   ,87.65,91.44,96.64
XS GIS Cut Line= 4
     638300.9776    4337872.0607     638170.2504    4338054.2367
     638164.4669    4338064.0483     638110.4773    4338141.9362
#Sta/Elev= 30
       0  971.51    6.14  969.92   15.36  968.16   27.64  966.76   36.86  966.44
   52.22  964.14   67.58  962.32  104.43  959.32  107.51  958.78  116.72  956.24
  125.94   956.1  175.08  951.03   184.3   950.9  190.44  951.33  196.58  951.05
  215.01   949.1  221.16  947.38  224.23  946.96  227.07  946.03  232.17  946.95
  253.96  948.81   272.3  951.78  290.64  955.85   293.7  956.65  299.82  959.24
  305.93  960.62  308.99   961.8  321.22  968.75  324.27  970.15  330.39  972.24
#Mann= 3 , 0 , 0
       0     .09       0  224.23     .04       0  232.17     .09       0
Bank Sta=224.23,232.17
XS Rating Curve= 0 ,0
Exp/Cntr=0.3,0.1

Type RM Length L Ch R = 1 ,11338.56,91.55,91.46,91.19
XS GIS Cut Line= 5
     638290.0305    4337854.8297     638112.0453    4337987.3633
     638107.6747    4337990.3401     638103.4192    4337992.7499
     638040.7925     4338042.155
#Sta/Elev= 30
       0  971.61    6.08  970.53    9.12  969.23   12.16   968.3   18.24  967.26
   33.44  966.03   54.72  962.97    60.8  962.69   66.88  962.79   79.04  961.88
  100.32   958.3   106.4  956.58  109.43   956.1  118.55  955.99  130.71  953.83
  148.95  952.12  158.07  951.55  197.59  950.08  215.83  948.01  219.06  947.24
  224.55     946   227.2  946.06  232.09  947.48   250.5  950.42  256.63     951
   268.9  952.74  275.04  954.24  287.31  958.74  302.65  968.47  311.86  973.87
#Mann= 3 , 0 , 0
       0     .09       0  219.06     .04       0  232.09     .09       0
Bank Sta=219.06,232.09
XS Rating Curve= 0 ,0
Exp/Cntr=0.3,0.1

Type RM Length L Ch R = 1 ,11247.1 ,91.49,91.39,91.55
XS GIS Cut Line= 4
     638191.6053    4337810.3796     638050.7952    4337919.1693
     638046.9679    4337921.5122     637983.6424    4337973.8924
#Sta/Elev= 30
       0  963.05    3.07  962.64   30.68  960.12   39.88   958.7   49.09  956.42
   52.15   955.9   58.29  955.61   70.56  953.05   73.63  952.61   82.83  952.05
   95.11  949.97   98.17  949.65  141.12  949.53  150.33   949.7   162.6  948.63
  165.67  947.93   171.8  946.15  174.87   946.4  177.94  947.13  180.18   947.4
  188.52  947.83  200.69  949.34  203.73  950.04  215.91  953.61     222  955.16
  228.08  956.06  234.17  957.58  240.26  958.87  255.48  961.29  264.61  963.08
#Mann= 3 , 0 , 0
       0     .09       0  165.67     .04       0  180.18     .09       0
Bank Sta=165.67,180.18
XS Rating Curve= 0 ,0
Exp/Cntr=0.3,0.1

Type RM Length L Ch R = 1 ,11155.71,87.74,91.47,96.72
XS GIS Cut Line= 3
     638139.2177    4337737.3544       637991.81    4337849.1637
     637875.4201     4337920.217
#Sta/Elev= 30
       0  963.95   12.13  961.81   30.33  958.12   48.53  955.95   54.59  955.91
   57.63  955.54   60.66  954.38   63.69   953.6   75.83  952.75   90.99   950.9
  139.52  948.65  163.78  948.49  166.82   948.3  170.41  947.54  175.92  946.14
  178.95  946.18  185.01  947.53  194.11  948.97  197.14  951.52  200.17  953.26
   203.2  953.97  206.23  954.22  212.29  954.01  218.35  954.65  221.38  954.48
   233.5  954.85  288.05  959.61  300.17  961.14  318.35  962.89  321.38  962.96
#Mann= 3 , 0 , 0
       0     .09       0  170.41     .04       0  185.01     .09       0
Bank Sta=170.41,185.01
XS Rating Curve= 0 ,0
Exp/Cntr=0.3,0.1

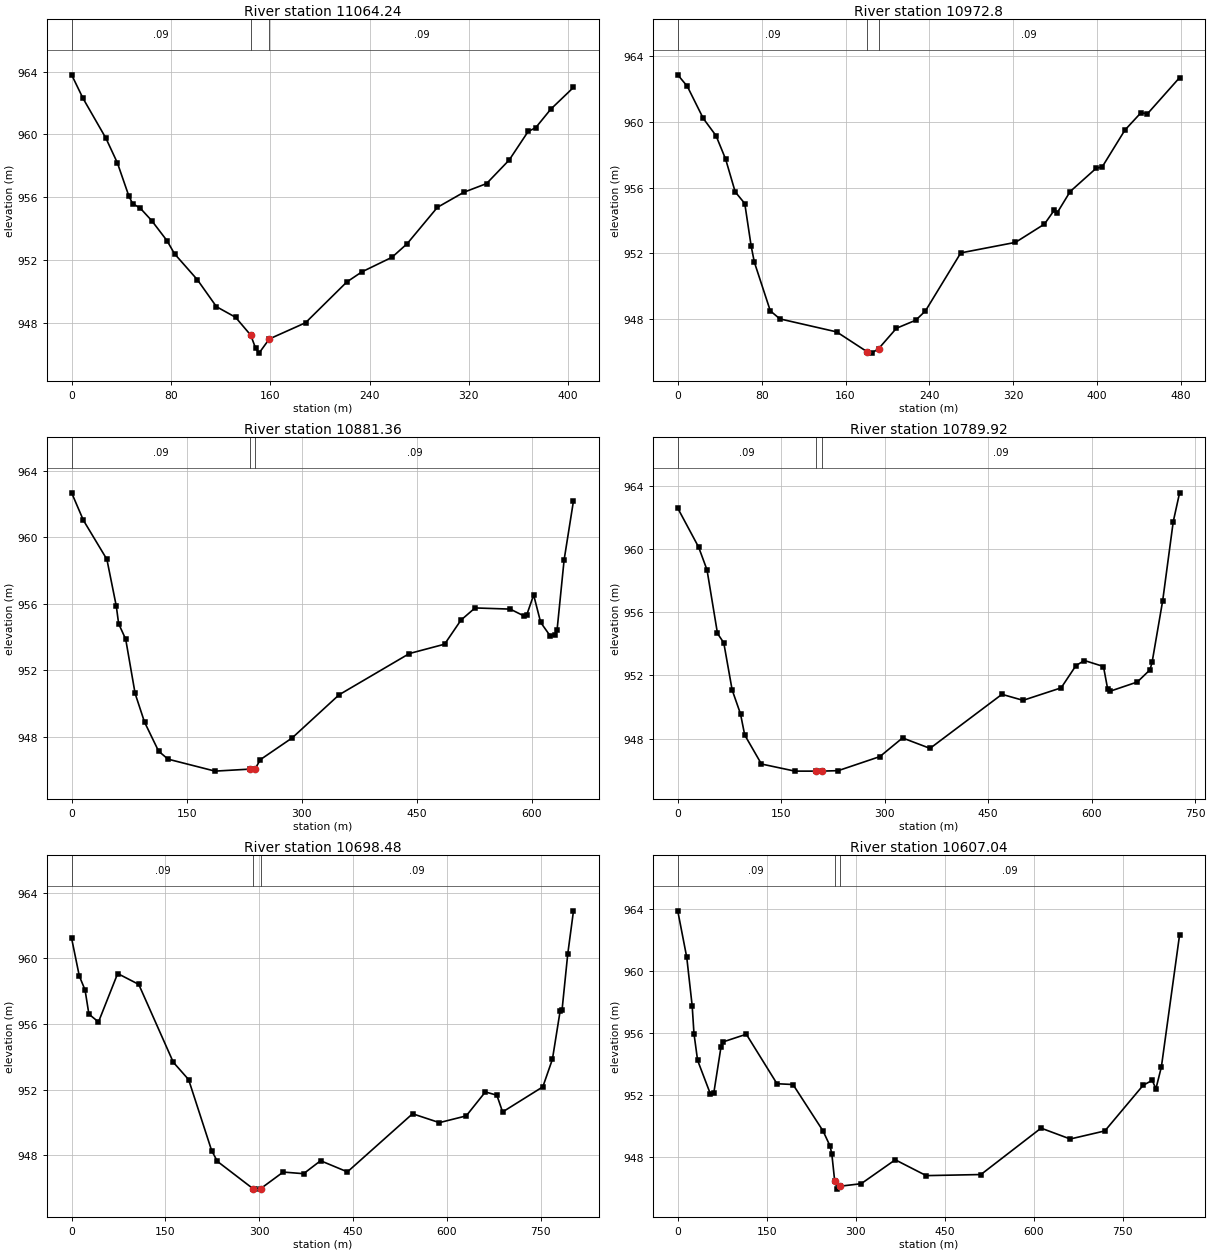
Type RM Length L Ch R = 1 ,11064.24,97.13,91.44,74.27
XS GIS Cut Line= 6
     638110.6426    4337694.4918     637980.3903    4337756.5985
     637976.6144    4337757.6204     637954.7114    4337760.3967
     637893.3013    4337793.0076     637794.7295    4337924.6798
#Sta/Elev= 30
       0  963.79    9.21  962.29   27.63  959.76   36.84   958.2   46.05   956.1
   49.12  955.61   55.26  955.32   64.48  954.53   76.76  953.26    82.9  952.42
  101.32  950.77  116.67  949.06  132.02  948.39   144.3  947.25  148.21  946.42
  150.97  946.11  159.25  947.01  188.43  948.04  221.68  950.63  233.78  951.27
   258.1   952.2  270.28  953.06  294.65  955.37  315.97  956.33  334.25  956.88
  352.52  958.38  367.75  960.19  373.84  960.43  386.03  961.61   404.3  962.99
#Mann= 3 , 0 , 0
       0     .09       0   144.3     .04       0  159.25     .09       0
Bank Sta=144.3,159.25
XS Rating Curve= 0 ,0
Exp/Cntr=0.3,0.1

Type RM Length L Ch R = 1 ,10972.8 ,83.65,91.44,92.71
XS GIS Cut Line= 6
       638048.73    4337581.7791     637934.6289    4337662.8902
     637910.4644    4337695.3106      637904.635    4337702.5815
     637901.5568    4337708.2932     637734.4044    4337935.7923
#Sta/Elev= 30
       0  962.85    9.13  962.15   24.35   960.2   36.52  959.15   45.65  957.73
   54.78  955.74   63.91  955.03      70  952.45   73.04  951.47   88.26  948.51
   97.39  948.02  151.55  947.23  180.43  946.03  184.99  945.94  191.67  946.22
  208.52  947.45  226.93  947.94  236.14   948.5  269.89  952.03  322.05  952.67
  349.67  953.78  358.88  954.61  361.95  954.48  374.22  955.76  398.77  957.16
   404.9  957.27  426.38  959.49  441.73  960.55  447.86  960.48  478.55  962.68
#Mann= 3 , 0 , 0
       0     .09       0  180.43     .04       0  191.67     .09       0
Bank Sta=180.43,191.67
XS Rating Curve= 0 ,0
Exp/Cntr=0.3,0.1

Type RM Length L Ch R = 1 ,10881.36,52.42,91.44,71.66
XS GIS Cut Line= 6
     638032.3258    4337546.4307     637833.8465    4337656.0313
     637826.9852    4337660.4857     637821.0763    4337666.1056
      637806.224    4337679.5263     637600.5249    4338012.0983
#Sta/Elev= 30
       0  962.67   15.32  961.02   45.96  958.67   58.21  955.86   61.28   954.8
   70.47  953.87   82.73  950.61   94.98  948.89  113.36  947.14  125.62  946.66
   186.9  945.94  232.18  946.06  239.37  946.09  245.94  946.63  287.53  947.94
  348.63  950.53  440.29  953.01  486.11  953.57   507.5  955.02  525.83  955.75
  571.65  955.68  589.98  955.26  593.04  955.31   602.2  956.53  611.37  954.88
  623.59  954.08   629.7  954.13  632.75  954.43  641.92  958.64  654.14  962.19
#Mann= 3 , 0 , 0
       0     .09       0  232.18     .04       0  239.37     .09       0
Bank Sta=232.18,239.37
XS Rating Curve= 0 ,0
Exp/Cntr=0.3,0.1

Type RM Length L Ch R = 1 ,10789.92,109.96,91.44,59.15
XS GIS Cut Line= 6
     638019.6258     4337531.614     637866.4344    4337624.1287
     637850.6894    4337594.7942     637804.6276    4337602.9619
     637771.4929     4337640.427     637558.1915    4337995.1649
#Sta/Elev= 30
       0  962.58   30.33  960.11   42.46  958.67   57.63  954.65   66.73  954.06
   78.86  951.08      91  949.56   97.06  948.23  121.33  946.39  169.86  945.94
  200.76  945.94  208.91  945.94  232.65  945.97  293.03  946.86  325.88  948.04
  365.74  947.38  469.99   950.8  500.65  950.42  555.84  951.21  577.31  952.62
  589.57  952.94  617.17  952.56   623.3  951.13  626.37  950.99  666.23  951.58
  684.62  952.35  687.69  952.83  703.02  956.72  718.35  961.73  727.55  963.55
#Mann= 3 , 0 , 0
       0     .09       0  200.76     .04       0  208.91     .09       0
Bank Sta=200.76,208.91
XS Rating Curve= 0 ,0
Exp/Cntr=0.3,0.1

Type RM Length L Ch R = 1 ,10698.48,65.65,91.44,53.75
XS GIS Cut Line= 6
     638042.9092    4337372.8637     637826.4644    4337553.7921
     637826.2971    4337559.8039      637807.247    4337585.7331
     637761.8268    4337628.3311     637543.3748    4337986.6983
#Sta/Elev= 30
       0  961.21   12.27  958.92   21.46  958.07    27.6   956.6   42.93  956.12
   73.59  959.07  107.32  958.41  162.52  953.67  187.05  952.61  223.84  948.29
  233.04  947.63  290.27  945.96  292.42  945.94  302.23  945.97  338.26  946.98
  370.88  946.88  398.06  947.67  440.95  946.99  545.11  950.53  587.99  949.99
  630.88   950.4  661.52  951.86   679.9  951.66  689.09  950.64  753.42  952.17
  768.74  953.85     781  956.77  784.06  956.82  793.25  960.26  802.44  962.89
#Mann= 3 , 0 , 0
       0     .09       0  290.27     .04       0  302.23     .09       0
Bank Sta=290.27,302.23
XS Rating Curve= 0 ,0
Exp/Cntr=0.3,0.1

Type RM Length L Ch R = 1 ,10607.04,95.71,91.44,17.39
XS GIS Cut Line= 6
     638051.3758    4337355.9303     637889.8729    4337426.8015
     637835.3484     4337505.124      637793.621    4337513.4135
     637763.4823    4337558.7134     637526.0887    4337971.4406
#Sta/Elev= 30
       0  963.87    15.2  960.87   24.33  957.75   27.37  955.96   33.45  954.24
   54.74   952.1   60.82  952.15   72.98  955.12   76.02  955.42  115.55  955.92
  167.25  952.73  194.23  952.68  244.83  949.69  256.74  948.71  259.72  948.18
  264.44  946.48  269.09  945.94  274.04  946.13  309.14  946.29  366.54  947.83
  418.71  946.81  510.86  946.88  612.23  949.87  661.38  949.17  719.74  949.69
  784.25  952.63  799.61  952.95  805.75   952.4  814.97  953.81  845.69  962.33
#Mann= 3 , 0 , 0
       0     .09       0  264.44     .04       0  274.04     .09       0
Bank Sta=264.44,274.04
XS Rating Curve= 0 ,0
Exp/Cntr=0.3,0.1

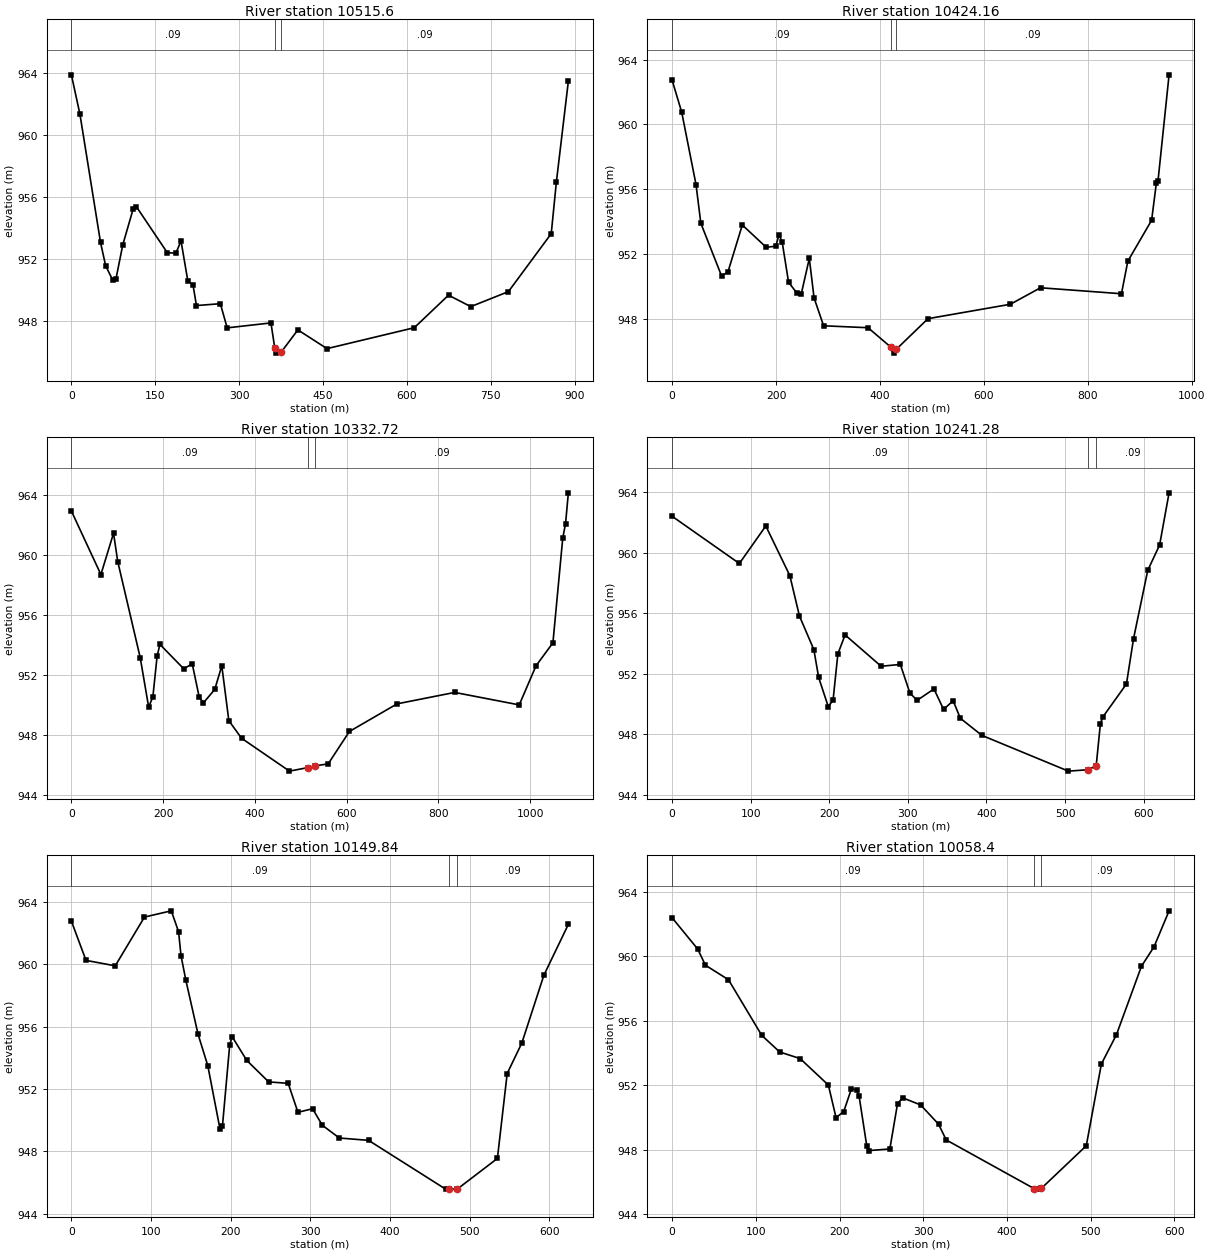
Type RM Length L Ch R = 1 ,10515.6 ,54.12,91.44,122.19
XS GIS Cut Line= 6
     638048.6418    4337324.0039     637820.4602    4337404.8356
     637749.0298    4337479.9693     637749.3614    4337498.0315
     637758.0309     4337535.287     637516.8282    4337958.2114
#Sta/Elev= 30
       0   963.9   15.32  961.35   52.09  953.09   61.28  951.58   73.54  950.68
   79.67  950.72   91.93  952.93  110.31  955.22  116.44  955.38   171.6  952.42
  186.92  952.39  196.11  953.18  208.37  950.58  217.56  950.34  223.69  949.01
  266.47  949.13  278.66  947.57  356.97  947.89  363.82  946.26  366.76  945.94
  375.59  946.02  405.13  947.44  457.18  946.23  613.35  947.58  674.59  949.68
   714.4  948.94  781.76  949.91  858.32  953.65   867.5  956.98  888.94  963.49
#Mann= 3 , 0 , 0
       0     .09       0  363.82     .04       0  375.59     .09       0
Bank Sta=363.82,375.59
XS Rating Curve= 0 ,0
Exp/Cntr=0.3,0.1

Type RM Length L Ch R = 1 ,10424.16,120.34,91.44,32.29
XS GIS Cut Line= 6
     638052.8752    4337302.8372     637806.0909    4337396.8468
     637715.1768    4337487.4607     637660.5667    4337488.0957
     637641.1784    4337557.8936     637397.7655    4337920.6405
#Sta/Elev= 30
       0  962.73   18.42  960.76   46.06  956.27   55.27  953.89   95.19  950.63
  107.48  950.88  135.11  953.78  181.17   952.4   199.6  952.47  205.74  953.18
  211.88  952.72  224.16  950.24  239.52   949.6  248.73  949.54  264.08  951.71
  273.25  949.27  291.59  947.55  377.16  947.43  420.62  946.24  426.24  945.86
  431.87  946.11  492.51  947.99  651.03  948.88  709.08   949.9  864.87  949.53
  877.09  951.54  922.92  954.07  932.08  956.38  935.14  956.48  956.52  963.06
#Mann= 3 , 0 , 0
       0     .09       0  420.62     .04       0  431.87     .09       0
Bank Sta=420.62,431.87
XS Rating Curve= 0 ,0
Exp/Cntr=0.3,0.1

Type RM Length L Ch R = 1 ,10332.72,29.46,91.44,98.5
XS GIS Cut Line= 6
     638089.1231    4337253.6246     637821.9825    4337343.3879
     637638.2534    4337429.4066     637651.8174    4337460.8716
     637652.4748    4337505.1438     637363.3696    4337915.3488
#Sta/Elev= 30
       0  962.91   64.33  958.68    91.9  961.43  101.09  959.54   150.1  953.14
  168.48  949.85  177.67  950.54  186.86  953.24  192.98  954.03  245.06   952.4
  263.44  952.74  278.76  950.51  287.97  950.14  312.56  951.03  327.92   952.6
  343.29  948.95  370.96  947.78  475.47  945.59  516.41  945.83  530.49  945.94
  559.78  946.07  606.12  948.23  710.16  950.07  835.62  950.83  976.38     950
 1013.11  952.61 1049.83  954.13 1071.25   961.1 1077.37  962.07 1083.49  964.12
#Mann= 3 , 0 , 0
       0     .09       0  516.41     .04       0  530.49     .09       0
Bank Sta=516.41,530.49
XS Rating Curve= 0 ,0
Exp/Cntr=0.3,0.1

Type RM Length L Ch R = 1 ,10241.28,89.34,91.44,97.79
XS GIS Cut Line= 6
     638111.3482    4337237.7495     637812.6323    4337337.2234
     637637.9448    4337424.8426     637634.6955      4337437.11
     637612.8419    4337435.3631     637525.5595    4337439.3624
#Sta/Elev= 30
       0  962.41   85.59  959.29  119.21  961.77  149.78  958.49  162.01  955.82
  180.35   953.6  186.46  951.76  198.69  949.83   204.8  950.26  210.91  953.32
  220.08  954.57  265.94   952.5  290.39  952.62  302.62  950.72  311.79  950.25
  333.16     951  345.38  949.65  357.59  950.22  366.75  949.06  394.24  947.93
  504.17  945.57  528.75  945.66  539.54  945.91  544.94  948.71  547.95  949.14
  578.08  951.33  587.12  954.33  605.19  958.84  620.26  960.51  632.31  963.96
#Mann= 3 , 0 , 0
       0     .09       0  528.75     .04       0  539.54     .09       0
Bank Sta=528.75,539.54
XS Rating Curve= 0 ,0
Exp/Cntr=0.3,0.1

Type RM Length L Ch R = 1 ,10149.84,102.54,91.44,71.52
XS GIS Cut Line= 6
     638090.7106    4337225.0495     637665.7966    4337352.4127
     637634.2248    4337345.7417     637624.3099    4337340.9827
     637601.9629    4337333.7389     637490.6344    4337356.8123
#Sta/Elev= 30
       0  962.77   18.36  960.25   55.07   959.9   91.78  963.03  125.43  963.43
  134.61  962.09  137.67  960.55  143.78  958.97  159.08  955.51  171.32  953.49
  186.61  949.43  189.67  949.59  198.85  954.84  201.91  955.35  220.27  953.83
   247.8  952.45  272.27  952.36  284.51   950.5  302.87  950.73   315.1  949.67
  336.52  948.85  373.23   948.7  469.99  945.57  474.42  945.57  484.82  945.58
  535.01  947.54   547.3  952.99  565.73  954.95  593.39   959.3  624.12  962.56
#Mann= 3 , 0 , 0
       0     .09       0  474.42     .04       0  484.82     .09       0
Bank Sta=474.42,484.82
XS Rating Curve= 0 ,0
Exp/Cntr=0.3,0.1

Type RM Length L Ch R = 1 ,10058.4 ,73.26,91.44,101.64
XS GIS Cut Line= 6
     638015.1719    4337121.8618     637681.3922    4337212.2288
      637614.284     4337258.828     637600.1931     4337274.775
      637562.794    4337306.3751     637472.2459    4337337.7622
#Sta/Elev= 30
       0  962.39    30.6  960.45   39.78  959.45   67.32  958.55  107.11   955.1
  128.53  954.07  153.01  953.66  186.67  952.02  195.85     950  205.03  950.38
  214.21  951.79  220.33  951.72  223.39  951.33  232.57  948.24  235.63  947.96
  260.11  948.06  269.29  950.87  275.41  951.23  296.83  950.79  318.26   949.6
  327.44  948.62  432.88  945.59  435.57  945.57  440.96  945.61  494.78  948.26
  512.82  953.33  530.79  955.14  560.73  959.39  575.71  960.59  593.68  962.82
#Mann= 3 , 0 , 0
       0     .09       0  432.88     .04       0  440.96     .09       0
Bank Sta=432.88,440.96
XS Rating Curve= 0 ,0
Exp/Cntr=0.3,0.1

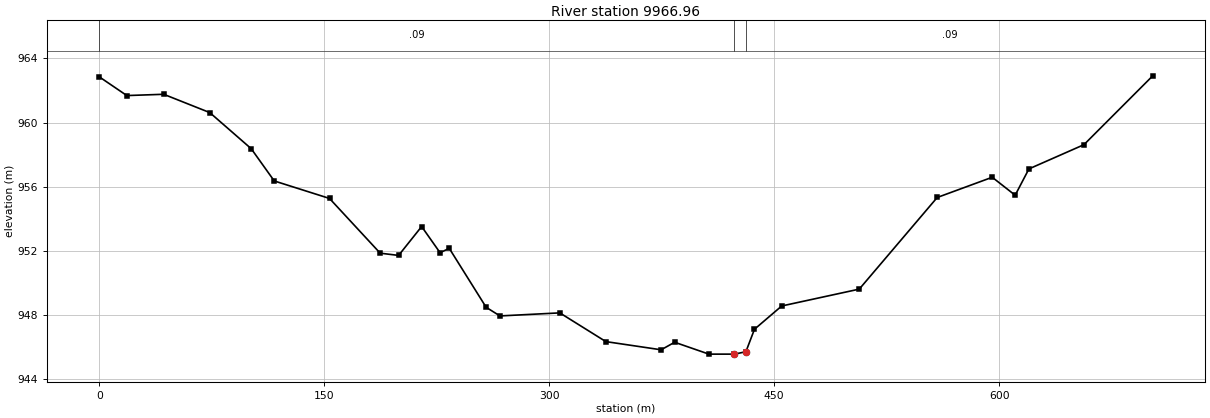
Type RM Length L Ch R = 1 ,9966.96 ,98.31,91.44,78.16
XS GIS Cut Line= 6
     637989.7719    4337101.2243      637620.469    4337193.9446
     637586.4013    4337190.0604      637568.019    4337186.3132
     637516.7594    4337181.5095      637302.383    4337215.5245
#Sta/Elev= 30
       0  962.85   18.42  961.68   42.99  961.76    73.7  960.62  101.33  958.37
  116.69  956.36  153.53  955.27  187.31  951.86  199.59  951.72  214.95  953.52
  227.23  951.89  233.37  952.16  257.94  948.49  267.15  947.95  307.07  948.14
  337.77  946.35  374.62  945.84  383.62  946.31  406.48  945.57  423.52  945.57
  431.13  945.72  436.84  947.12  455.01  948.57   506.7  949.62  558.67  955.33
  595.35  956.59  610.64  955.47  619.81  957.11   656.5  958.62  702.36  962.91
#Mann= 3 , 0 , 0
       0     .09       0  423.52     .04       0  431.13     .09       0
Bank Sta=423.52,431.13
XS Rating Curve= 0 ,0
Exp/Cntr=0.3,0.1