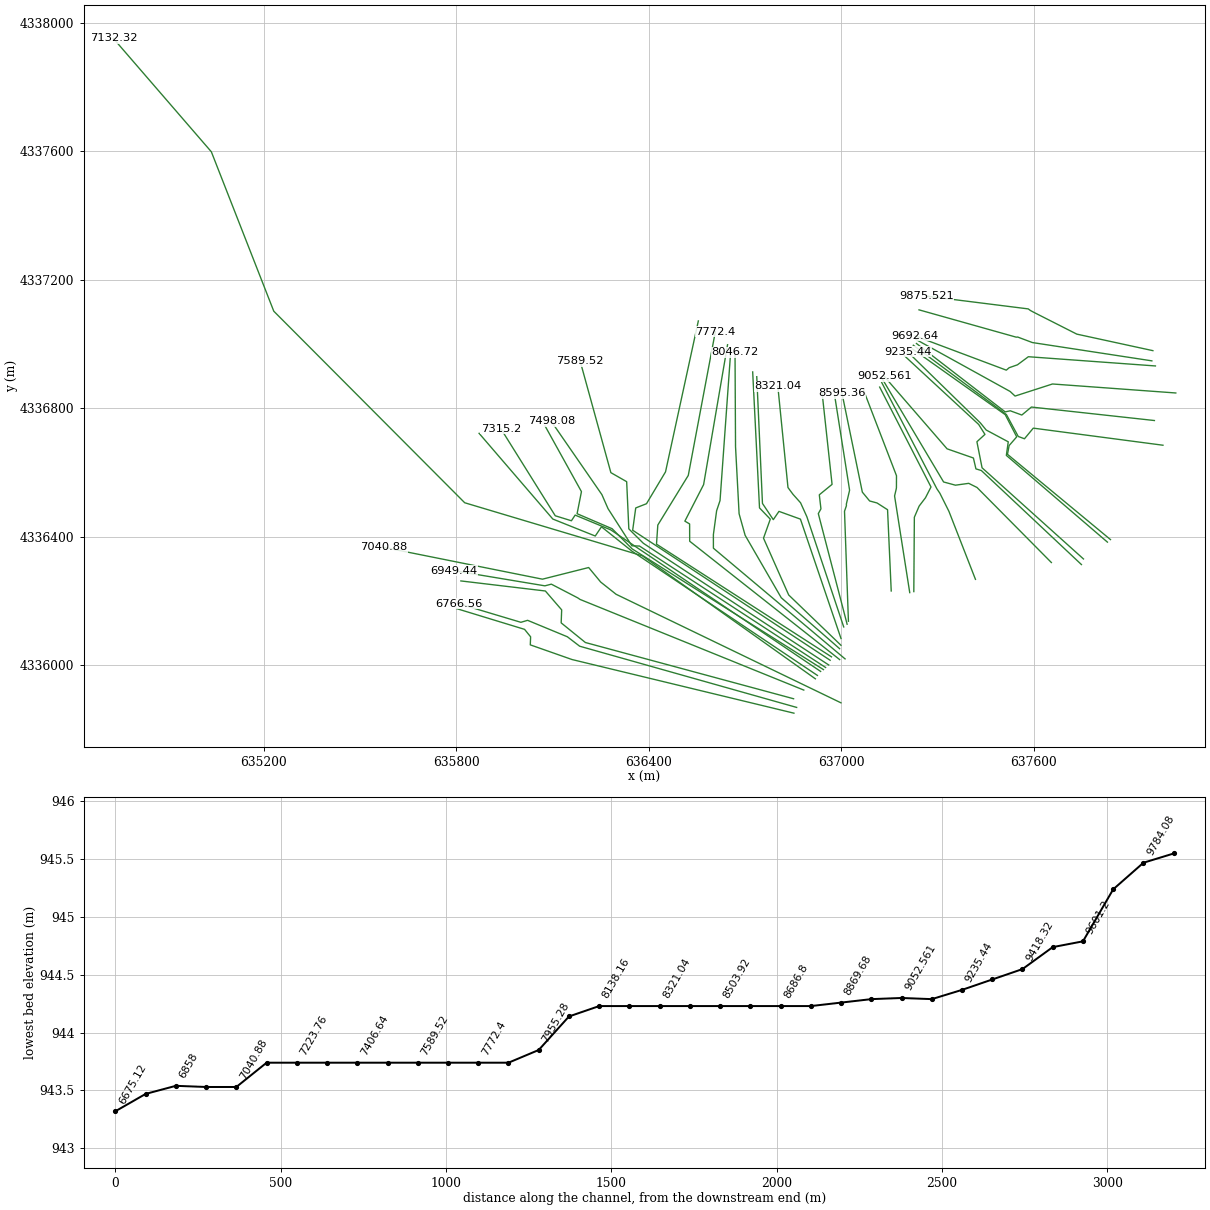
HEC-RAS study BeaverCreek.prj: BeaverCreek

--- BeaverCreek.g01 (geometry) --- (continued)

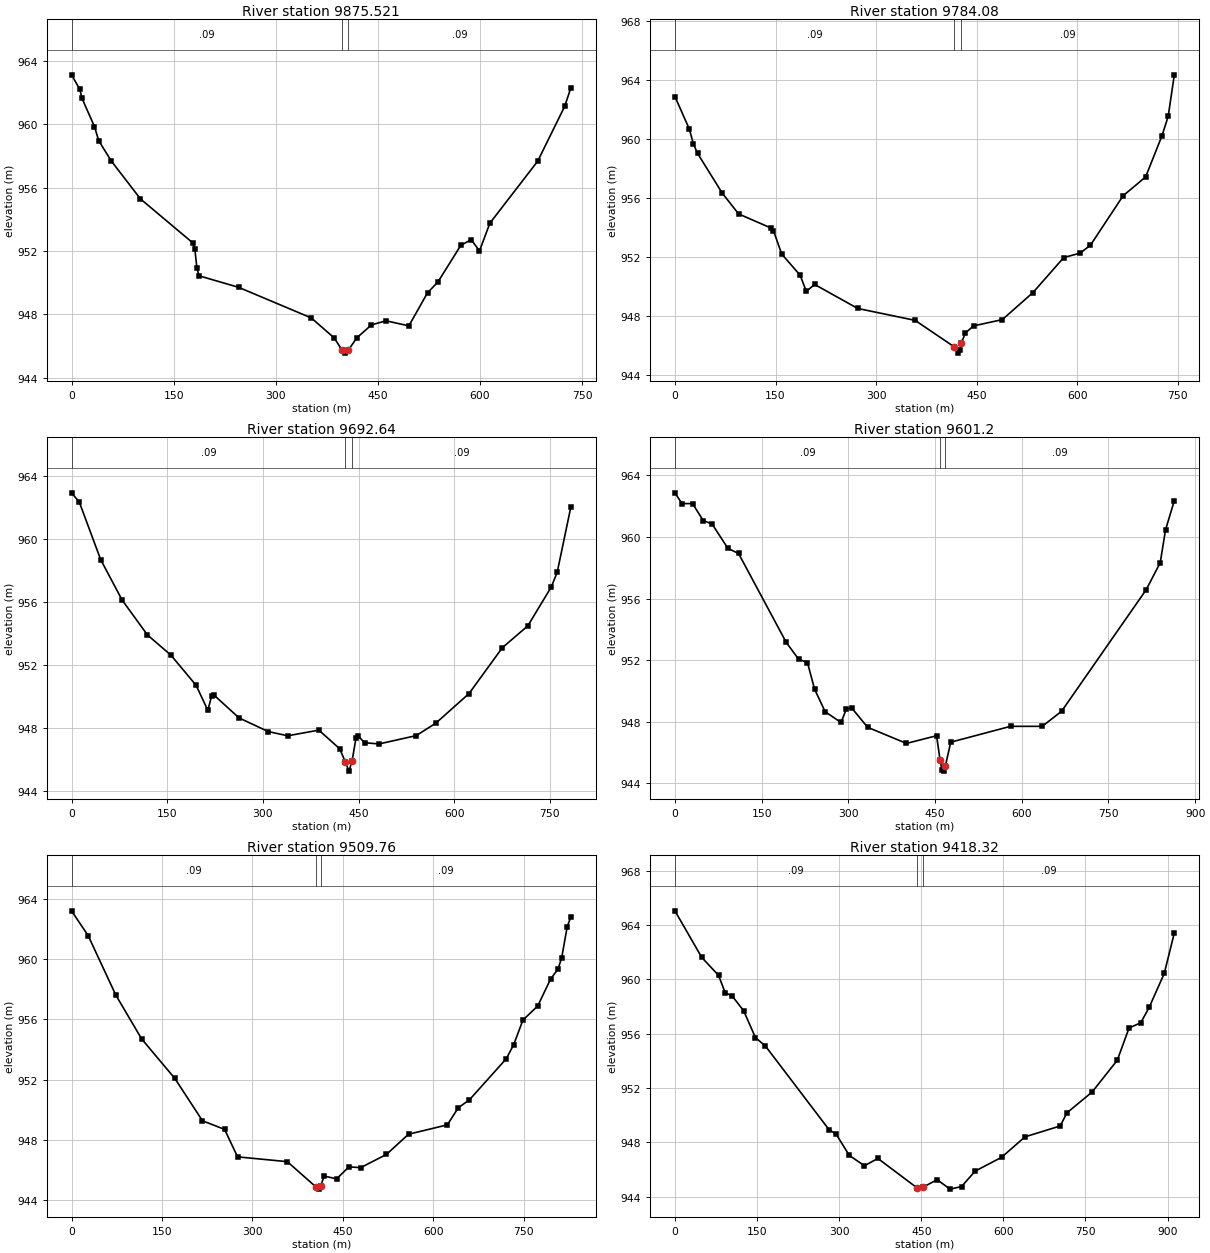
Type RM Length L Ch R = 1 ,9875.521,89.25,91.44,95.12
XS GIS Cut Line= 6
     637970.7219    4336978.9865     637733.6805    4337030.4225
     637600.4022    4337097.9527     637589.3874    4337103.8373
      637582.316    4337108.9603     637264.2829    4337148.8494
#Sta/Elev= 30
       0  963.11   12.28  962.19   15.35  961.63   33.77  959.84   39.91  958.96
   58.34  957.68  101.32  955.28  178.08  952.51  181.15  952.14  184.22  950.92
  187.29  950.43  245.61   949.7  352.33  947.77  385.87  946.51  397.42  945.75
   401.8  945.55  406.82  945.75  419.29  946.52  440.66  947.33  462.03  947.59
  495.61  947.27  523.08  949.36  538.35  950.04  571.93  952.35  587.19  952.71
   599.4     952  614.66  953.75  684.87  957.66  724.56  961.12  733.71   962.3
#Mann= 3 , 0 , 0
       0     .09       0  397.42     .04       0  406.82     .09       0
Bank Sta=397.42,406.82
XS Rating Curve= 0 ,0
Exp/Cntr=0.3,0.1

Type RM Length L Ch R = 1 ,9784.08 ,69.14,91.44,108.77
XS GIS Cut Line= 5
     637967.5469    4336947.2365     637595.2674     4337004.174
     637549.4939    4337021.3708     637544.8768    4337020.9641
     637242.0579    4337105.9868
#Sta/Elev= 30
       0  962.87   21.43  960.67   27.56  959.66   33.68  959.02   70.42  956.33
   94.92  954.91  143.91  953.94  146.97  953.77  159.22  952.19  186.77  950.75
  195.96  949.65  208.21  950.13  272.51   948.5  358.24  947.69  416.34   945.9
  422.45  945.47  425.51  945.71  426.94  946.14  433.19  946.84  445.41  947.32
  488.16  947.74  533.97  949.58  579.77  951.95   604.2  952.25  619.47  952.78
  668.33  956.14  701.92  957.42  726.35  960.22  735.51  961.52  744.67  964.34
#Mann= 3 , 0 , 0
       0     .09       0  416.34     .04       0  426.94     .09       0
Bank Sta=416.34,426.94
XS Rating Curve= 0 ,0
Exp/Cntr=0.3,0.1

Type RM Length L Ch R = 1 ,9692.64 ,97.49,91.44,83.77
XS GIS Cut Line= 6
     637978.6594    4336931.3614     637582.7655    4336960.0781
     637548.7342    4336934.8896     637522.9825    4336925.8903
     637514.0528    4336918.2835     637229.3579    4337025.0241
#Sta/Elev= 30
       0  962.96   12.21  962.37    45.8   958.7   79.39  956.13  119.08  953.91
  155.72  952.63  195.41   950.7  213.73  949.11  219.84  950.05  222.89   950.1
  262.59  948.63  308.39  947.76  338.92  947.49  387.77  947.85  420.62  946.66
   429.5   945.8  435.03  945.24  439.89  945.89  445.85  947.32  448.82   947.5
  459.49  947.05  481.98  946.97  540.33   947.5  571.04  948.29  623.25  950.18
  675.46   953.1  715.39  954.49  752.24  956.97  761.45   957.9  782.95  962.08
#Mann= 3 , 0 , 0
       0     .09       0   429.5     .04       0  439.89     .09       0
Bank Sta=429.5,439.89
XS Rating Curve= 0 ,0
Exp/Cntr=0.3,0.1

Type RM Length L Ch R = 1 ,9601.2  ,63.84,91.44,61.22
XS GIS Cut Line= 5
     638042.1595    4336847.2238     637657.9136    4336875.2213
     637541.3216    4336837.6111     637525.9591    4336851.9501
     637232.5329    4337013.9116
#Sta/Elev= 30
       0  962.87   12.23  962.17   30.58  962.17   48.92  961.07   64.21  960.85
   91.73  959.26  110.08  958.93  192.63  953.15  214.04  952.06  229.32  951.84
  241.55  950.12   259.9  948.65  287.42  947.95  296.59  948.83  305.77   948.9
  333.28  947.64  400.58  946.59  452.64  947.09  458.77   945.5  461.83  944.88
  464.89  944.79  467.96  945.14  477.15  946.67  580.58   947.7  635.43   947.7
  668.94  948.68  815.19  956.57  839.57  958.33  848.71  960.46  863.94  962.36
#Mann= 3 , 0 , 0
       0     .09       0  458.77     .04       0  467.96     .09       0
Bank Sta=458.77,467.96
XS Rating Curve= 0 ,0
Exp/Cntr=0.3,0.1

Type RM Length L Ch R = 1 ,9509.76 ,76.98,91.44,17.81
XS GIS Cut Line= 6
     637975.4844    4336761.4986     637592.2638    4336803.4431
     637562.3658    4336778.5722     637526.3824    4336791.8014
     637510.5074    4336788.3618     637234.1204    4337001.2116
#Sta/Elev= 30
       0  963.19   27.54  961.55   73.43  957.61  116.26   954.7  171.34  952.08
  217.23  949.27  253.95   948.7  275.36  946.88  357.97  946.56  406.15  944.86
  410.86  944.74  413.21  944.94  419.03  945.61   439.6  945.42  460.24  946.22
  479.44  946.16  522.28  947.04     559  948.38  623.26     949  641.62  950.14
  659.98  950.66  721.18  953.39  733.42  954.32  748.72  955.95   773.2  956.88
  794.63  958.67  806.87  959.33  812.99  960.08  822.17  962.14  828.29   962.8
#Mann= 3 , 0 , 0
       0     .09       0  406.15     .04       0  413.21     .09       0
Bank Sta=406.15,413.21
XS Rating Curve= 0 ,0
Exp/Cntr=0.3,0.1

Type RM Length L Ch R = 1 ,9418.32 ,139.64,91.44,3.67
XS GIS Cut Line= 6
     638002.1346    4336684.6039     637598.1243    4336737.7654
     637570.6076    4336704.6925      637551.293    4336711.8362
     637514.4136    4336779.9724      637224.258    4336995.7545
#Sta/Elev= 30
       0  965.04   49.02  961.61   79.66  960.29   91.92     959  104.17  958.79
  125.62  957.68  147.07  955.71  165.45  955.08  281.87  948.91  294.13  948.62
  318.64  947.03  346.22  946.27  370.73  946.81  442.75  944.63  452.46  944.68
     479  945.24  502.75  944.55  523.54  944.74  548.56  945.88  596.64  946.89
  639.54   948.4  703.89   949.2  716.15  950.17  762.12   951.7  808.08  954.04
  829.53  956.41  850.98   956.8  866.31  957.93  893.89  960.43  912.27  963.41
#Mann= 3 , 0 , 0
       0     .09       0  442.75     .04       0  452.46     .09       0
Bank Sta=442.75,452.46
XS Rating Curve= 0 ,0
Exp/Cntr=0.3,0.1

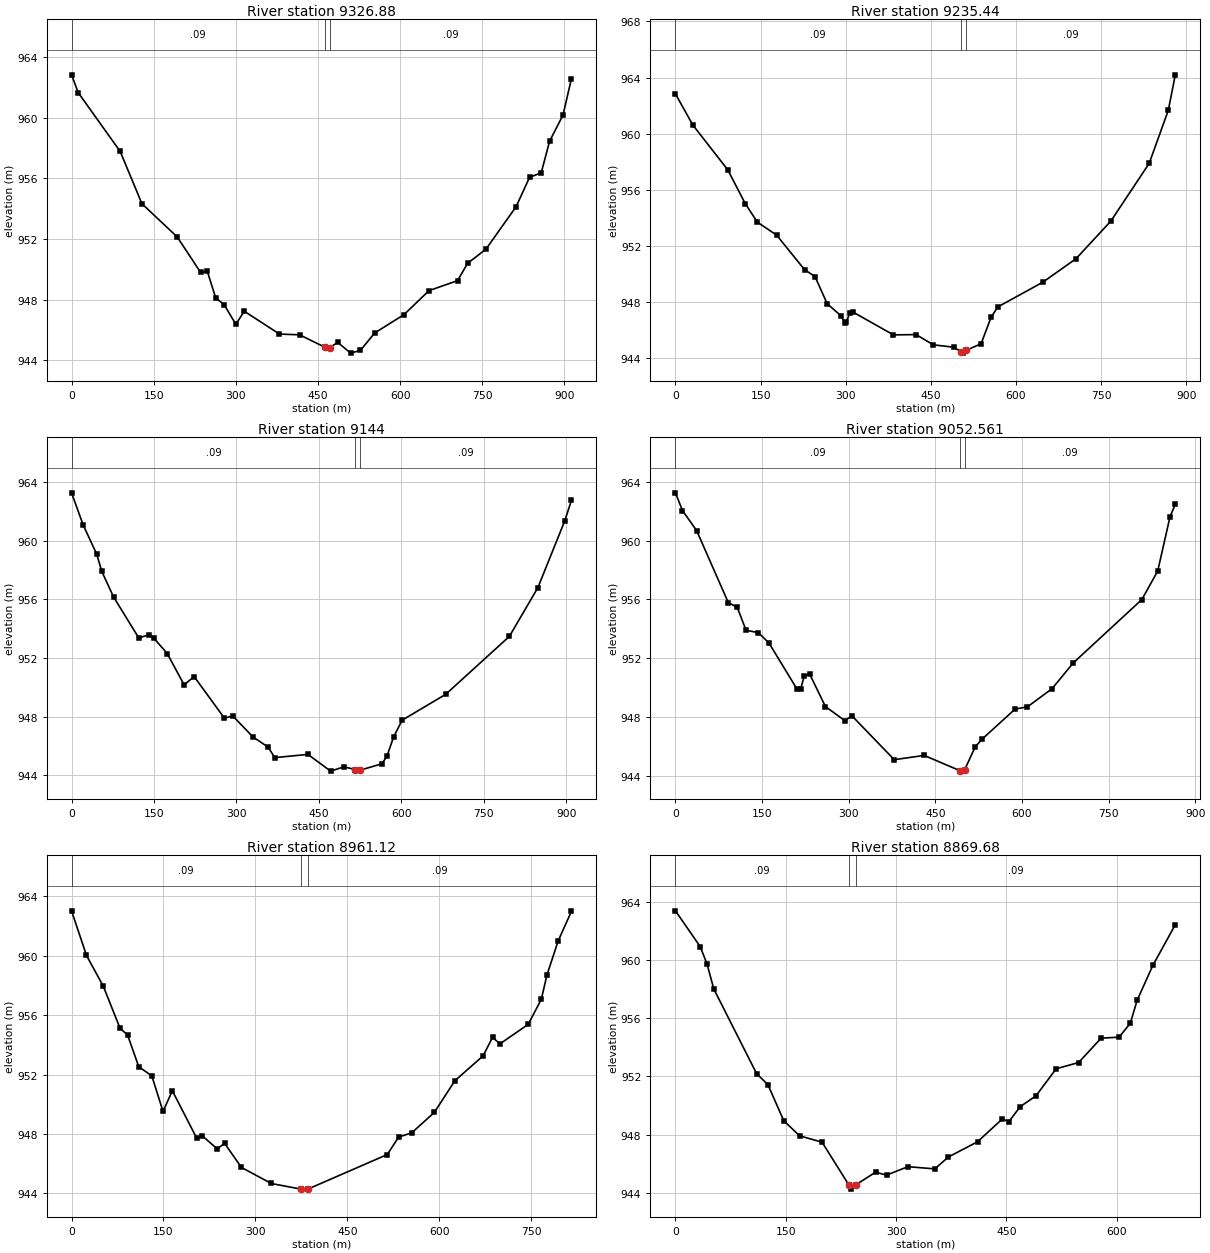
Type RM Length L Ch R = 1 ,9326.88 ,3.36,91.44,79.26
XS GIS Cut Line= 6
     637838.6218    4336390.9158     637517.6776    4336656.3133
     637522.8034    4336683.5242     637546.4745    4336710.6757
     637510.6926    4336779.7152      637221.083     4336984.642
#Sta/Elev= 30
       0  962.85   12.25  961.67    88.8  957.79  128.61  954.33  192.92  952.14
  235.79  949.79  248.04  949.86  263.35   948.1  278.66  947.67   300.1  946.36
  315.41  947.23  379.72  945.72  416.46  945.67  462.16  944.86  471.17  944.82
   486.1  945.17  509.79  944.46  527.55  944.64  553.52  945.79  607.01     947
  652.89  948.59  704.88  949.25  723.23  950.39  756.88  951.33  811.93  954.14
  836.39  956.07   857.8  956.38   873.1  958.47  897.56  960.19  912.86  962.59
#Mann= 3 , 0 , 0
       0     .09       0  462.16     .04       0  471.17     .09       0
Bank Sta=462.16,471.17
XS Rating Curve= 0 ,0
Exp/Cntr=0.3,0.1

Type RM Length L Ch R = 1 ,9235.44 ,95.72,91.44,8.14
XS GIS Cut Line= 6
     637829.0967    4336382.9783     637514.1851    4336652.9266
     637520.1264    4336695.1643     637451.3464    4336731.9711
     637432.8256    4336754.4607     637206.7955     4336975.117
#Sta/Elev= 30
       0  962.84   30.72  960.62   92.17  957.43   122.9  955.03   144.4   953.7
   178.2  952.78  227.36  950.32  245.79  949.83   267.3  947.89  291.88  947.02
  298.03  946.52   301.1  946.57  307.24  947.26  313.39  947.28  384.05  945.67
  423.92  945.69  454.39  944.96  490.67  944.79  502.76  944.47  505.78  944.37
  511.82  944.56   538.4  945.04  555.88  946.91  567.69  947.66  647.42  949.43
  705.69   951.1  767.02  953.78  834.49  957.89  868.23  961.68  880.49   964.2
#Mann= 3 , 0 , 0
       0     .09       0  502.76     .04       0  511.82     .09       0
Bank Sta=502.76,511.82
XS Rating Curve= 0 ,0
Exp/Cntr=0.3,0.1

Type RM Length L Ch R = 1 ,9144    ,23.44,91.44,110.3
XS GIS Cut Line= 6
     637754.4841    4336330.5907     637438.5042    4336614.3569
     637422.4656    4336695.4455        637447.5    4336718.3384
     637427.9208    4336749.2947     637197.2705     4336962.417
#Sta/Elev= 30
       0  963.25   21.39  961.04   45.83  959.07      55   957.9   76.38  956.16
  122.21  953.37  140.55  953.57  149.71  953.35  174.16   952.3  204.71  950.17
  223.04  950.73  278.04   947.9  293.32  948.05  329.98  946.62  357.48  945.93
   369.7  945.21  429.99  945.43  471.25  944.29  495.48  944.58  515.95   944.4
  524.29  944.35  564.64  944.79   573.8  945.32  586.01  946.63  601.27  947.76
  680.54  949.52   796.4  953.47  848.23  956.79  897.01  961.33  909.21  962.73
#Mann= 3 , 0 , 0
       0     .09       0  515.95     .04       0  524.29     .09       0
Bank Sta=515.95,524.29
XS Rating Curve= 0 ,0
Exp/Cntr=0.3,0.1

Type RM Length L Ch R = 1 ,9052.561,52.68,91.44,100.09
XS GIS Cut Line= 6
     637748.1341    4336313.1282     637436.2161    4336605.8728
     637419.4145    4336610.9482     637411.5329    4336644.8435
     637329.5387    4336673.3632     637133.7703    4336898.9168
#Sta/Elev= 30
       0  963.26   12.22  962.05   36.67  960.69   91.67  955.77  106.94  955.47
  122.22   953.9  143.61  953.73  161.94  953.03  210.83  949.87  216.94  949.92
  223.05  950.77  232.22  950.93  259.72   948.7  293.33  947.74  305.55  948.07
  378.89  945.08   430.7  945.37   492.1  944.34  495.09   944.3  501.08  944.41
  519.04  945.95  531.02  946.48  588.27  948.53  609.61  948.68  652.27  949.92
  688.84  951.67   807.7  955.99  835.13  957.93  856.46  961.63   865.6  962.48
#Mann= 3 , 0 , 0
       0     .09       0   492.1     .04       0  501.08     .09       0
Bank Sta=492.1,501.08
XS Rating Curve= 0 ,0
Exp/Cntr=0.3,0.1

Type RM Length L Ch R = 1 ,8961.12 ,116.64,91.44,42.81
XS GIS Cut Line= 6
     637654.4714    4336319.4782     637422.7668    4336553.0837
     637396.8904    4336565.9425     637355.5526    4336560.2058
     637318.6265    4336570.2287     637125.8328    4336894.1543
#Sta/Elev= 30
       0  963.02   24.37  960.02   51.79  957.95   79.21  955.11    91.4  954.67
  109.68  952.53     131  951.91  149.28  949.52  164.51  950.91  204.12  947.73
  213.26  947.88  237.63     947  249.82  947.37  277.24  945.75  325.98  944.67
  374.39  944.29  385.56  944.29  515.32  946.62  533.71  947.79  555.17  948.08
  591.94  949.45  625.65  951.59  671.62  953.26  686.95   954.5  699.21  954.07
  745.18  955.38  766.63  957.07  775.82  958.71  794.21  961.01  815.67  962.98
#Mann= 3 , 0 , 0
       0     .09       0  374.39     .04       0  385.56     .09       0
Bank Sta=374.39,385.56
XS Rating Curve= 0 ,0
Exp/Cntr=0.3,0.1

Type RM Length L Ch R = 1 ,8869.68 ,106.61,91.44,33.89
XS GIS Cut Line= 5
     637417.9334    4336267.0906     637335.3212    4336478.5889
      637307.085    4336535.0618     637297.7509    4336548.9156
     637125.8328    4336879.8668
#Sta/Elev= 30
       0  963.36   33.75   960.9   42.96  959.71   52.16     958  110.46  952.18
   125.8  951.43  147.28  948.96  168.76  947.92  199.44  947.48  236.08  944.53
  239.09  944.26   245.1  944.55  272.16  945.42  287.19  945.22  316.07   945.8
  352.76  945.65   371.1  946.46  410.84  947.51  444.46  949.07  453.63   948.9
  468.92  949.92  490.32  950.66  517.83  952.52   548.4  952.95  578.97  954.62
  603.42  954.69  618.71  955.65  627.88  957.21  649.27  959.61  679.84  962.41
#Mann= 3 , 0 , 0
       0     .09       0  236.08     .04       0   245.1     .09       0
Bank Sta=236.08,245.1
XS Rating Curve= 0 ,0
Exp/Cntr=0.3,0.1

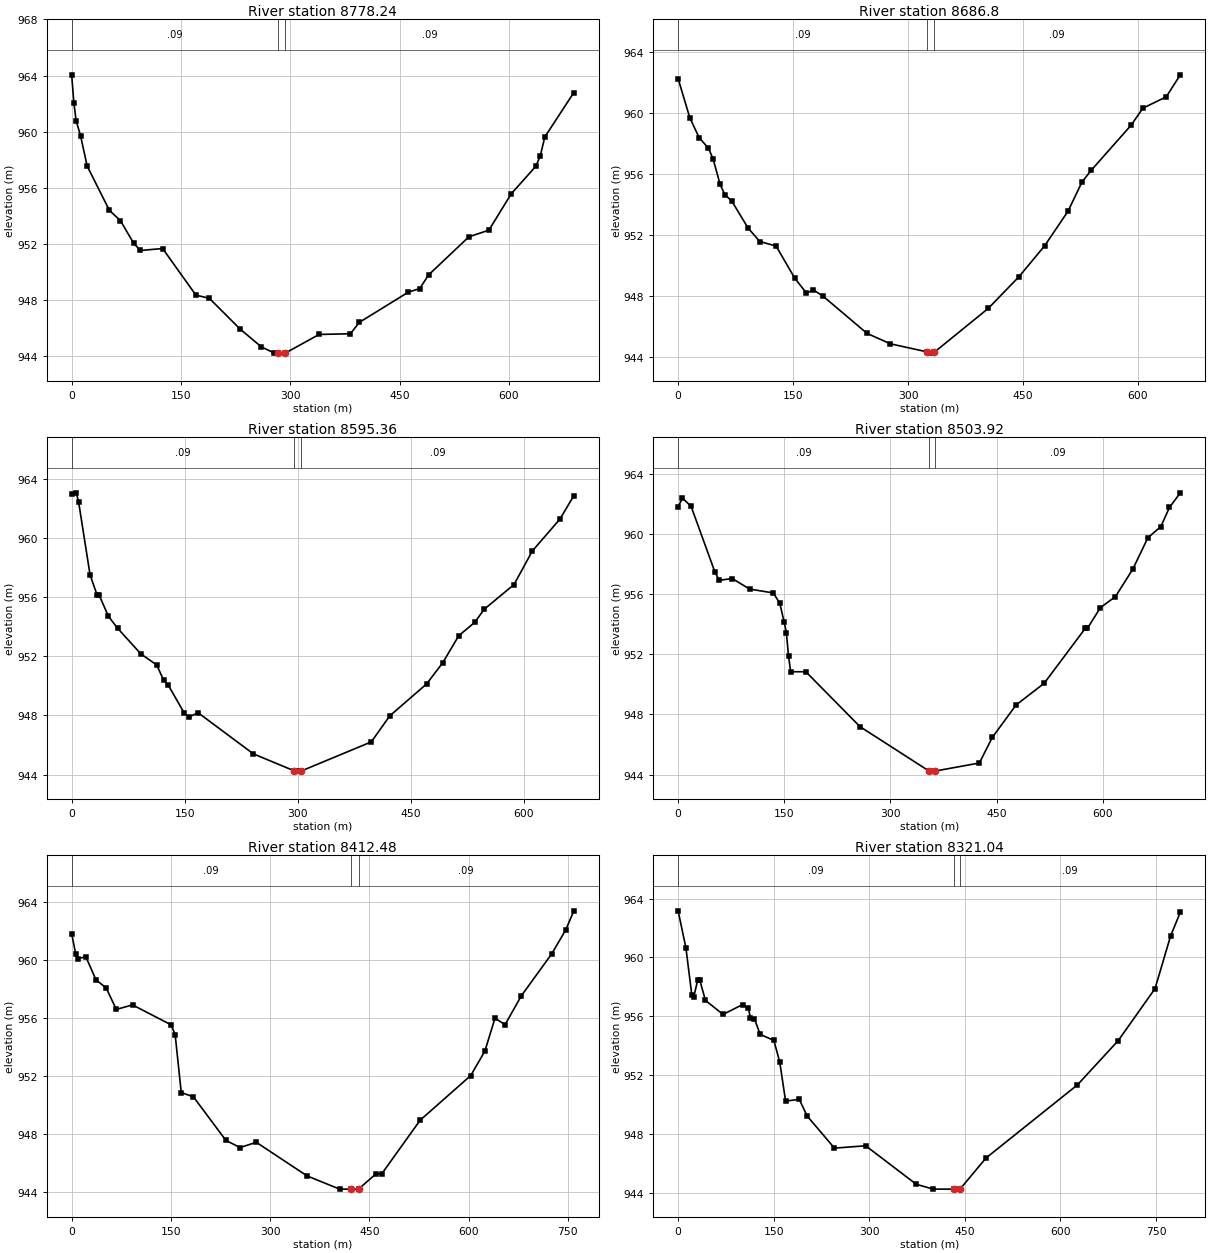
Type RM Length L Ch R = 1 ,8778.24 ,69.94,91.44,108.38
XS GIS Cut Line= 6
     637225.8455    4336228.9905     637227.5303    4336460.4529
     637242.4754    4336495.2039     637262.1908    4336521.0426
     637279.3888    4336554.6447     637119.4828    4336865.5793
#Sta/Elev= 30
       0  964.05    3.05  962.06    6.09  960.79   12.18  959.72   21.32  957.55
   51.78   954.4      67  953.66   85.28  952.04   94.41  951.54  124.87  951.68
  170.56  948.36  188.83  948.14  231.47  945.93  260.57  944.67  278.32  944.23
  282.92  944.23  293.16  944.23  339.63  945.56  382.57  945.61  394.84  946.42
  462.31  948.58  477.65  948.82  489.92   949.8  545.12  952.51  572.73  952.99
   603.4  955.58  637.13  957.54  643.27  958.29   649.4  959.62  689.27  962.79
#Mann= 3 , 0 , 0
       0     .09       0  282.92     .04       0  293.16     .09       0
Bank Sta=282.92,293.16
XS Rating Curve= 0 ,0
Exp/Cntr=0.3,0.1

Type RM Length L Ch R = 1 ,8686.8  ,37.99,91.44,113.76
XS GIS Cut Line= 6
     637213.1455    4336225.8155     637165.9109    4336526.6112
     637171.1032    4336548.4904     637171.6957    4336552.7173
     637171.8641    4336589.7145     637068.6827    4336857.6417
#Sta/Elev= 30
       0  962.23   15.22  959.67    27.4  958.36   39.58  957.67   45.67  956.96
   54.81  955.29    60.9  954.63   70.03   954.2   91.34  952.43  106.57  951.55
  127.88  951.25  152.24  949.14  167.46  948.17   176.6  948.37  188.78  947.98
  246.63  945.52  277.08  944.84  325.13  944.31   329.1  944.23  334.08  944.28
  404.89  947.17  444.59  949.23  478.19  951.26  508.73  953.53  527.06  955.45
  539.28  956.23   591.2  959.18  606.47  960.29  637.02  961.04  655.34  962.48
#Mann= 3 , 0 , 0
       0     .09       0  325.13     .04       0  334.08     .09       0
Bank Sta=325.13,334.08
XS Rating Curve= 0 ,0
Exp/Cntr=0.3,0.1

Type RM Length L Ch R = 1 ,8595.36 ,137.96,91.44,47.53
XS GIS Cut Line= 6
     637155.4662    4336230.8955     637144.0497    4336483.8478
     637111.2081    4336504.8496     637088.1668    4336511.1168
     637065.4683    4336538.6167     637002.0076    4336846.5292
#Sta/Elev= 30
       0  962.99     6.1  963.07    9.15  962.48   24.41  957.52   33.56  956.18
   36.61  956.13   48.81  954.71   61.01   953.9   91.52  952.18  112.88  951.41
  122.03  950.38  128.13  950.05  149.49  948.15  155.59   947.9  167.79  948.18
  241.01   945.4  295.18  944.25  298.16  944.23  304.13  944.23  397.51  946.21
  421.93  947.97  470.77  950.13  492.13  951.56   513.5   953.4  534.86  954.31
  547.07  955.18  586.75  956.86  611.17  959.14   647.8   961.3  666.11  962.88
#Mann= 3 , 0 , 0
       0     .09       0  295.18     .04       0  304.13     .09       0
Bank Sta=295.18,304.13
XS Rating Curve= 0 ,0
Exp/Cntr=0.3,0.1

Type RM Length L Ch R = 1 ,8503.92 ,82.65,91.44,64.16
XS GIS Cut Line= 6
      637022.116    4336136.7036     637009.9306    4336479.0329
     637015.8527    4336496.3202     637015.6472    4336501.2575
     637025.7609    4336544.6161      636979.077    4336840.1439
#Sta/Elev= 30
       0  961.81    6.12  962.39   18.35  961.84   51.99  957.47   58.11  956.92
   76.46  957.04  100.93  956.34  134.57  956.08  143.75  955.38  149.86  954.13
  152.92  953.45  155.98  951.88  159.04  950.84  180.45  950.84  256.91  947.19
  354.73  944.23  362.36  944.23  425.55  944.77  443.87  946.47  477.45  948.63
  517.14  950.07  575.14  953.72   578.2  953.72  596.52   955.1  617.89  955.84
  642.31  957.66  663.68  959.75     682   960.5  694.21  961.77  709.48  962.74
#Mann= 3 , 0 , 0
       0     .09       0  354.73     .04       0  362.36     .09       0
Bank Sta=354.73,362.36
XS Rating Curve= 0 ,0
Exp/Cntr=0.3,0.1

Type RM Length L Ch R = 1 ,8412.48 ,49.88,91.44,133.01
XS GIS Cut Line= 6
     637018.0237    4336127.4608     636928.2805    4336471.7343
     636936.4826     4336486.551     636931.3967    4336530.3001
      636971.143    4336562.7512     636939.7069    4336851.3623
#Sta/Elev= 30
       0   961.8    6.13   960.4     9.2  960.08   21.47  960.21    36.8  958.62
   52.14  958.07   67.48  956.59   92.01   956.9  150.29  955.53  156.42  954.86
  165.62  950.87  184.02  950.58   233.1  947.58  254.57  947.09   279.1  947.45
  355.78  945.14  405.01  944.23  421.87  944.23  433.54  944.23  459.57  945.27
  468.61  945.28  526.68  948.97  603.08  952.04  624.47  953.72  639.75  955.99
  655.03  955.54  679.48  957.52  725.32   960.4  746.71  962.06  758.93  963.37
#Mann= 3 , 0 , 0
       0     .09       0  421.87     .04       0  433.54     .09       0
Bank Sta=421.87,433.54
XS Rating Curve= 0 ,0
Exp/Cntr=0.3,0.1

Type RM Length L Ch R = 1 ,8321.04 ,31.89,91.44,95.18
XS GIS Cut Line= 6
     637007.4404    4336118.9942     636892.5705    4336462.1586
     636873.0492    4336505.3722     636849.3904     4336531.797
      636833.784    4336552.8358     636802.1233    4336868.2957
#Sta/Elev= 30
       0  963.17   12.27  960.64   21.47  957.45   24.53  957.32   30.67  958.44
   33.73  958.49   42.93  957.07   70.54  956.12   101.2  956.79   110.4  956.53
  113.47   955.9   119.6  955.84   128.8  954.76  150.27  954.35  159.47  952.88
  168.67  950.22  190.14  950.34  202.41  949.21  245.34  947.02  294.41  947.18
  373.73  944.56  400.41  944.23  433.01  944.23  442.37  944.23  483.26  946.35
  626.54  951.32  690.56  954.33  748.48  957.88  772.87  961.46  788.11  963.07
#Mann= 3 , 0 , 0
       0     .09       0  433.01     .04       0  442.37     .09       0
Bank Sta=433.01,442.37
XS Rating Curve= 0 ,0
Exp/Cntr=0.3,0.1

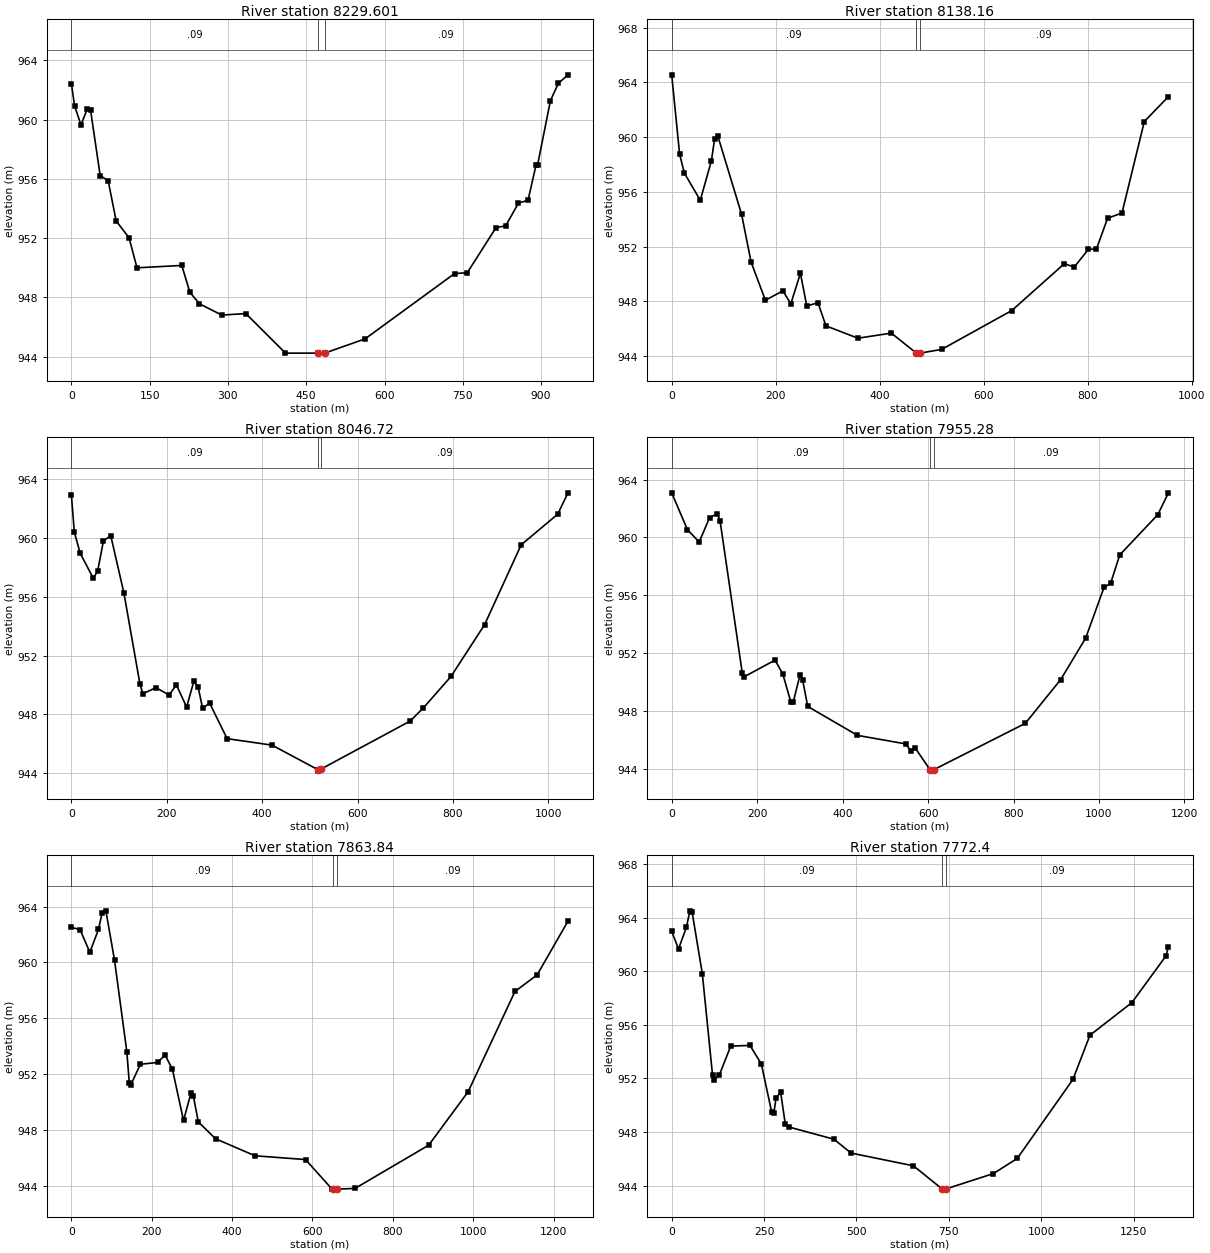
Type RM Length L Ch R = 1 ,8229.601,140.13,91.44,18.84
XS GIS Cut Line= 6
     636998.9737    4336083.0107     636872.5415     4336454.565
     636805.6713    4336478.6923     636788.0069    4336452.9775
     636754.2725    4336503.3807     636736.5065     4336897.929
#Sta/Elev= 30
       0  962.43    6.13  960.93    18.4  959.64   30.66  960.73   36.79  960.63
   55.19  956.22   70.52  955.87   85.85  953.15  110.38  952.03  125.72  949.99
  211.57  950.15   226.9  948.35   245.3  947.56  288.22   946.8  334.22   946.9
  410.25  944.23  471.72  944.23  485.27  944.23  562.64  945.19  734.09   949.6
  758.58  949.66  813.69  952.71  832.06  952.82  856.55  954.36  874.92  954.55
  890.23  956.92  893.29  956.94  917.79  961.27  933.09  962.45  951.46  963.02
#Mann= 3 , 0 , 0
       0     .09       0  471.72     .04       0  485.27     .09       0
Bank Sta=471.72,485.27
XS Rating Curve= 0 ,0
Exp/Cntr=0.3,0.1

Type RM Length L Ch R = 1 ,8138.16 ,63.39,91.44,64.58
XS GIS Cut Line= 6
     636998.9737     4336061.844       636835.99    4336218.4777
      636757.518    4336395.2806     636778.6704    4336454.4154
     636745.0826    4336489.4725     636723.8065    4336912.7457
#Sta/Elev= 30
       0  964.55   15.27  958.75   24.44  957.37   54.98  955.39   76.37  958.27
   82.48  959.86   88.59   960.1  134.41  954.37  152.74  950.87  180.23  948.09
  213.83  948.78  229.12  947.83  247.54  950.06  259.82  947.67  281.32  947.91
  296.67  946.22  358.08  945.32  422.48  945.69  470.56  944.23  477.27  944.23
   519.1   944.5  654.07  947.34  755.42  950.77  773.85   950.5  801.48  951.81
  816.84  951.83  838.34  954.08  865.98  954.46  908.97  961.14  955.04  962.95
#Mann= 3 , 0 , 0
       0     .09       0  470.56     .04       0  477.27     .09       0
Bank Sta=470.56,477.27
XS Rating Curve= 0 ,0
Exp/Cntr=0.3,0.1

Type RM Length L Ch R = 1 ,8046.72 ,103.67,91.44,64.95
XS GIS Cut Line= 6
     636994.7403    4336051.2607     636812.7066     4336210.011
     636700.2489    4336404.2235     636681.4823    4336471.1738
     636670.3678    4336679.8842      636668.773    4336974.1292
#Sta/Elev= 30
       0  962.96    6.11  960.42   18.34  958.98   45.86  957.27   55.03  957.75
   67.26  959.81   82.55  960.16  110.07  956.27   143.7  950.08  149.81  949.41
  177.33  949.82  204.84  949.32  220.13  950.01  241.53   948.5   256.7  950.25
  265.79  949.85  274.89  948.44  290.06  948.75  326.45  946.35  420.46  945.91
  516.14  944.25  517.42  944.14  523.19  944.28  709.76  947.54  737.42  948.43
  795.68  950.58  866.18  954.11  942.81  959.54 1019.43  961.63 1040.89  963.08
#Mann= 3 , 0 , 0
       0     .09       0  516.14     .04       0  523.19     .09       0
Bank Sta=516.14,523.19
XS Rating Curve= 0 ,0
Exp/Cntr=0.3,0.1

Type RM Length L Ch R = 1 ,7955.28 ,73.92,91.44,70.86
XS GIS Cut Line= 6
     637011.6737    4336019.5106     636601.4268     4336364.095
     636601.3729    4336406.5075     636611.4221    4336480.5916
     636622.0643    4336512.2619      636656.073    4336986.8292
#Sta/Elev= 30
       0  963.08   36.74  960.54   64.29  959.68   88.78  961.37  107.15  961.63
  113.28  961.13  165.32   950.6  168.38  950.35  241.86  951.52  260.23  950.55
   278.6  948.64  284.72  948.65  300.03  950.46  306.15  950.18   318.4  948.32
  434.73  946.32  547.88  945.73     560  945.22  569.09  945.48  605.09  943.93
  608.08  943.85  614.06  943.96  827.55  947.15  910.43  950.18  968.75  953.04
 1011.72  956.54 1027.07  956.82 1048.56  958.79 1137.58  961.57 1162.14  963.06
#Mann= 3 , 0 , 0
       0     .09       0  605.09     .04       0  614.06     .09       0
Bank Sta=605.09,614.06
XS Rating Curve= 0 ,0
Exp/Cntr=0.3,0.1

Type RM Length L Ch R = 1 ,7863.84 ,102.13,91.44,58.85
XS GIS Cut Line= 6
     636994.7403     4336017.394     636527.5021    4336385.7909
     636527.2904    4336439.5543     636512.5004    4336448.3312
     636570.9044    4336562.0064     636645.4896    4336997.4126
#Sta/Elev= 30
       0   962.5   21.47  962.35   46.01  960.72   67.47  962.36   76.68  963.55
   85.88  963.69  107.35  960.16  138.02  953.59  144.15  951.34  147.22  951.17
  171.75  952.69  214.69  952.82  233.09  953.36   251.5  952.33   279.1  948.66
   297.5   950.6  303.64   950.4   315.9  948.56  358.84  947.35  456.99  946.13
  582.73  945.86  648.77  943.74  652.18  943.74  661.33  943.74  705.87  943.79
  889.21  946.89  987.37  950.72 1103.95  957.91 1159.16   959.1 1235.86  962.95
#Mann= 3 , 0 , 0
       0     .09       0  652.18     .04       0  661.33     .09       0
Bank Sta=652.18,661.33
XS Rating Curve= 0 ,0
Exp/Cntr=0.3,0.1

Type RM Length L Ch R = 1 ,7772.4  ,82.21,91.44,66.11
XS GIS Cut Line= 5
     636969.3403    4336025.8606     636424.1265    4336376.6654
     636428.1902    4336436.1384     636523.1289    4336590.6235
     636607.3896    4337037.6293
#Sta/Elev= 30
       0  962.97   18.44  961.65   39.94  963.28   49.16   964.5   55.31   964.4
   82.96   959.8  110.61  952.23  113.69  951.85  129.05  952.26  159.78  954.41
  212.01  954.46  242.74  953.07  270.39  949.52  276.54  949.41  282.68  950.57
  294.97  950.95  307.26  948.63  316.48  948.38  439.38  947.46  485.47  946.43
  654.28  945.48  732.52  943.74  741.74  943.75  870.82   944.9  935.36  946.03
 1085.96  951.92 1132.07  955.22 1245.79  957.66 1337.99  961.14 1344.14   961.8
#Mann= 3 , 0 , 0
       0     .09       0  732.52     .04       0  741.74     .09       0
Bank Sta=732.52,741.74
XS Rating Curve= 0 ,0
Exp/Cntr=0.3,0.1

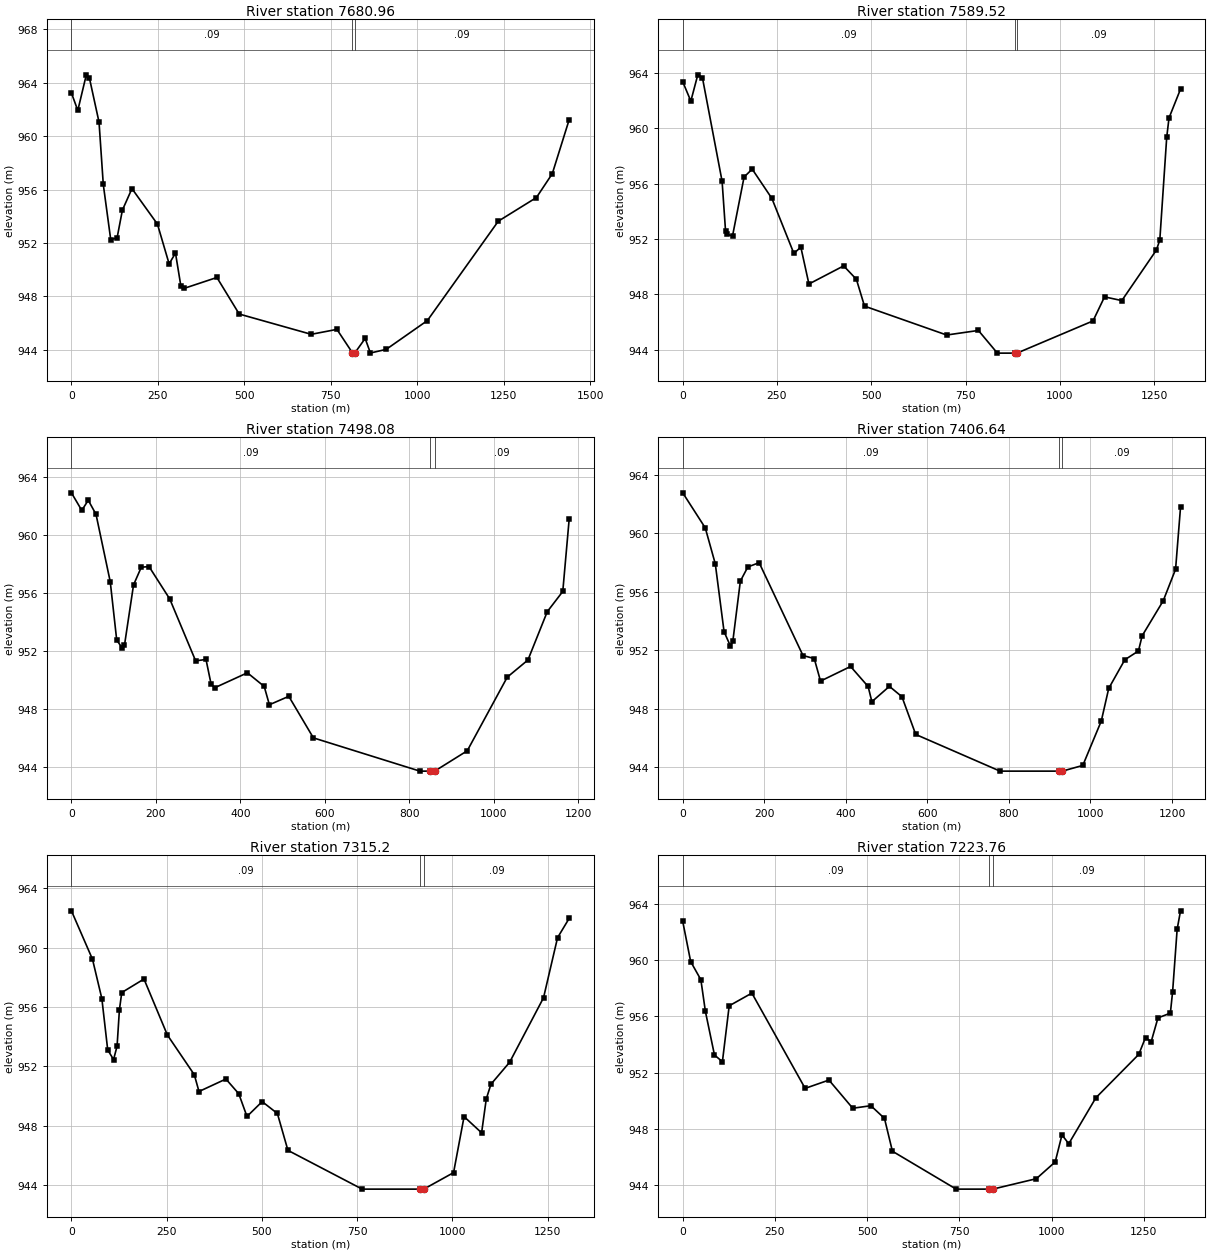
Type RM Length L Ch R = 1 ,7680.96 ,12.52,91.44,203.16
XS GIS Cut Line= 6
      636965.107    4336015.2773     636349.8472    4336419.9663
     636359.3912    4336489.3713     636392.9414    4336502.5406
     636452.2412    4336601.7354     636554.4728    4337071.4961
#Sta/Elev= 30
       0  963.24   18.43  961.93      43   964.6   52.21  964.34   79.85  961.05
   92.14  956.38  113.64  952.25  132.06  952.38  147.42  954.46  175.06  956.07
  248.77  953.41  282.56  950.43  300.98  951.24  316.34   948.8  325.55  948.59
  420.76  949.41  485.26  946.67  693.64  945.15  767.87  945.52  812.86  943.76
  816.48  943.74  819.33  943.74  849.59  944.84   864.8  943.75  910.42  944.02
 1029.51  946.18 1234.67  953.63 1344.91   955.4 1390.84  957.19 1439.84  961.25
#Mann= 3 , 0 , 0
       0     .09       0  812.86     .04       0  819.33     .09       0
Bank Sta=812.86,819.33
XS Rating Curve= 0 ,0
Exp/Cntr=0.3,0.1

Type RM Length L Ch R = 1 ,7589.52 ,73.99,91.44,72.03
XS GIS Cut Line= 6
     636960.8736    4336000.4606     636383.1313    4336379.3787
     636337.8875    4336424.2256     636331.1607    4336571.1278
      636281.928    4336599.2479     636186.1721    4336946.6125
#Sta/Elev= 30
       0  963.37    21.5  961.97   39.92  963.87    52.2  963.67  104.41  956.17
  113.62  952.55  116.69  952.35  132.04  952.21  162.75  956.48  184.24  957.05
  236.45  954.93  294.79  950.95  313.22  951.41  334.71  948.74  426.83  950.05
  460.61  949.08  482.11  947.14  700.02  945.05  784.18  945.38  834.52  943.74
  880.34  943.74  886.51  943.74 1088.23  946.07 1118.77  947.81 1164.57  947.54
 1256.17  951.19 1265.34  951.92 1283.66  959.35 1289.76  960.75  1320.3  962.84
#Mann= 3 , 0 , 0
       0     .09       0  880.34     .04       0  886.51     .09       0
Bank Sta=880.34,886.51
XS Rating Curve= 0 ,0
Exp/Cntr=0.3,0.1

Type RM Length L Ch R = 1 ,7498.08 ,9.48,91.44,59.41
XS GIS Cut Line= 6
     636950.9782    4335992.7877     636371.1556     4336370.762
      636347.343    4336371.5558     636273.1509    4336487.0585
     636253.9449    4336530.9014     636096.3194    4336758.7579
#Sta/Elev= 30
       0   962.9    24.5  961.69   39.81  962.39   58.19  961.42   91.88  956.78
  107.19  952.76  119.44  952.25  125.57  952.41     147  956.56  165.38  957.78
  183.75  957.82  232.76  955.59  294.01  951.33  318.51  951.43  330.76  949.71
  339.95  949.49  416.51  950.51  456.32  949.57  468.57  948.31  514.51  948.89
   572.7  946.03  824.81  943.74  849.59  943.74  859.83  943.74   936.9  945.14
 1031.63  950.21 1080.53  951.39 1126.36  954.72 1163.04  956.11 1178.31  961.13
#Mann= 3 , 0 , 0
       0     .09       0  849.59     .04       0  859.83     .09       0
Bank Sta=849.59,859.83
XS Rating Curve= 0 ,0
Exp/Cntr=0.3,0.1

Type RM Length L Ch R = 1 ,7406.64 ,3.49,91.44,110.04
XS GIS Cut Line= 6
     636944.3636    4335986.1731     636348.2073    4336361.9646
     636285.8978     4336424.671     636176.6899    4336471.4398
     636190.2508    4336540.1619     636076.8435     4336744.628
#Sta/Elev= 30
       0  962.78    55.3  960.38   79.88  957.92  101.39  953.28  116.75  952.31
  122.89  952.63  141.33  956.74  159.76  957.71  187.41     958  294.95  951.65
   322.6  951.44  337.96   949.9  411.69   950.9  454.71  949.53  463.92  948.49
  506.94  949.54  537.66  948.83  571.46  946.25  778.27  943.74  923.07  943.74
  931.01  943.74  981.28  944.13 1026.62  947.17 1044.84   949.4 1084.32  951.36
 1117.72  951.96 1126.83     953 1178.45  955.39 1208.81  957.55 1220.96  961.79
#Mann= 3 , 0 , 0
       0     .09       0  923.07     .04       0  931.01     .09       0
Bank Sta=923.07,931.01
XS Rating Curve= 0 ,0
Exp/Cntr=0.3,0.1

Type RM Length L Ch R = 1 ,7315.2  ,3.71,91.44,11.6
XS GIS Cut Line= 6
     636935.4559    4335980.5286     636281.7439     4336421.033
     636170.6187    4336467.0926      636159.028    4336449.4835
      636108.706     4336464.976     635939.5623    4336735.3864
#Sta/Elev= 30
       0  962.47   55.29  959.21   79.87  956.56   95.23  953.11  110.59  952.46
   119.8  953.36  125.95  955.81  132.09  956.97  190.45  957.88  251.89  954.11
  322.54  951.44  334.83  950.31  405.48  951.15  439.27  950.16  460.78  948.63
  500.71  949.63  540.64  948.83  568.29  946.35  763.25  943.74  914.23  943.74
   924.9  943.74 1003.09  944.85 1030.69  948.62 1076.69  947.53 1088.96  949.81
 1101.23   950.8  1150.3  952.28 1239.24  956.62 1276.04  960.66 1306.71  961.97
#Mann= 3 , 0 , 0
       0     .09       0  914.23     .04       0   924.9     .09       0
Bank Sta=914.23,924.9
XS Rating Curve= 0 ,0
Exp/Cntr=0.3,0.1

Type RM Length L Ch R = 1 ,7223.76 ,12.85,91.44,210.53
XS GIS Cut Line= 6
     636925.4679    4335968.0932     636347.6903    4336354.7988
      636252.645    4336430.6883     636233.2888     4336401.963
     636101.0981    4336454.8115     635871.3658     4336721.628
#Sta/Elev= 30
       0  962.74   21.51  959.89   49.17   958.6   61.47  956.35   86.06  953.26
  107.57  952.78  126.01  956.75  187.48  957.65  331.93  950.89  396.47  951.48
  461.01  949.48  510.19  949.66  547.07  948.76  568.58  946.43  741.48  943.74
  830.94  943.74  840.74  943.74  958.87  944.48 1010.01  945.67 1028.38  947.59
 1046.75  946.96 1120.23  950.22 1236.57   953.3 1254.94   954.5 1270.25   954.2
 1288.62  955.89  1322.3  956.23 1328.42  957.76 1340.67  962.18 1349.85  963.49
#Mann= 3 , 0 , 0
       0     .09       0  830.94     .04       0  840.74     .09       0
Bank Sta=830.94,840.74
XS Rating Curve= 0 ,0
Exp/Cntr=0.3,0.1

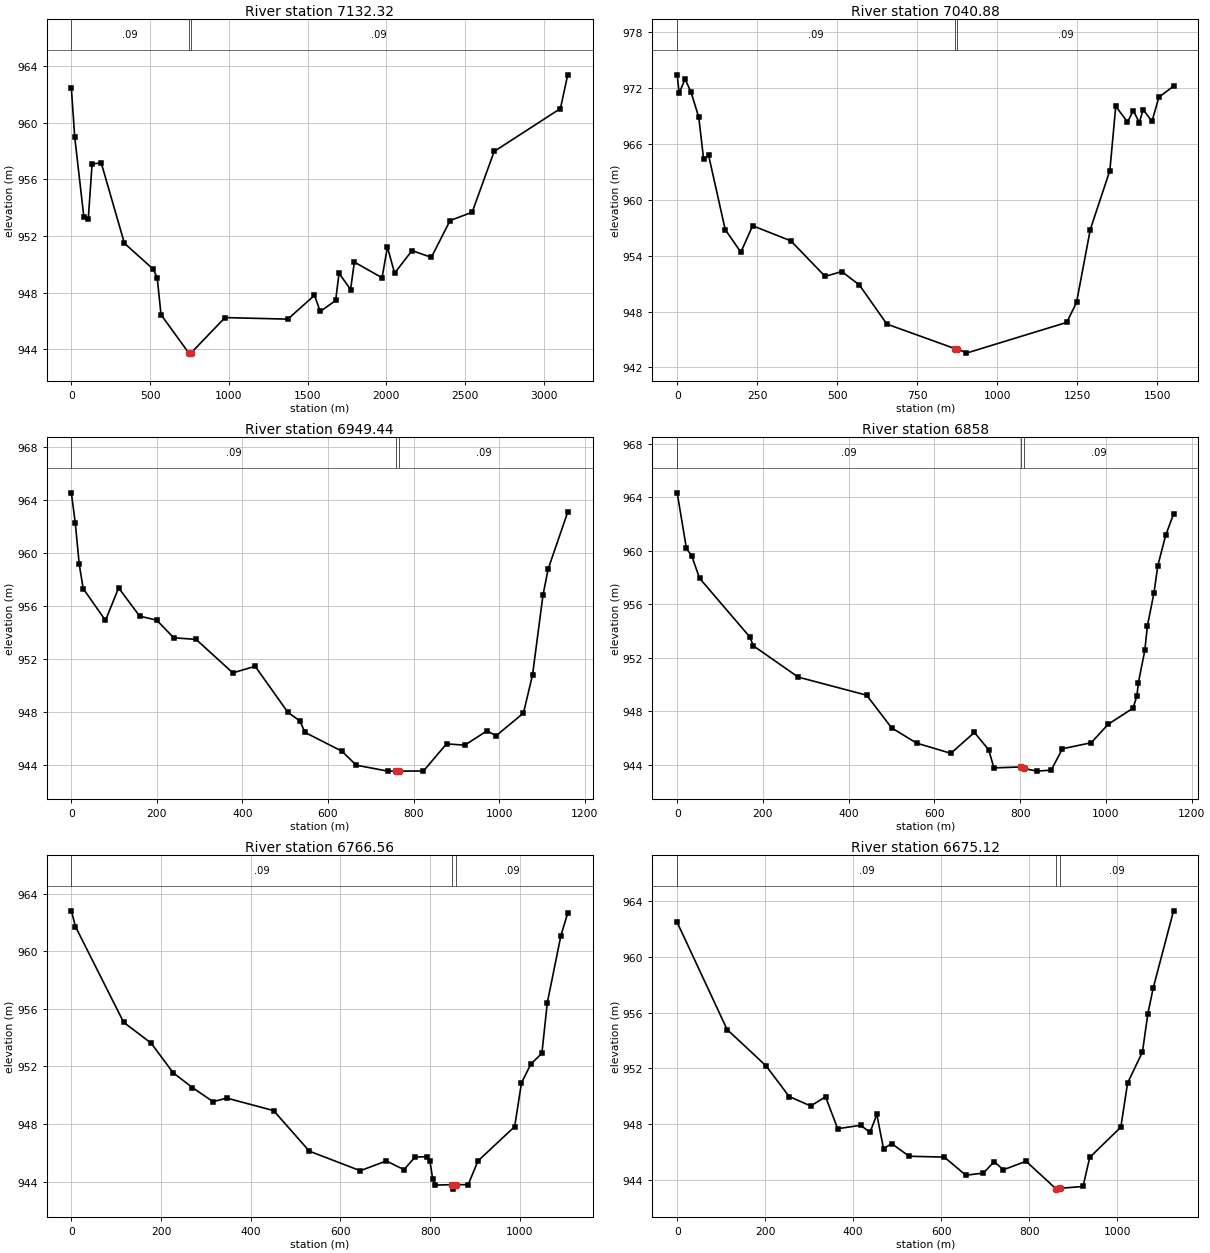
Type RM Length L Ch R = 1 ,7132.32 ,131.89,91.44,327.95
XS GIS Cut Line= 6
     636919.1179    4335957.5098     636380.0452    4336340.3358
     635826.5487    4336505.5187      635231.602     4337101.835
     635037.1329    4337597.9298     634731.5385    4337951.1492
#Sta/Elev= 30
       0  962.45   21.43  958.99   79.59  953.32  107.14  953.18  131.62   957.1
  189.78  957.17  336.71   951.5  520.37  949.66  544.86  949.07  569.35  946.45
  746.08  943.74  759.04  943.74  975.53  946.25 1374.18  946.14 1543.63  947.82
 1580.25  946.68 1678.09  947.46 1699.49  949.38 1772.75  948.23 1796.75  950.17
 1972.72  949.06 2006.45  951.23 2052.44  949.39 2162.85  950.98 2285.61   950.5
  2404.3   953.1 2544.74  953.69 2684.26  957.98 3105.23  961.01 3151.32  963.39
#Mann= 3 , 0 , 0
       0     .09       0  746.08     .04       0  759.04     .09       0
Bank Sta=746.08,759.04
XS Rating Curve= 0 ,0
Exp/Cntr=0.3,0.1

Type RM Length L Ch R = 1 ,7040.88 ,65.75,91.44,21.91
XS GIS Cut Line= 6
     636998.8899    4335882.7649     636298.2076    4336220.6526
     636250.2049    4336258.7046     636212.7669    4336303.9219
     636068.7914    4336267.6603      635573.312    4336366.9533
#Sta/Elev= 30
       0  973.42    6.13  971.44    24.5  972.97   42.88  971.59   67.38  968.88
   82.69  964.33      98  964.81  150.07   956.8  199.07  954.37  235.82  957.21
  355.26  955.59  462.45  951.77  514.52  952.29  569.64  950.85  655.39  946.65
  868.51  944.01  875.41  944.02  903.92  943.53 1217.84  946.83 1248.46  948.98
 1291.34   956.8 1352.59  963.14 1370.97  970.04 1407.72  968.36 1426.09  969.58
 1444.47  968.28 1456.72  969.69 1484.28  968.41 1505.72  971.02 1551.66   972.2
#Mann= 3 , 0 , 0
       0     .09       0  868.51     .04       0  875.41     .09       0
Bank Sta=868.51,875.41
XS Rating Curve= 0 ,0
Exp/Cntr=0.3,0.1

Type RM Length L Ch R = 1 ,6949.44 ,115.21,91.44,37.31
XS GIS Cut Line= 6
     636883.0022    4335922.4524      636185.904    4336204.5932
      636178.794    4336209.4354      636096.461    4336252.1429
     636076.4352    4336246.9377      635793.975    4336293.9282
#Sta/Elev= 30
       0  964.55    9.21  962.26   18.42  959.15   27.63  957.32   79.81  954.91
   110.5  957.37  159.61  955.24  199.52  954.93  239.42   953.6   291.6  953.48
  377.55  950.95  429.73  951.45  506.47  947.96   534.1  947.33  546.37  946.45
  632.32  945.04  666.08  943.98  739.75  943.53  758.18  943.53  766.01  943.53
  823.25  943.54   877.2  945.59  919.85  945.49  971.64  946.57  992.96   946.2
 1056.93  947.91 1078.25  950.79 1102.62  956.81 1114.81   958.8  1160.5  963.09
#Mann= 3 , 0 , 0
       0     .09       0  758.18     .04       0  766.01     .09       0
Bank Sta=758.18,766.01
XS Rating Curve= 0 ,0
Exp/Cntr=0.3,0.1

Type RM Length L Ch R = 1 ,6858    ,20.64,91.44,128.04
XS GIS Cut Line= 6
     636851.2521    4335895.4649     636202.4846    4336070.5154
     636127.0782    4336131.6342     636128.6657    4336172.1156
     636077.8656    4336230.8532     635814.6125    4336262.1781
#Sta/Elev= 30
       0  964.32   21.48  960.17   33.75  959.62   52.16  957.94  168.76  953.58
  177.96  952.89  282.29  950.56  441.84  949.21  500.14  946.77  558.44  945.63
  638.22  944.87   693.2  946.43  726.57  945.13   738.7  943.78  800.75  943.85
  809.05  943.74  838.58  943.54  872.07  943.61  898.61  945.21  965.65  945.66
 1005.26  947.04 1063.16  948.24  1072.3  949.17 1075.35   950.1 1090.59  952.55
 1096.68  954.39 1111.92  956.84 1121.06  958.89 1139.34  961.16 1157.63  962.73
#Mann= 3 , 0 , 0
       0     .09       0  800.75     .04       0  809.05     .09       0
Bank Sta=800.75,809.05
XS Rating Curve= 0 ,0
Exp/Cntr=0.3,0.1

Type RM Length L Ch R = 1 ,6766.56 ,48.76,91.44,39.43
XS GIS Cut Line= 6
     636860.7771    4335868.4773     636184.7452    4336058.9863
     636146.3616    4336088.3753     636022.5014    4336139.5646
     636001.5209    4336133.4006       635809.85    4336190.7405
#Sta/Elev= 30
       0  962.82     9.2  961.72  116.55  955.07  177.89  953.62  226.96  951.56
   269.9  950.53  315.91  949.55  346.58   949.8  450.86  948.93  530.61  946.11
  644.09  944.75  702.36  945.43  741.64  944.82  765.93  945.69  793.35  945.73
  799.44  945.43  805.53   944.2  811.62  943.75  848.18  943.78  851.22  943.47
  857.02  943.78  884.73  943.78  906.59  945.43  988.44  947.82 1003.59  950.86
 1024.81  952.18 1049.06  952.91 1061.19  956.43  1091.5   961.1 1106.66  962.66
#Mann= 3 , 0 , 0
       0     .09       0  848.18     .04       0  857.02     .09       0
Bank Sta=848.18,857.02
XS Rating Curve= 0 ,0
Exp/Cntr=0.3,0.1

Type RM Length L Ch R = 1 ,6675.12 ,28.62,91.44,109.97
XS GIS Cut Line= 6
     636852.3435    4335850.5518     636160.8445    4336017.5404
     636030.8677    4336063.1811     636031.8761    4336088.2293
     636013.0083    4336111.4677     635801.4164    4336175.9899
#Sta/Elev= 30
       0  962.47  113.45  954.78  202.37  952.16   254.5  949.97  303.56  949.29
  337.29  949.95  364.89  947.66  417.01   947.9  438.48   947.4  453.81  948.68
  469.14  946.22  487.54  946.59   527.4  945.68  607.12  945.62  656.18  944.32
  696.05  944.47  720.46  945.29  741.65  944.71  793.12  945.32  860.93  943.35
   863.5  943.32  870.89  943.38  922.55  943.51  937.92   945.6 1008.58  947.77
 1023.94  950.94 1057.74  953.17 1070.03  955.92 1082.32  957.78  1128.4   963.3
#Mann= 3 , 0 , 0
       0     .09       0  860.93     .04       0  870.89     .09       0
Bank Sta=860.93,870.89
XS Rating Curve= 0 ,0
Exp/Cntr=0.3,0.1