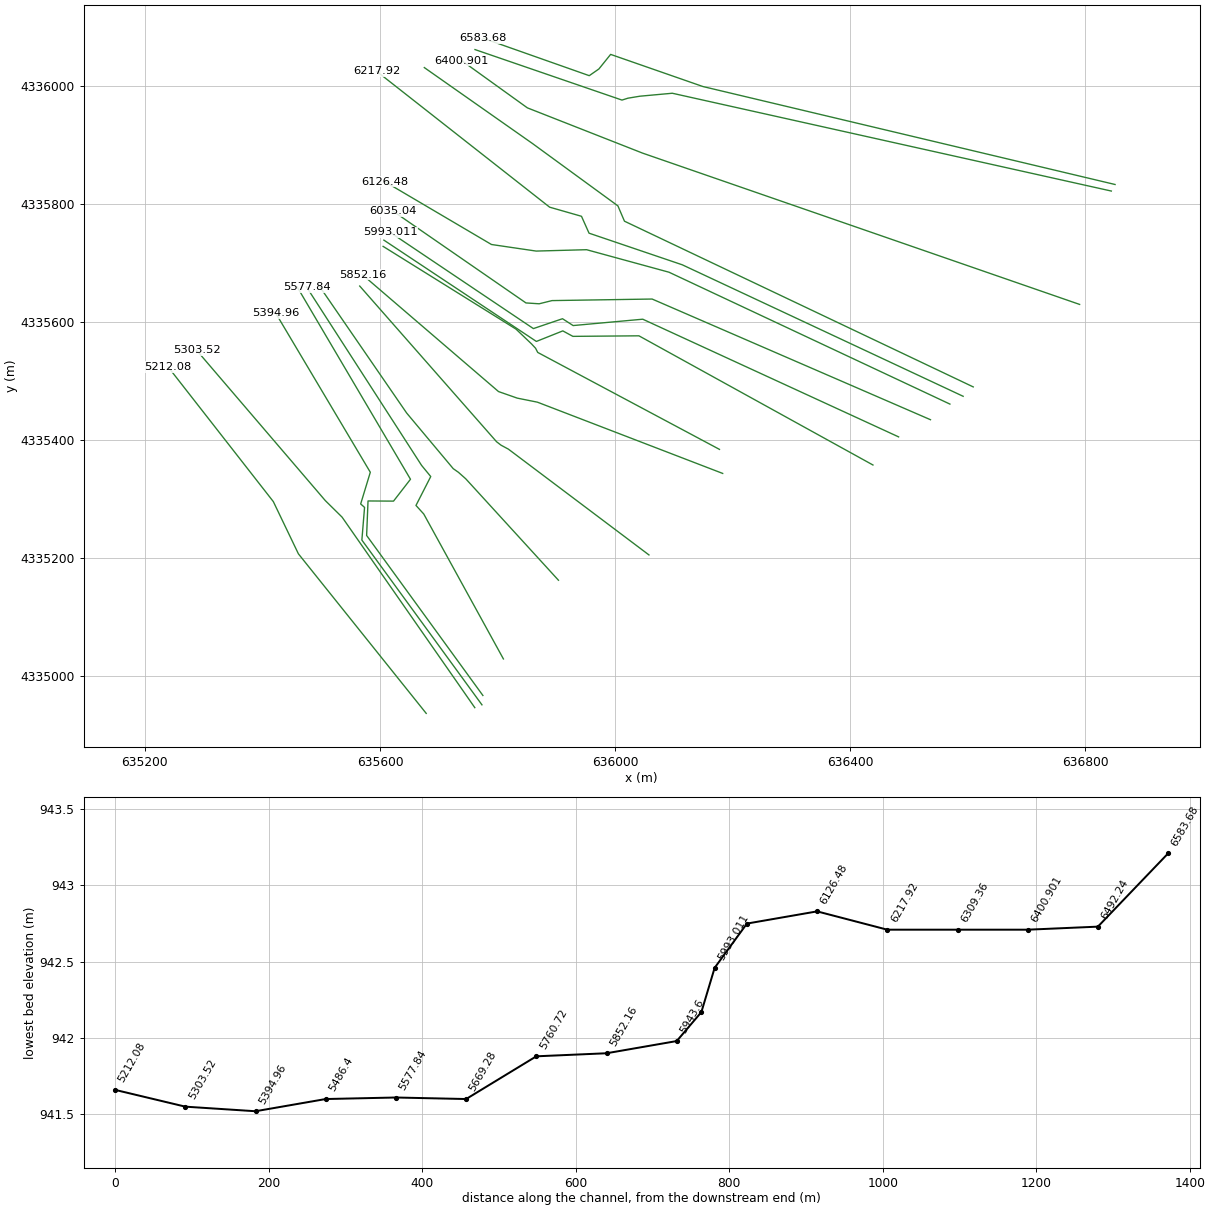
HEC-RAS study BeaverCreek.prj: BeaverCreek

--- BeaverCreek.g01 (geometry) --- (continued)

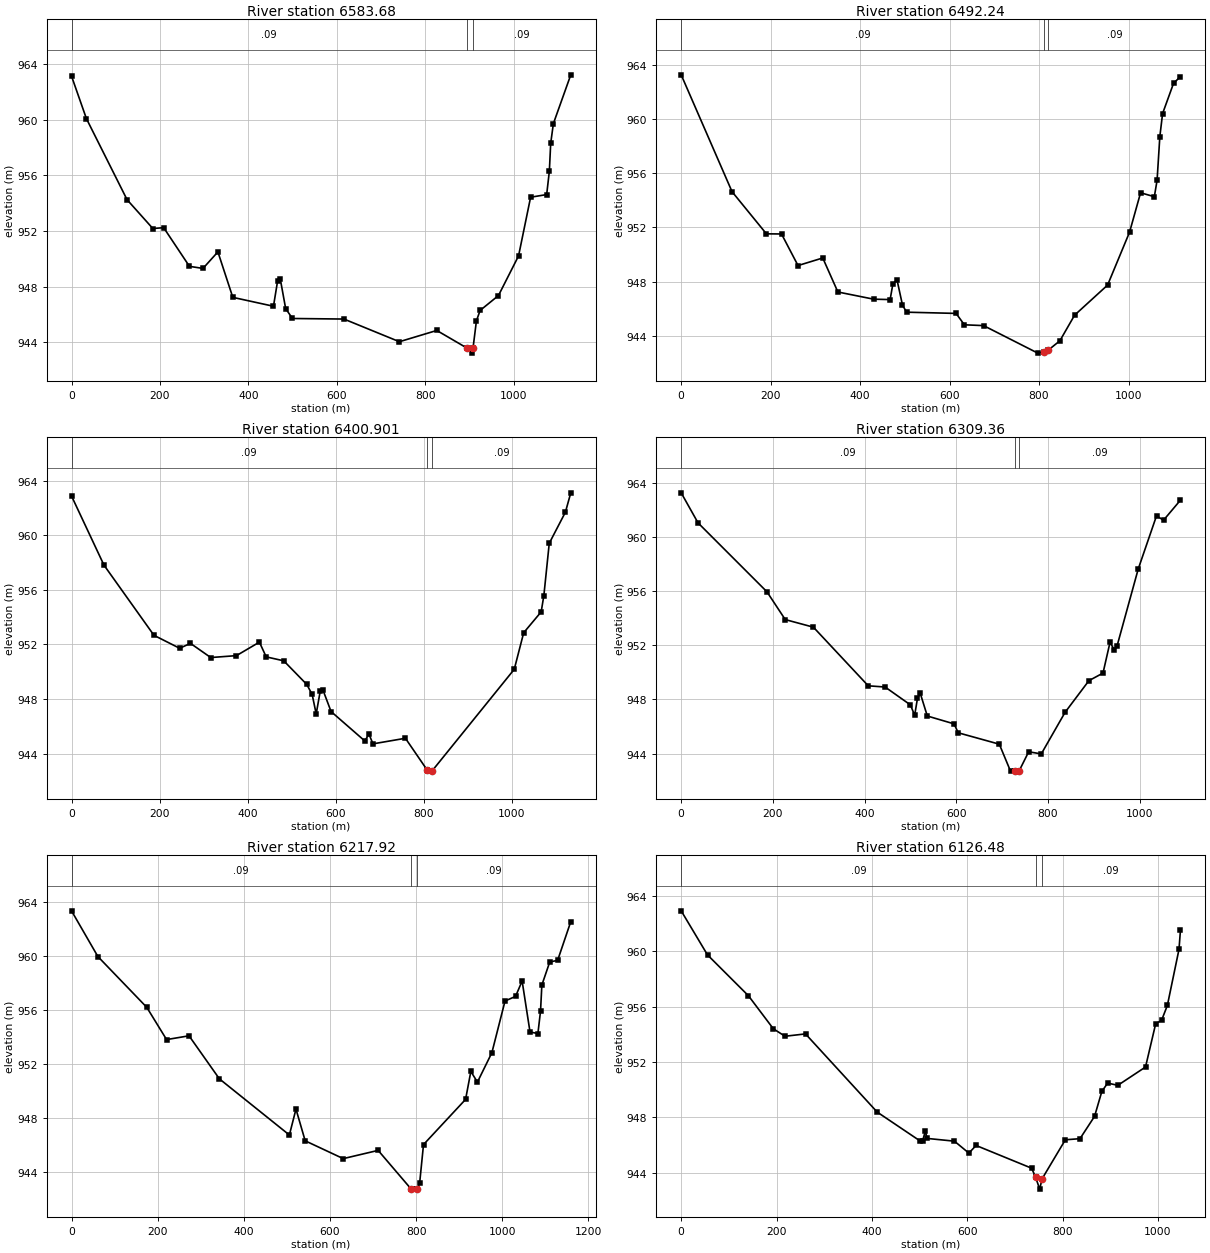
Type RM Length L Ch R = 1 ,6583.68 ,25.35,91.44,71.8
XS GIS Cut Line= 6
      636850.756    4335833.0892      636149.452    4335999.0879
     635992.4876     4336053.526      635972.538     4336028.865
     635956.1073    4336017.4764     635776.0164    4336080.7397
#Sta/Elev= 30
       0  963.13   33.73  960.07  125.74  954.24     184  952.17  208.54  952.23
  266.81  949.45  297.47   949.3  331.21  950.49  364.94  947.22  456.94  946.58
  466.14  948.37  472.28  948.55  484.54  946.41  499.88   945.7  616.41  945.66
  741.83  944.03  826.41  944.84  894.93  943.57  905.74  943.21  908.33  943.55
  916.12  945.53  924.43  946.28  965.97  947.35 1011.42   950.2 1038.69  954.42
 1075.05  954.61 1081.11  956.29 1084.14  958.29  1090.2  959.71 1129.59  963.22
#Mann= 3 , 0 , 0
       0     .09       0  894.93     .04       0  908.33     .09       0
Bank Sta=894.93,908.33
XS Rating Curve= 0 ,0
Exp/Cntr=0.3,0.1

Type RM Length L Ch R = 1 ,6492.24 ,115.06,91.34,77.2
XS GIS Cut Line= 6
      636844.406    4335821.9767     636097.4328    4335987.7006
     636042.2302    4335982.6822     636021.8277    4335979.3025
     636011.7735    4335976.1275     635761.7288    4336061.6897
#Sta/Elev= 30
       0  963.26  113.69  954.64  190.52  951.53  224.32  951.52  261.19  949.19
   316.5  949.75   350.3  947.24   430.2  946.71  467.07  946.68  473.22  947.83
  482.44  948.14  494.73  946.27  503.95  945.75  614.57  945.66     633  944.82
  676.02  944.76  797.23  942.73  811.81  942.82  820.57  942.95  846.52  943.64
  879.45  945.53   953.2  947.75 1002.37  951.66 1026.95  954.56 1057.68  954.27
 1063.83  955.48 1069.97   958.7 1076.12   960.4  1100.7  962.64 1116.07  963.13
#Mann= 3 , 0 , 0
       0     .09       0  811.81     .04       0  820.57     .09       0
Bank Sta=811.81,820.57
XS Rating Curve= 0 ,0
Exp/Cntr=0.3,0.1

Type RM Length L Ch R = 1 ,6400.901,118.77,91.54,97.82
XS GIS Cut Line= 4
     636790.4309    4335629.8888     636046.9039    4335886.2266
     635850.8354    4335962.9395     635738.9746    4336043.0806
#Sta/Elev= 30
       0  962.89   73.73  957.82   187.4  952.67  245.77  951.72  270.35  952.08
  316.43  951.04   374.8  951.18  427.03  952.17  442.39  951.09  482.33   950.8
  534.56  949.07  546.84  948.34  556.06   946.9  565.28  948.59  571.42  948.66
  589.85  947.08  666.66  944.92  675.87  945.43  685.09  944.71  758.82  945.12
  807.83  942.81  810.77  942.71  820.04  942.75 1006.19  950.18 1027.59  952.86
 1067.34  954.39 1073.46  955.59 1085.69  959.42 1122.39   961.7 1134.62  963.12
#Mann= 3 , 0 , 0
       0     .09       0  807.83     .04       0  820.04     .09       0
Bank Sta=807.83,820.04
XS Rating Curve= 0 ,0
Exp/Cntr=0.3,0.1

Type RM Length L Ch R = 1 ,6309.36 ,63.54,91.44,79.43
XS GIS Cut Line= 5
     636609.4555    4335490.1004     636016.0271    4335770.9035
     636004.8637    4335796.8538     635859.2497    4335902.6991
     635675.4745    4336031.1744
#Sta/Elev= 30
       0  963.26   36.81  961.04  187.14  955.95  227.02   953.9  288.37  953.34
  408.02  949.01  444.83  948.92  500.05   947.6  509.26  946.83  515.39  948.08
  521.53  948.45  536.87  946.78  595.16   946.2  604.36  945.54  693.91   944.7
  718.32  942.71  728.22  942.71  736.91  942.71  757.99  944.14  785.45  943.98
  837.32  947.05  889.35  949.39  920.07  949.95  935.43  952.23  944.64  951.66
  950.79  951.96  996.86  957.63 1036.79  961.56 1052.15  961.24 1089.01  962.72
#Mann= 3 , 0 , 0
       0     .09       0  728.22     .04       0  736.91     .09       0
Bank Sta=728.22,736.91
XS Rating Curve= 0 ,0
Exp/Cntr=0.3,0.1

Type RM Length L Ch R = 1 ,6217.92 ,47.37,91.44,115.06
XS GIS Cut Line= 6
     636592.2576    4335474.2253     636114.4287    4335696.9905
     635955.7501    4335750.6031     635942.9024    4335779.2066
     635888.7156    4335794.6582     635594.7764    4336024.5598
#Sta/Elev= 30
       0  963.33    61.3  959.94  174.71  956.18  220.69  953.79   272.8  954.07
   343.3  950.88  505.75  946.72  521.07  948.64  542.43  946.29  630.74  944.97
   711.8  945.58  788.04  942.73  790.85  942.71  802.86  942.71  808.28   943.2
   817.1  946.01  914.78  949.36  926.99  951.43  942.25  950.64  975.83  952.82
 1006.35  956.65 1030.77  956.99 1046.03  958.13 1064.35  954.35 1082.66  954.24
 1088.77  955.91 1091.82  957.83 1110.14  959.54 1128.45  959.66 1158.97  962.53
#Mann= 3 , 0 , 0
       0     .09       0  788.04     .04       0  802.86     .09       0
Bank Sta=788.04,802.86
XS Rating Curve= 0 ,0
Exp/Cntr=0.3,0.1

Type RM Length L Ch R = 1 ,6126.48 ,86.59,91.44,92.42
XS GIS Cut Line= 6
     636569.7679    4335460.9961     636091.8006     4335684.446
     635951.5366    4335722.6032     635865.7063    4335720.2777
     635789.7131    4335731.4158     635608.0056    4335838.0281
#Sta/Elev= 30
       0  962.91   55.22  959.73  141.11  956.78  193.26   954.4   217.8  953.86
  260.74  954.03  411.05  948.39  500.01  946.33  506.15   946.3  512.28  947.04
  515.35  946.49  573.05  946.29  603.33  945.43  618.47  945.98  734.92  944.34
  743.54  943.67   751.8  942.83  756.99  943.58  805.67  946.39  836.39  946.47
  866.92  948.08  882.19  949.88   894.4  950.48  915.77  950.32  973.78  951.64
  995.16  954.77 1007.37     955 1019.58  956.08 1044.01  960.13 1047.06  961.52
#Mann= 3 , 0 , 0
       0     .09       0  743.54     .04       0  756.99     .09       0
Bank Sta=743.54,756.99
XS Rating Curve= 0 ,0
Exp/Cntr=0.3,0.1

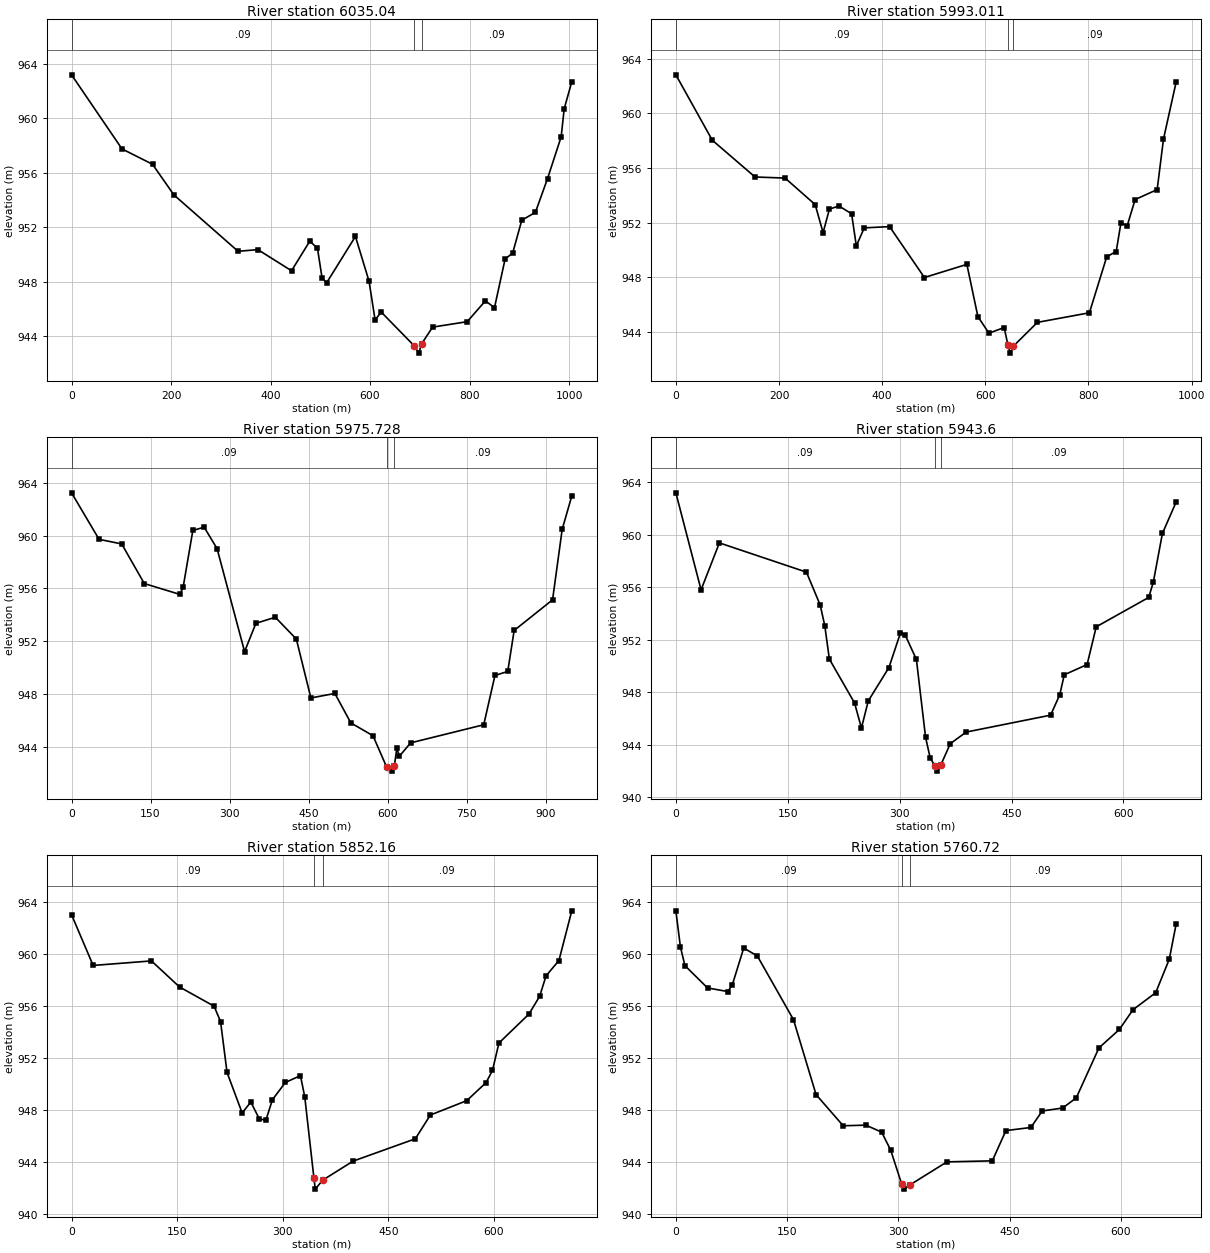
Type RM Length L Ch R = 1 ,6035.04 ,42.75,42.03,42.67
XS GIS Cut Line= 6
      636536.695    4335434.5378     636063.0989    4335639.0048
     635892.7549     4335636.371     635870.8959    4335630.9543
     635848.4371    4335632.4022     635622.5577    4335787.7572
#Sta/Elev= 30
       0  963.19  101.33  957.75  162.74  956.62  205.73  954.37  334.69  950.23
  374.61  950.35  442.16   948.8     479  950.98  494.36  950.44  503.57  948.26
  512.78  947.92  570.61  951.32  597.99  948.03  610.16  945.18  622.33  945.77
  689.19  943.27  698.11  942.75  703.47  943.42   725.7  944.66   795.3  945.06
  831.85  946.59  850.13  946.09  871.45  949.66  886.68   950.1  904.96  952.51
  932.37  953.09  956.74  955.57  984.15  958.64  990.25   960.7 1005.48  962.68
#Mann= 3 , 0 , 0
       0     .09       0  689.19     .04       0  703.47     .09       0
Bank Sta=689.19,703.47
XS Rating Curve= 0 ,0
Exp/Cntr=0.3,0.1

Type RM Length L Ch R = 1 ,5993.011,18.5,17.28,18.1
XS GIS Cut Line= 6
     636482.4553    4335405.4335     636047.1266    4335604.8411
     635928.6859    4335594.0669     635910.5884    4335605.6557
     635861.0583     4335588.934      635617.266    4335752.0384
#Sta/Elev= 30
       0  962.81    70.6  958.03  153.47  955.34  211.79  955.26  270.11  953.32
  285.45  951.27  297.73  952.99  316.15  953.22   340.7  952.65  349.91   950.3
  365.26  951.62  414.37  951.71  481.88  947.99  564.21  948.95  585.56  945.13
  606.97  943.92  636.49  944.33  643.76  943.06   648.3  942.46   654.1  942.96
  700.95  944.71  801.78  945.41  835.39  949.51  853.72  949.89  862.89  951.98
  875.11  951.78  890.39  953.69  933.16  954.42  945.38  958.11  969.83  962.26
#Mann= 3 , 0 , 0
       0     .09       0  643.76     .04       0   654.1     .09       0
Bank Sta=643.76,654.1
XS Rating Curve= 0 ,0
Exp/Cntr=0.3,0.1

Type RM Length L Ch R = 1 ,5975.728,66.06,32.13,8.62
XS GIS Cut Line= 6
     636438.7989    4335357.8084     636040.6279    4335576.6795
     635928.3067      4335575.76     635911.1087    4335585.0204
     635866.1295     4335567.161     635606.6827    4335738.8092
#Sta/Elev= 30
       0  963.24   52.19  959.72   95.17  959.37  138.15  956.37  205.69  955.55
  211.83  956.09  230.25  960.39  251.74  960.64   276.3  959.01  328.49  951.22
  349.98  953.36  386.82  953.82  426.73  952.17  454.36  947.71   499.9  948.05
  530.26  945.82  572.27  944.85  597.97   942.5   608.2  942.17  612.88  942.57
  617.55  943.91  622.39   943.3  643.75  944.31  782.52  945.68   803.8  949.41
  828.11  949.72  840.26  952.82   913.2  955.14  931.43  960.47  949.67     963
#Mann= 3 , 0 , 0
       0     .09       0  597.97     .04       0  612.88     .09       0
Bank Sta=597.97,612.88
XS Rating Curve= 0 ,0
Exp/Cntr=0.3,0.1

Type RM Length L Ch R = 1 ,5943.6  ,77.73,91.44,96.98
XS GIS Cut Line= 6
     636177.6547    4335384.2668     635868.4389    4335548.5402
     635864.7679     4335555.615     635858.0283    4335562.8387
     635831.5255    4335588.0101     635605.3598    4335728.2258
#Sta/Elev= 30
       0  963.21   33.79  955.81   58.36  959.39  175.07  957.16   193.5  954.65
  199.64  953.08  205.79  950.53  239.57  947.18  248.79  945.27     258  947.34
  285.64  949.88     301   952.5  307.14   952.4   322.5   950.5  334.79  944.56
  340.93     943  347.07   942.4  350.14  941.98  355.46  942.48  367.99  944.08
  389.31  944.96  502.42  946.25  514.66   947.8  520.77  949.33  551.36  950.11
  563.59  952.99  633.94  955.23  640.06  956.38   652.3  960.11  670.65   962.5
#Mann= 3 , 0 , 0
       0     .09       0  347.07     .04       0  355.46     .09       0
Bank Sta=347.07,355.46
XS Rating Curve= 0 ,0
Exp/Cntr=0.3,0.1

Type RM Length L Ch R = 1 ,5852.16 ,96.57,91.44,70.28
XS GIS Cut Line= 5
     636183.1117    4335343.5209     635867.9228    4335464.2439
     635833.6287    4335471.1028     635801.7711    4335482.2068
     635570.3355    4335680.0716
#Sta/Elev= 30
       0  963.05   30.68  959.14  113.53  959.49  153.42  957.48  202.51     956
  211.72  954.81  220.92  950.89   242.4  947.77  254.67  948.61  266.95   947.3
  276.15  947.22  285.36  948.79  303.77  950.12  325.24  950.65  331.38  948.99
  344.38  942.74  346.26   941.9  356.79  942.59  400.09  944.06  488.44  945.78
  509.75  947.61  561.52  948.72  588.92  950.11  598.05  951.05  607.19  953.16
  649.82  955.39  665.04  956.76  674.18  958.34  692.45  959.52  710.71  963.35
#Mann= 3 , 0 , 0
       0     .09       0  344.38     .04       0  356.79     .09       0
Bank Sta=344.38,356.79
XS Rating Curve= 0 ,0
Exp/Cntr=0.3,0.1

Type RM Length L Ch R = 1 ,5760.72 ,91.16,91.44,85.36
XS GIS Cut Line= 5
      636057.699    4335205.4081     635818.5539    4335384.6482
     635805.9664    4335391.3916     635798.3933    4335397.2224
      635565.573    4335661.0215
#Sta/Elev= 30
       0  963.32     6.1  960.56    12.2   959.1   42.69  957.38   70.14   957.1
   76.24  957.64   91.49  960.45  109.79  959.85  158.58  954.94  189.07  949.16
  225.67  946.76  256.17  946.81  277.51  946.27  289.71  944.88  304.57  942.26
  307.43  941.88  315.53   942.2  365.53  943.98  426.72  944.06  445.08  946.39
  478.73  946.63  494.03   947.9  521.57  948.13  539.92  948.91  570.52  952.76
  598.06  954.18  616.41   955.7  647.01  957.01  665.36  959.59  674.54  962.28
#Mann= 3 , 0 , 0
       0     .09       0  304.57     .04       0  315.53     .09       0
Bank Sta=304.57,315.53
XS Rating Curve= 0 ,0
Exp/Cntr=0.3,0.1

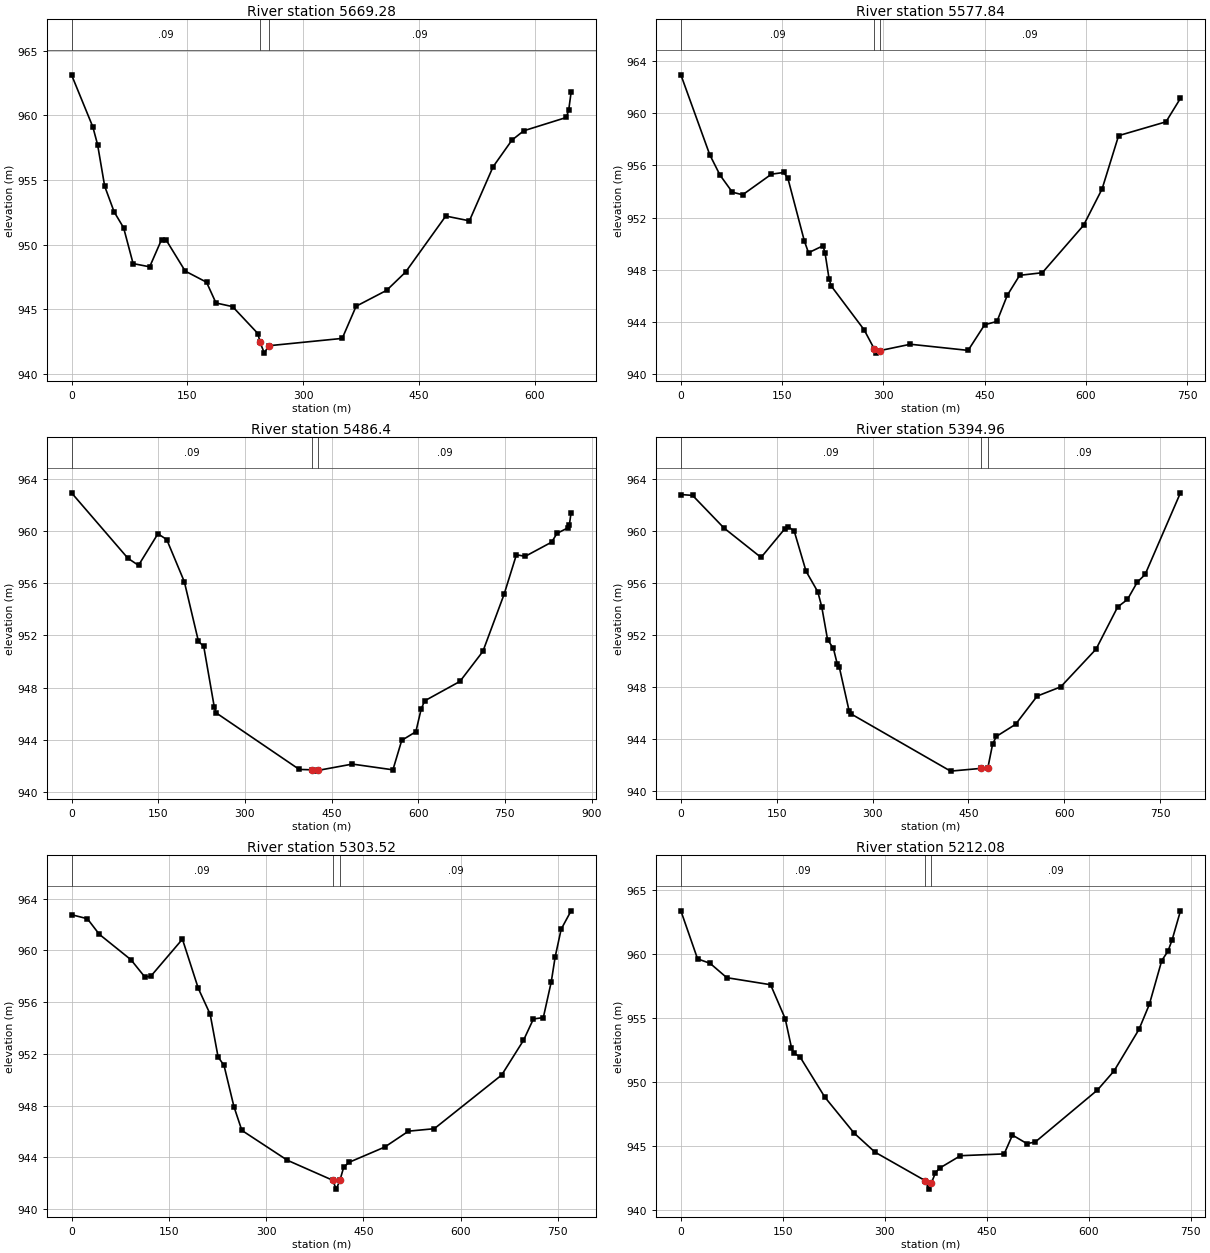
Type RM Length L Ch R = 1 ,5669.28 ,94.27,91.44,37.78
XS GIS Cut Line= 6
     635903.7111    4335162.5455     635746.0131    4335334.3715
     635733.5635    4335345.3829     635724.6978    4335351.5764
     635645.4666    4335445.8098     635495.7228     4335662.609
#Sta/Elev= 30
       0  963.14   27.62  959.11   33.76  957.74   42.96  954.52   55.24  952.53
   67.51   951.3   79.79  948.53  101.27  948.28  116.61  950.38  122.75  950.34
   147.3  947.95  174.92  947.09  187.19  945.48  208.67   945.2  241.53  943.11
   244.3  942.43  249.84   941.6  255.25  942.17  350.74  942.74  368.76  945.23
  408.28  946.46  432.79  947.87  484.88  952.21  515.52  951.84  546.16  956.02
  570.67  958.09  585.98  958.81  641.13  959.84   644.2  960.42  647.26  961.78
#Mann= 3 , 0 , 0
       0     .09       0   244.3     .04       0  255.25     .09       0
Bank Sta=244.3,255.25
XS Rating Curve= 0 ,0
Exp/Cntr=0.3,0.1

Type RM Length L Ch R = 1 ,5577.84 ,127.15,91.44,46.01
XS GIS Cut Line= 6
     635810.0485    4335029.1953     635674.5273    4335274.7558
     635661.2946    4335289.2754     635686.4103    4335338.2348
      635670.866    4335357.0864     635475.0853     4335659.434
#Sta/Elev= 30
       0  962.93   42.68  956.82   57.92  955.25   76.22  953.94   91.46  953.74
  134.14  955.32  152.43  955.45  158.53  954.99  182.92  950.19  189.02   949.3
  210.36  949.83   213.4  949.31   219.5  947.29  222.55  946.76  271.33   943.4
  286.09  941.96  288.89  941.61  294.51   941.8  339.86  942.29  425.37  941.82
  449.79  943.78   468.1  944.04  483.37  946.04  501.68  947.57  535.26  947.77
  596.31   951.4  623.78  954.19   648.2  958.27  718.41  959.33  739.78  961.13
#Mann= 3 , 0 , 0
       0     .09       0  286.09     .04       0  294.51     .09       0
Bank Sta=286.09,294.51
XS Rating Curve= 0 ,0
Exp/Cntr=0.3,0.1

Type RM Length L Ch R = 1 ,5486.4  ,31.83,91.44,102.23
XS GIS Cut Line= 6
     635775.1234    4334967.2827     635577.3246    4335238.3874
     635579.7059    4335296.8605     635623.0976    4335296.5959
     635651.9373    4335333.6376     635459.2103     4335659.434
#Sta/Elev= 30
       0  962.94   97.63  957.92  115.93  957.38  149.49   959.8  164.75  959.36
  195.25  956.12  219.66  951.55  228.81  951.16  247.12   946.5  250.17  946.07
  394.11  941.73  416.85   941.7  422.92   941.6  425.89  941.65  485.99  942.14
   556.2   941.7  571.46  943.96  595.88  944.62  605.04  946.35  611.15  946.99
   672.2  948.48  711.89  950.78  748.52  955.15  769.89  958.19  785.15  958.07
  830.94  959.16   840.1  959.83  858.42  960.24  861.47  960.47  864.52  961.42
#Mann= 3 , 0 , 0
       0     .09       0  416.85     .04       0  425.89     .09       0
Bank Sta=416.85,425.89
XS Rating Curve= 0 ,0
Exp/Cntr=0.3,0.1

Type RM Length L Ch R = 1 ,5394.96 ,41.29,91.44,95.06
XS GIS Cut Line= 6
     635773.5359    4334951.4076     635569.2394    4335230.5999
     635573.8079    4335285.9684     635567.1933    4335291.7893
     635583.5975    4335345.4998     635422.6977    4335614.9839
#Sta/Elev= 30
       0  962.79   18.37  962.72   67.35  960.22  125.52  957.95  162.26  960.13
  168.39  960.32  177.57  959.95  195.94  956.89  214.31  955.31  220.43  954.17
  229.62  951.63   238.8  950.95  244.92  949.73  247.99  949.52  263.29  946.16
  266.36  945.92  422.15  941.52   469.5  941.73   480.5  941.77  487.96   943.6
  493.84  944.19  523.91  945.12   557.7  947.29  594.56     948  649.85   950.9
  683.64  954.14     699  954.72  714.36  956.05  726.65  956.64  781.94  962.92
#Mann= 3 , 0 , 0
       0     .09       0   469.5     .04       0   480.5     .09       0
Bank Sta=469.5,480.5
XS Rating Curve= 0 ,0
Exp/Cntr=0.3,0.1

Type RM Length L Ch R = 1 ,5303.52 ,96.09,91.44,78.49
XS GIS Cut Line= 4
      635761.365    4334946.6451     635535.5511    4335269.4648
       635506.98    4335297.5196     635287.7599    4335552.5422
#Sta/Elev= 30
       0  962.76   24.43  962.45   42.76  961.25   91.62  959.28     113  957.95
  122.16     958  171.02  960.87  195.45  957.07  213.78  955.07  225.99  951.77
  235.15  951.11  250.42  947.93  262.64  946.09  332.88  943.78  402.54  942.24
  408.26  941.55  413.98  942.25   419.7  943.25  428.28  943.63  482.92   944.8
   519.6  946.03  559.35  946.22   663.3  950.37  696.92  953.05  712.21   954.7
   727.5  954.81  739.73  957.57  745.84  959.52  755.01  961.64   770.3  963.06
#Mann= 3 , 0 , 0
       0     .09       0  402.54     .04       0  413.98     .09       0
Bank Sta=402.54,413.98
XS Rating Curve= 0 ,0
Exp/Cntr=0.3,0.1

Type RM Length L Ch R = 1 ,5212.08 ,75.93,91.44,112.2
XS GIS Cut Line= 4
     635678.6826    4334936.9437     635461.2377    4335207.2875
      635418.577    4335295.7891     635239.6497    4335523.8789
#Sta/Elev= 30
       0  963.39   24.56  959.64   42.98  959.29   67.55  958.17  132.02  957.62
  153.51  954.97  162.72  952.71  165.79  952.28  175.01  952.01  211.85  948.84
  254.83  946.04  285.54  944.55  359.22  942.33  365.36  941.66  368.43  942.11
  374.57  942.94  380.71   943.3  411.42  944.27   475.7  944.41  487.91  945.88
  509.27  945.21  521.48  945.34  613.02   949.4  637.43  950.89  674.05  954.13
  689.31  956.08  707.62  959.51  716.77  960.24  722.88  961.13  735.08  963.38
#Mann= 3 , 0 , 0
       0     .09       0  359.22     .04       0  368.43     .09       0
Bank Sta=359.22,368.43
XS Rating Curve= 0 ,0
Exp/Cntr=0.3,0.1