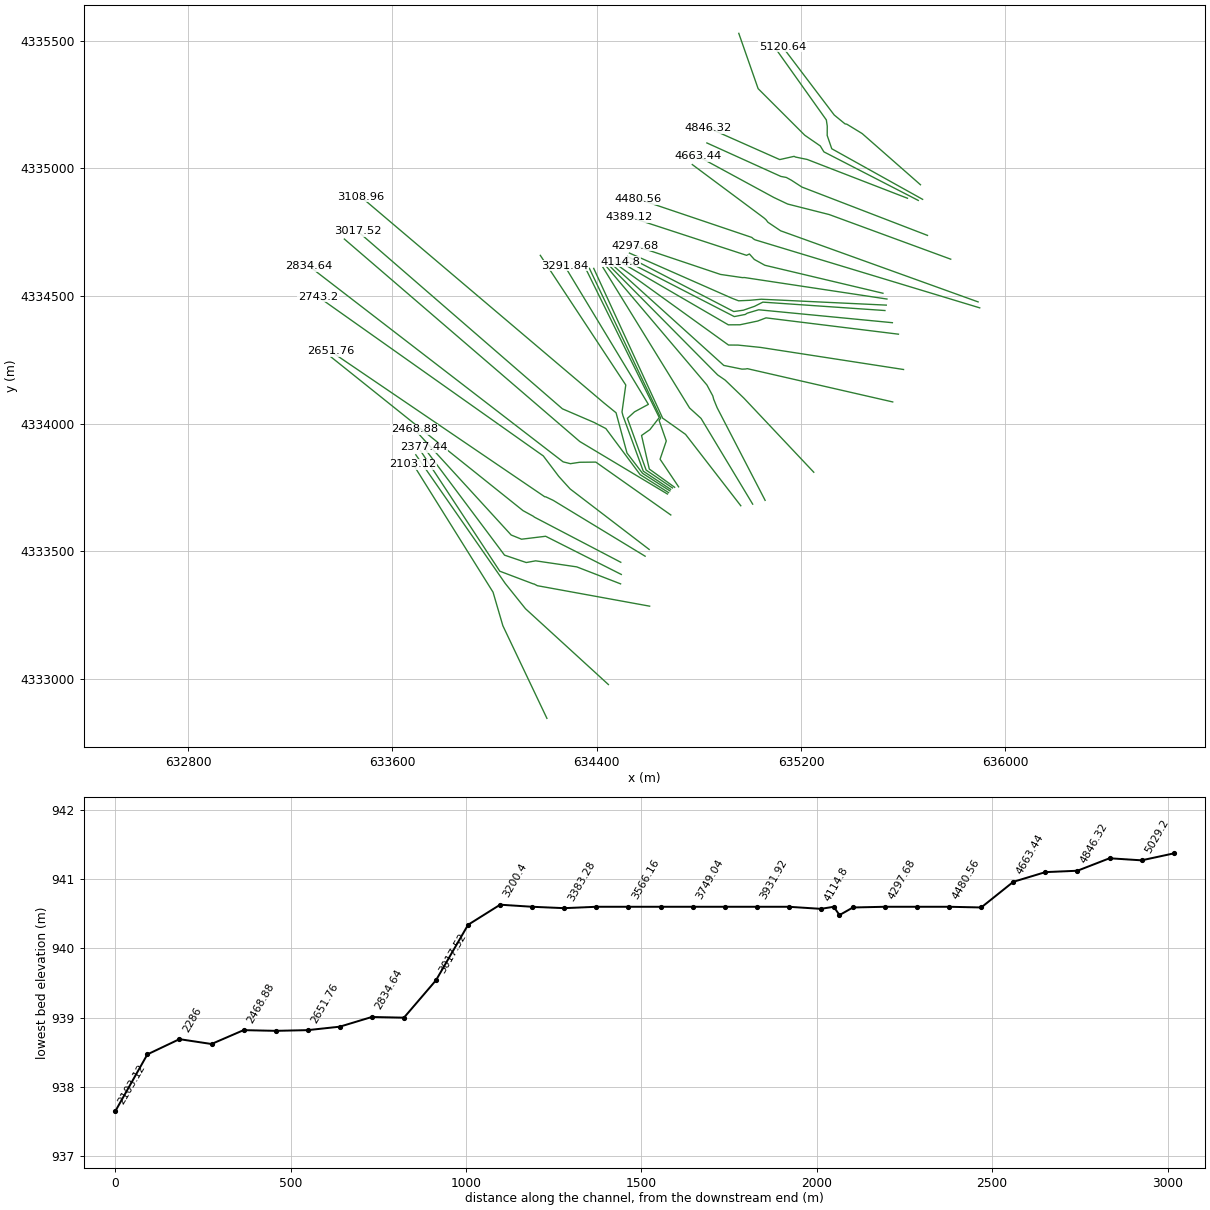
HEC-RAS study BeaverCreek.prj: BeaverCreek

--- BeaverCreek.g01 (geometry) --- (continued)

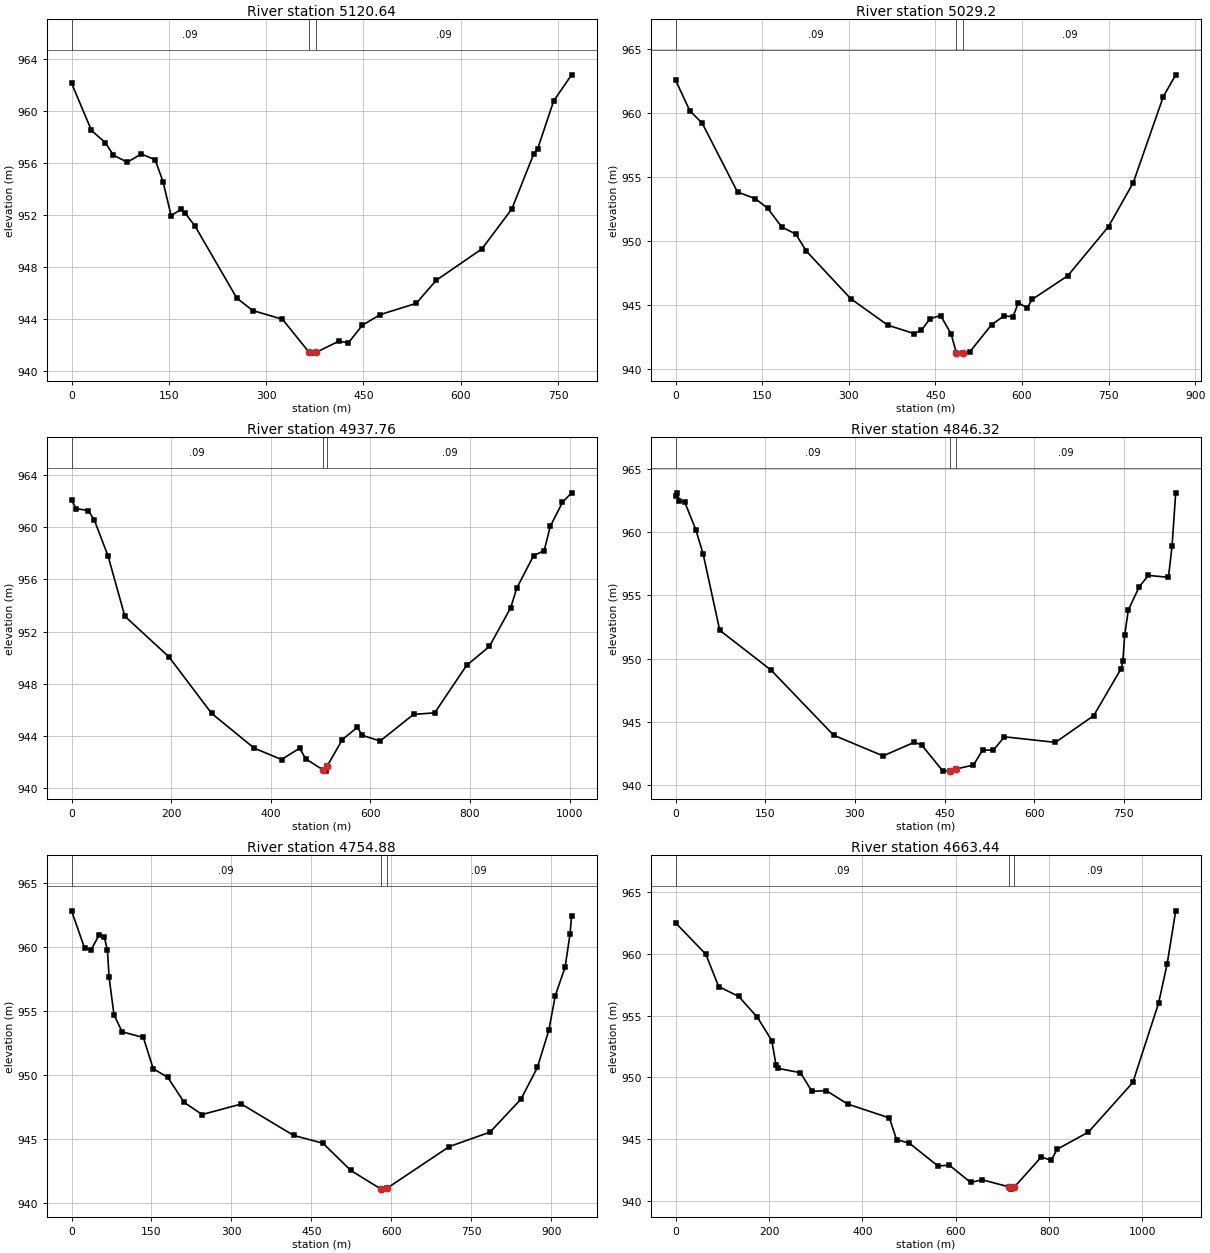
Type RM Length L Ch R = 1 ,5120.64 ,115.59,91.44,52.03
XS GIS Cut Line= 6
     635667.2173    4334935.4444      635438.953    4335135.8704
     635378.8803     4335172.544      635372.012    4335173.6702
     635329.6785    4335208.3969     635127.4662    4335475.1955
#Sta/Elev= 30
       0  962.16   30.68  958.52   52.16  957.57   64.44  956.62   85.91  956.07
  107.39   956.7  128.87  956.27  141.14  954.55  153.42  951.96  168.76  952.43
   174.9  952.16  190.24  951.16  254.67  945.61  279.22  944.65     325  943.98
  366.09  941.44  368.78  941.37   376.6  941.42  411.66  942.28  426.87  942.17
  448.28  943.52  475.92  944.34   531.2   945.2  561.92  946.97  632.56   949.4
  678.62  952.47  712.41  956.71  718.55  957.12  743.12  960.79  770.76   962.8
#Mann= 3 , 0 , 0
       0     .09       0  366.09     .04       0   376.6     .09       0
Bank Sta=366.09,376.6
XS Rating Curve= 0 ,0
Exp/Cntr=0.3,0.1

Type RM Length L Ch R = 1 ,5029.2  ,36.83,91.44,102.58
XS GIS Cut Line= 6
      635675.684    4334878.2943     635319.9551    4335076.3916
     635302.1369     4335128.249     635302.3376    4335164.7663
     635298.7884    4335189.1043     635099.9495    4335468.8455
#Sta/Elev= 30
       0  962.53   24.49  960.15   45.92  959.19  107.15  953.82  137.76  953.31
  159.19  952.57  183.68   951.1  208.18  950.54  226.54  949.21  303.08  945.52
  367.37  943.45  413.26  942.79  425.45  943.04  440.68  943.95  458.95   944.2
  477.22  942.77  486.35  941.27  498.52  941.27  509.45  941.36  547.63   943.5
  569.08  944.17   584.4  944.11  593.59  945.18  608.92  944.81  618.11  945.47
   679.4   947.3  749.88  951.13  792.78  954.55  844.87  961.26  866.32  962.95
#Mann= 3 , 0 , 0
       0     .09       0  486.35     .04       0  498.52     .09       0
Bank Sta=486.35,498.52
XS Rating Curve= 0 ,0
Exp/Cntr=0.3,0.1

Type RM Length L Ch R = 1 ,4937.76 ,65.57,91.44,187.09
XS GIS Cut Line= 6
     635658.7506    4334874.0609     635289.1752    4335064.2207
      635275.111    4335087.2987     635214.4448    4335129.1376
     635031.6931     4335311.686     634956.0158    4335528.1122
#Sta/Elev= 30
       0  962.09    9.17  961.43   33.62  961.28   45.84  960.54   73.35  957.79
  106.96  953.18  195.59  950.06  281.16  945.73  366.73  943.06  421.63  942.19
  458.01  943.06  470.29  942.23  504.07  941.42  510.21   941.3  513.28  941.69
   543.7  943.72  574.09  944.67   583.2  944.05  619.67  943.61  686.53  945.65
  729.07  945.77     793   949.4  838.85  950.86  881.65  953.83  893.88  955.33
  927.51  957.82  948.91  958.21  961.13  960.07  985.59  961.91 1003.93  962.64
#Mann= 3 , 0 , 0
       0     .09       0  504.07     .04       0  513.28     .09       0
Bank Sta=504.07,513.28
XS Rating Curve= 0 ,0
Exp/Cntr=0.3,0.1

Type RM Length L Ch R = 1 ,4846.32 ,107.85,91.44,70.89
XS GIS Cut Line= 6
     635616.4172    4334882.5276     635223.7837    4335034.4489
     635177.9473    4335043.9323     635172.6701    4335046.6479
     635116.3137    4335033.9479     634837.4823    4335157.6948
#Sta/Elev= 30
       0  962.81    3.07  963.06    6.15  962.48   15.36  962.34    33.8  960.17
   46.09  958.24   73.75  952.24   159.8  949.09  264.28  943.96  347.25  942.32
  399.49   943.4  411.78  943.18  447.37  941.12  458.63  941.15  469.08  941.29
  498.48   941.6  513.68  942.78  531.93  942.78  550.23  943.83  635.65  943.39
  699.71   945.5  745.47   949.2  748.52   949.8  751.57  951.85  757.67  953.84
  775.97  955.68  791.23  956.57  824.78  956.42  830.88   958.9  836.98  963.09
#Mann= 3 , 0 , 0
       0     .09       0  458.63     .04       0  469.08     .09       0
Bank Sta=458.63,469.08
XS Rating Curve= 0 ,0
Exp/Cntr=0.3,0.1

Type RM Length L Ch R = 1 ,4754.88 ,83.75,91.44,87.78
XS GIS Cut Line= 6
      635694.734    4334737.1388     635203.0311    4334926.4739
     635161.0681    4334953.6864      635142.018    4334964.0052
     635120.9042    4334967.9739     634831.1323    4335099.0895
#Sta/Elev= 30
       0  962.81   24.51   959.9   36.76  959.77   52.08  960.95   61.27   960.8
   67.39  959.72   70.46  957.62   79.65  954.69   94.96  953.37  134.79  952.93
  153.17   950.5  180.74  949.81  211.37  947.86  245.07  946.92  318.59  947.74
  416.62  945.29  471.76  944.68  523.83  942.56  579.94  941.12  585.04   941.1
  591.56  941.16  708.88  944.42  785.34  945.55  843.44  948.13  874.03  950.59
  895.43  953.48  907.67   956.2  926.02  958.41  935.19  960.97  938.25  962.43
#Mann= 3 , 0 , 0
       0     .09       0  579.94     .04       0  591.56     .09       0
Bank Sta=579.94,591.56
XS Rating Curve= 0 ,0
Exp/Cntr=0.3,0.1

Type RM Length L Ch R = 1 ,4663.44 ,107.08,91.44,88.58
XS GIS Cut Line= 5
     635785.7508    4334644.0053     635309.8089    4334818.7933
      635147.345    4334859.9089     635093.4687    4334885.4891
     634797.2655    4335046.1727
#Sta/Elev= 30
       0   962.5   64.53  959.97   92.19  957.35  135.21  956.55  175.15  954.86
  205.88  952.98   215.1  950.98  218.17  950.74  267.34  950.38  291.92  948.87
  322.65  948.93  368.74  947.84  457.86  946.72  473.22  944.97  500.88  944.67
  561.87  942.83  586.24   942.9  631.95   941.5  656.33  941.72  713.37  941.15
  719.34  940.96   725.3  941.12  783.26  943.56  804.71  943.29  816.96  944.18
  884.36  945.58  979.32  949.59 1034.47     956 1052.85  959.18 1071.23  963.48
#Mann= 3 , 0 , 0
       0     .09       0  713.37     .04       0   725.3     .09       0
Bank Sta=713.37,725.3
XS Rating Curve= 0 ,0
Exp/Cntr=0.3,0.1

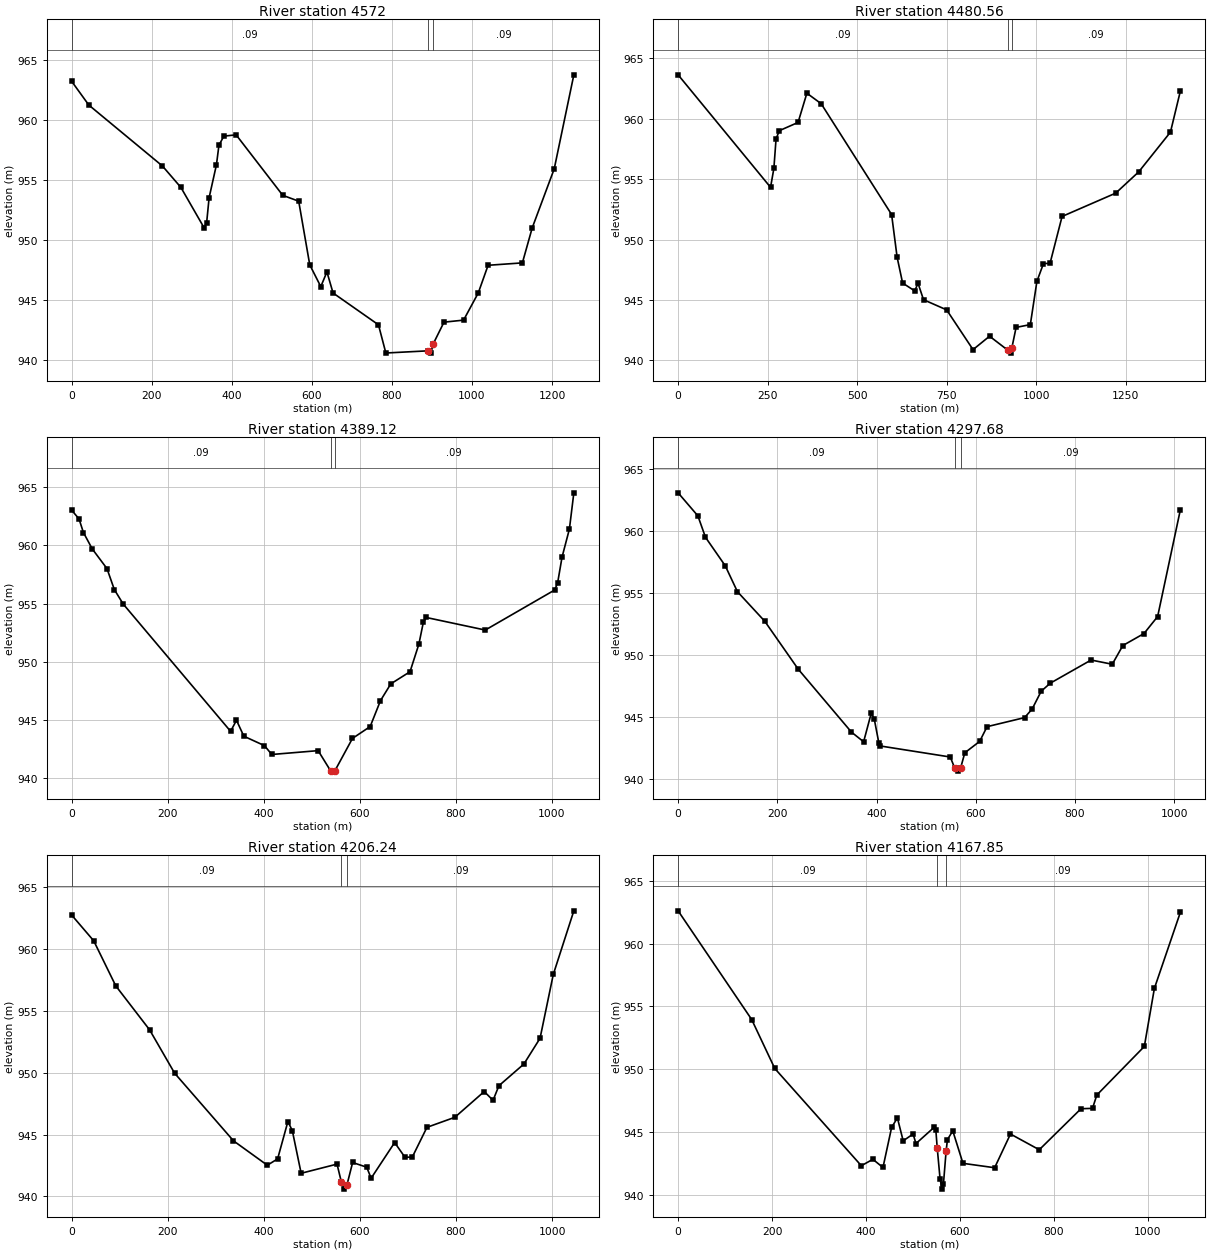
Type RM Length L Ch R = 1 ,4572    ,73.49,91.44,92.02
XS GIS Cut Line= 6
     635892.9073    4334476.7883     635119.8371    4334755.1382
     635070.2276    4334788.4758     635062.0931    4334799.0262
     635053.8451     4334806.144     634773.9822    4335014.4227
#Sta/Elev= 30
       0  963.24   42.92  961.26  226.87  956.18  272.86   954.4  331.11  951.02
  337.25  951.47  343.38  953.54  361.77   956.3  367.91  957.91  380.17  958.67
  410.83  958.78  527.33  953.74  567.19  953.25  594.78  947.95  622.37  946.13
   637.7  947.36  653.03   945.6  766.47  942.95  784.86   940.6  889.42  940.78
  897.47  940.59  902.92  941.34  930.12  943.17  979.08  943.34 1015.81  945.61
 1040.29  947.91 1125.97  948.11 1150.45  951.02 1205.54  955.95  1254.5  963.78
#Mann= 3 , 0 , 0
       0     .09       0  889.42     .04       0  902.92     .09       0
Bank Sta=889.42,902.92
XS Rating Curve= 0 ,0
Exp/Cntr=0.3,0.1

Type RM Length L Ch R = 1 ,4480.56 ,80.5,91.44,82.93
XS GIS Cut Line= 5
     635899.2573    4334453.5049     635019.5466    4334719.8692
     635013.4553    4334723.5213      635006.907    4334729.2516
      634563.638    4334878.9557
#Sta/Elev= 30
       0  963.63  258.22  954.32  267.45  955.88  273.59  958.33  282.82  959.01
  335.08  959.69  359.67  962.11  399.63  961.24  596.37  952.07  611.74  948.54
  627.11   946.4  660.93  945.75  670.15  946.38  685.52  945.02  750.08  944.18
  823.85  940.89  869.97     942  921.52  940.83  929.15   940.6  932.05     941
  944.13  942.73  983.88  942.96 1002.23  946.54 1020.58  948.01 1038.92  948.03
 1072.56  951.91  1222.4  953.84 1286.62   955.6  1375.3  958.89 1402.82  962.27
#Mann= 3 , 0 , 0
       0     .09       0  921.52     .04       0  932.05     .09       0
Bank Sta=921.52,932.05
XS Rating Curve= 0 ,0
Exp/Cntr=0.3,0.1

Type RM Length L Ch R = 1 ,4389.12 ,68.62,91.44,94.95
XS GIS Cut Line= 6
     635520.3732     4334510.655       635058.07    4334620.2446
     635016.8334    4334643.0064     634997.6629    4334664.3565
     634986.3677    4334659.1384     634527.6546    4334809.1056
#Sta/Elev= 30
       0  963.02   15.33  962.27   24.52   961.1   42.91  959.69   73.57     958
   88.89   956.2  107.28  954.96  331.05  944.02  343.31  944.97  358.64   943.6
  401.55  942.79  416.87  942.03  513.38  942.36  539.43  940.62   542.3   940.6
  548.04  940.61  584.87  943.41  621.76  944.43  643.27  946.66  664.79   948.1
  704.75  949.14   723.2  951.51  732.42  953.37  738.56   953.8  861.52  952.72
 1005.99  956.16 1012.14  956.76 1021.36  958.98 1036.73   961.4 1045.96  964.51
#Mann= 3 , 0 , 0
       0     .09       0  539.43     .04       0  548.04     .09       0
Bank Sta=539.43,548.04
XS Rating Curve= 0 ,0
Exp/Cntr=0.3,0.1

Type RM Length L Ch R = 1 ,4297.68 ,82.55,91.44,90.35
XS GIS Cut Line= 5
     635536.0884        4334488.     634978.3162    4334572.1606
     634970.3597    4334571.8441     634884.4325    4334584.3405
     634549.1906    4334697.0213
#Sta/Elev= 30
       0  963.07   39.85  961.21   55.18  959.48   95.04  957.18  119.56  955.09
  174.74   952.7  242.19  948.83  349.49  943.75  374.01  942.97  389.34  945.27
  395.47  944.81  404.67  942.89  407.74  942.63  548.76  941.74  557.95  940.82
  564.09   940.6  569.39  940.82  578.04  942.08  607.98     943  622.95  944.19
  698.51  944.92  713.76  945.61  732.05  947.05  750.35   947.7  832.67  949.57
  875.35  949.23  896.69  950.74  939.38  951.71  966.82  953.08 1012.55  961.68
#Mann= 3 , 0 , 0
       0     .09       0  557.95     .04       0  569.39     .09       0
Bank Sta=557.95,569.39
XS Rating Curve= 0 ,0
Exp/Cntr=0.3,0.1

Type RM Length L Ch R = 1 ,4206.24 ,25.12,38.39,46.18
XS GIS Cut Line= 6
     635533.4426    4334464.1875      635044.047    4334487.2471
     634999.5715    4334483.0638     634955.1373     4334481.115
     634930.9374    4334490.4221     634528.0239     4334667.917
#Sta/Elev= 30
       0  962.72   45.93  960.64   91.86     957  162.29  953.45  214.35  949.95
  336.83  944.49  407.26  942.52   428.7  943.03  450.13  946.05  459.32  945.31
  477.69  941.87   552.4  942.61   561.3  941.18  567.23  940.59  573.16  940.95
  584.85  942.74  614.19  942.36  623.36  941.47  672.28  944.35  693.68  943.17
  708.97  943.17  739.55  945.58  797.64  946.39  858.79  948.47  877.13  947.76
  889.36  948.94  941.34  950.69  974.97  952.77 1002.49  957.92  1045.3  963.06
#Mann= 3 , 0 , 0
       0     .09       0   561.3     .04       0  573.16     .09       0
Bank Sta=561.3,573.16
XS Rating Curve= 0 ,0
Exp/Cntr=0.3,0.1

Type RM Length L Ch R = 1 ,4167.85 ,19.02,16.3,19.67
XS GIS Cut Line= 6
     635528.1509    4334443.0208     635050.2657    4334475.8557
     635017.8807    4334459.5574     634974.0656    4334444.3173
     634936.2301    4334439.0521     634520.0864    4334654.6878
#Sta/Elev= 30
       0   962.6   156.6  953.96  205.73  950.07  389.96  942.34  414.53  942.85
  436.02   942.2  454.45  945.39  466.73  946.14  479.01  944.32  500.16  944.86
   506.2   944.1  545.44  945.41  548.45  945.21  551.47  943.76  557.51   941.3
  561.79  940.48  564.64  940.86  570.35  943.48  573.21  944.42  584.62  945.11
   606.3  942.53  673.69  942.18  707.39  944.86  768.66  943.61  857.49  946.87
     882   946.9  891.19  947.96  992.28  951.82 1013.72  956.44 1068.86  962.47
#Mann= 3 , 0 , 0
       0     .09       0  551.47     .04       0  570.35     .09       0
Bank Sta=551.47,570.35
XS Rating Curve= 0 ,0
Exp/Cntr=0.3,0.1

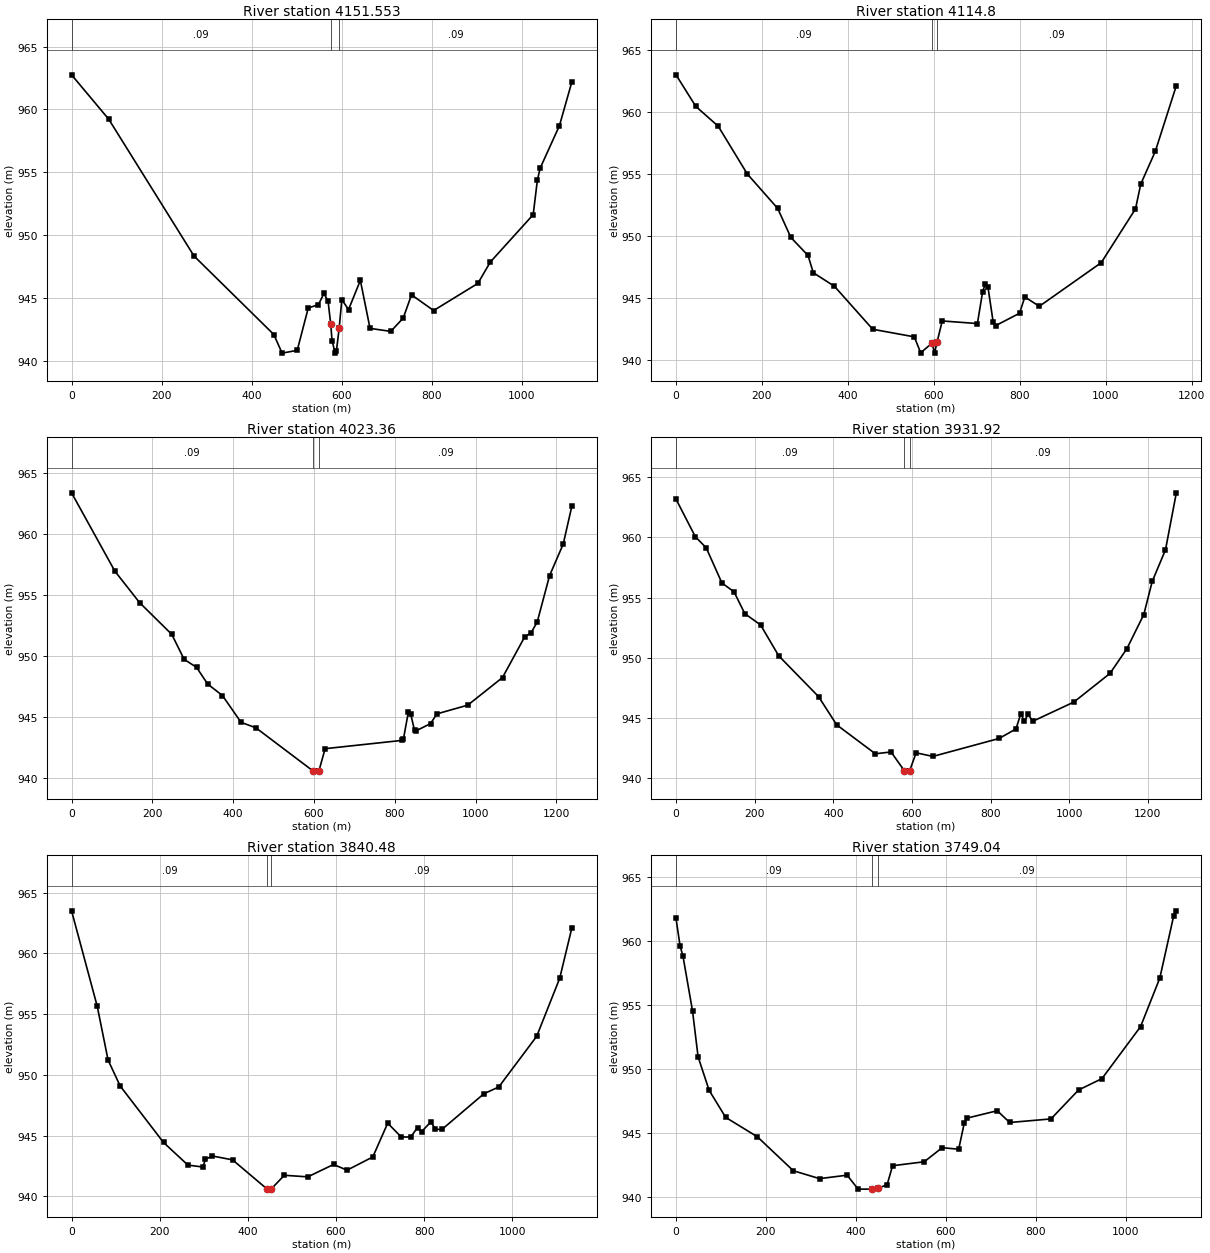
Type RM Length L Ch R = 1 ,4151.553,39.4,36.75,32.24
XS GIS Cut Line= 6
     635557.2551    4334395.3957     635033.8655     4334445.956
     634988.7804     4334432.621     634981.5837    4334427.7526
     634938.4037    4334419.2859     634506.8572    4334641.4586
#Sta/Elev= 30
       0  962.75   82.54  959.22  272.08  948.33   449.4  942.08  467.74   940.6
  501.37  940.82  525.83  944.19  548.48  944.46  560.72  945.35   569.9  944.73
  575.85   942.9  578.75   941.6  585.55  940.61  588.54  940.79  594.53  942.58
  600.51  944.85  615.47  944.07  641.64  946.39  663.14  942.57  709.22  942.33
  736.87  943.39   755.3  945.24  804.45  943.99  902.76  946.15  930.41  947.85
 1025.64  951.62 1034.85  954.34    1041  955.31 1084.01  958.71 1111.65   962.2
#Mann= 3 , 0 , 0
       0     .09       0  575.85     .04       0  594.53     .09       0
Bank Sta=575.85,594.53
XS Rating Curve= 0 ,0
Exp/Cntr=0.3,0.1

Type RM Length L Ch R = 1 ,4114.8  ,113.44,91.44,79.36
XS GIS Cut Line= 6
     635581.0677    4334350.4164     635062.7002    4334414.2925
     635029.8395    4334401.8412     634960.4183    4334387.2361
     634915.0624    4334387.0404     634490.9821    4334633.5211
#Sta/Elev= 30
       0  962.97   46.08  960.43   98.31  958.83   165.9  954.99  236.57  952.22
  267.29  949.88  307.23  948.43  319.52  947.04  368.67  945.95  457.77  942.49
   554.5  941.88  569.25   940.6  595.86  941.37  601.61  940.57  607.35  941.44
   619.5  943.16  701.32  942.95  713.58  945.52  719.71  946.15  725.84   945.9
  738.11  943.05  744.24  942.79  799.42  943.78  811.68  945.09   845.4  944.34
  989.49  947.85  1069.2  952.18 1081.46  954.18 1115.18   956.8 1164.23   962.1
#Mann= 3 , 0 , 0
       0     .09       0  595.86     .04       0  607.35     .09       0
Bank Sta=595.86,607.35
XS Rating Curve= 0 ,0
Exp/Cntr=0.3,0.1

Type RM Length L Ch R = 1 ,4023.36 ,94.04,91.44,87.12
XS GIS Cut Line= 5
     635600.9644    4334212.1449     635041.1571    4334298.6032
     634953.0492    4334307.7163     634915.7239    4334307.9298
     634472.7788    4334627.0124
#Sta/Elev= 30
       0  963.41  107.17  956.99   168.4  954.41  248.01  951.81  278.63  949.76
  309.25  949.11   336.8  947.74  373.55  946.79  419.47   944.6  456.22  944.15
  596.99  940.63   603.1   940.6  612.26  940.63  627.53  942.44  818.09  943.12
  821.16   943.2  833.43  945.42  839.56  945.25  848.76  943.94  851.83  943.89
  888.63   944.5  903.96  945.29  980.64  946.01 1066.51  948.27 1121.71  951.62
 1137.05  951.93 1152.38  952.82 1183.05  956.63 1216.79  959.21 1238.26  962.34
#Mann= 3 , 0 , 0
       0     .09       0  596.99     .04       0  612.26     .09       0
Bank Sta=596.99,612.26
XS Rating Curve= 0 ,0
Exp/Cntr=0.3,0.1

Type RM Length L Ch R = 1 ,3931.92 ,131.16,91.44,53.45
XS GIS Cut Line= 6
      635558.631    4334085.1446     634989.4369    4334215.4577
     634982.1284    4334214.0398     634968.7988    4334213.5693
     634897.2877     4334228.126     634455.8454    4334627.0124
#Sta/Elev= 30
       0  963.17   49.17  960.05   76.83  959.13  116.78  956.21  147.52  955.48
  175.18  953.66  215.13  952.73  261.23  950.17  362.65  946.78  408.74  944.44
  507.09  942.04  547.04  942.19  580.85  940.63  583.92   940.6  594.03  940.61
  610.78  942.12  653.35  941.82  821.82  943.31  864.76   944.1  877.02  945.36
  886.23  944.74  895.43  945.31  907.69  944.74 1011.97  946.33 1103.97  948.71
  1146.9  950.76 1189.84  953.59 1211.31  956.34 1245.04  958.96 1272.64  963.69
#Mann= 3 , 0 , 0
       0     .09       0  580.85     .04       0  594.03     .09       0
Bank Sta=580.85,594.03
XS Rating Curve= 0 ,0
Exp/Cntr=0.3,0.1

Type RM Length L Ch R = 1 ,3840.48 ,116.03,91.44,68.87
XS GIS Cut Line= 5
      635249.597    4333809.9774     634975.7932    4334100.2638
     634902.6001    4334170.7022      634873.431    4334190.7535
     634451.6121     4334616.429
#Sta/Elev= 30
       0  963.51   58.32  955.64   82.88  951.22   110.5  949.08  208.73  944.44
  263.98  942.58  297.75  942.42  303.89  943.05  319.23  943.33  365.28  943.01
  443.86   940.6  452.82   940.6   482.7  941.74  536.02  941.61  594.41  942.63
  625.14  942.16  683.53  943.25  717.34  946.03  748.07  944.89  769.58  944.89
  784.95  945.67  794.17  945.33  815.68  946.15   824.9  945.53  840.27  945.51
  935.54  948.45  969.34  949.01 1055.39  953.18 1107.64  957.96 1135.29  962.12
#Mann= 3 , 0 , 0
       0     .09       0  443.86     .04       0  452.82     .09       0
Bank Sta=443.86,452.82
XS Rating Curve= 0 ,0
Exp/Cntr=0.3,0.1

Type RM Length L Ch R = 1 ,3749.04 ,73.46,91.44,103.97
XS GIS Cut Line= 6
     635059.0966    4333699.9105     634871.2971     4334062.404
     634857.8314    4334095.3201     634854.4035    4334108.4999
     634831.2524    4334151.4948      634438.912    4334614.3123
#Sta/Elev= 30
       0  961.77    9.21  959.59   15.35  958.85   36.83  954.52   49.11  950.95
   73.67  948.33   110.5  946.21   181.1  944.69  260.91  942.04  319.24  941.42
  380.63  941.69  405.18   940.6  435.38   940.6  449.26  940.66  469.64  940.95
  481.85  942.43  552.23  942.74  592.07  943.84  628.84  943.72   641.1  945.74
  647.23  946.15  714.64  946.73  742.22  945.81  834.15  946.09  895.44  948.35
  947.53  949.24 1033.33   953.3 1076.23   957.1 1106.87  961.93    1113  962.36
#Mann= 3 , 0 , 0
       0     .09       0  435.38     .04       0  449.26     .09       0
Bank Sta=435.38,449.26
XS Rating Curve= 0 ,0
Exp/Cntr=0.3,0.1

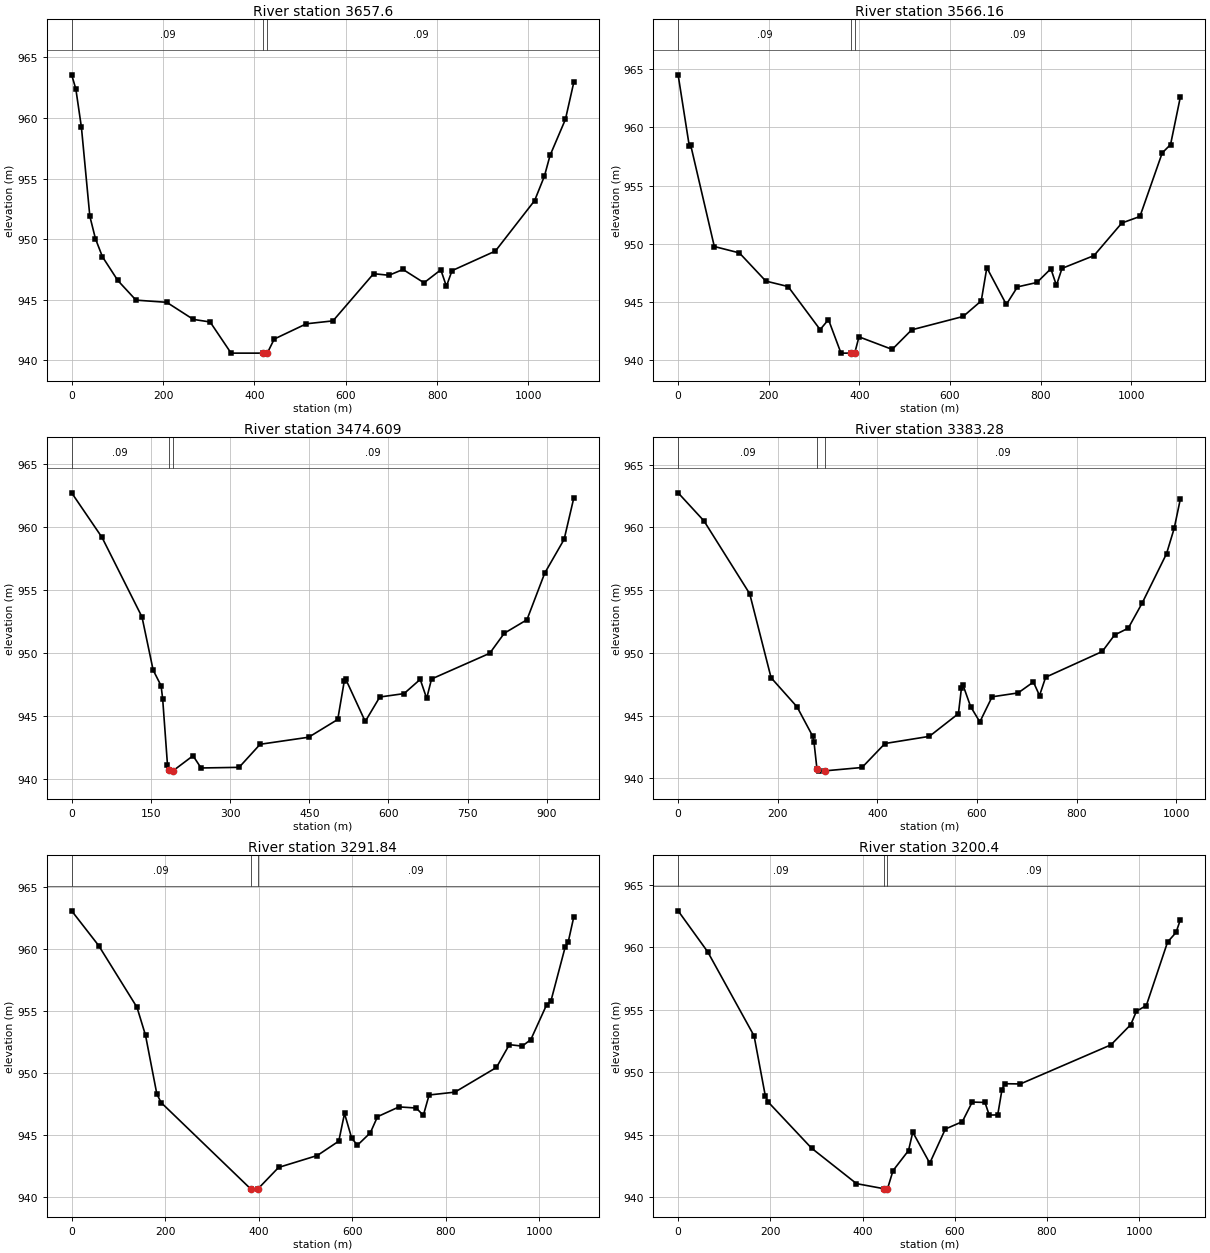
Type RM Length L Ch R = 1 ,3657.6  ,83.01,91.44,105.85
XS GIS Cut Line= 4
     635010.4132    4333685.0938     634808.2289    4334020.7786
     634763.3408    4334061.5587     634424.0953    4334612.1957
#Sta/Elev= 30
       0  963.55    9.18  962.38   21.43  959.21    39.8  951.89   52.05  950.04
   67.35  948.55  101.03  946.59  140.83  944.97  208.18  944.79  266.35  943.38
  303.09  943.17  349.01   940.6  419.61   940.6  428.26   940.6  443.42  941.76
  513.82  943.02  572.06  943.26  660.95  947.15  694.67  947.02  725.32   947.5
   771.3   946.4  808.08  947.47  820.34  946.11   832.6   947.4  927.62  949.02
 1013.45  953.18  1034.9   955.2 1047.16   956.9 1080.88  959.88 1099.27  962.95
#Mann= 3 , 0 , 0
       0     .09       0  419.61     .04       0  428.26     .09       0
Bank Sta=419.61,428.26
XS Rating Curve= 0 ,0
Exp/Cntr=0.3,0.1

Type RM Length L Ch R = 1 ,3566.16 ,106.78,91.55,33.28
XS GIS Cut Line= 4
     634963.8464    4333678.7438     634747.5328    4333958.2429
     634657.8956    4334021.8231     634388.1119    4334607.9623
#Sta/Elev= 30
       0  964.51   24.59  958.41   27.66  958.49   79.91  949.76  135.22  949.21
  193.62  946.79  242.79  946.32  313.48  942.62  331.91  943.48  359.53   940.6
   381.3   940.6  390.06  940.63  399.22     942  472.54  940.92  515.56   942.6
  629.24  943.75  669.19  945.09  681.48  947.94  724.49  944.78  749.08  946.29
  792.09  946.67  822.82  947.85  835.11  946.42   847.4  947.88  918.07  948.98
  979.52  951.78 1019.46  952.34 1068.62   957.8 1087.06  958.52 1108.57  962.59
#Mann= 3 , 0 , 0
       0     .09       0   381.3     .04       0  390.06     .09       0
Bank Sta=381.3,390.06
XS Rating Curve= 0 ,0
Exp/Cntr=0.3,0.1

Type RM Length L Ch R = 1 ,3474.609,99.31,91.33,6.18
XS GIS Cut Line= 6
     634720.4293    4333752.8273     634647.8802    4333860.9758
     634672.1606     4333932.273     634644.0791    4334012.6743
     634650.4291    4334021.8024     634371.1786    4334607.9623
#Sta/Elev= 30
       0  962.68   57.54  959.14  133.24  952.83  154.33  948.62  169.39  947.37
  172.41  946.32  181.45  941.12  184.26  940.68  187.47   940.6  191.18   940.6
  229.88  941.82  245.09  940.85  317.14   940.9  356.96  942.73  448.84  943.29
  503.96   944.7  516.22  947.72  519.28  947.88  556.03  944.54  583.59  946.48
  629.53  946.75  660.16  947.88  672.41  946.37   681.6  947.91  791.85  949.95
  819.42  951.54  862.29  952.61  895.98  956.31  932.73  958.99  951.11  962.29
#Mann= 3 , 0 , 0
       0     .09       0  184.26     .04       0  191.18     .09       0
Bank Sta=184.26,191.18
XS Rating Curve= 0 ,0
Exp/Cntr=0.3,0.1

Type RM Length L Ch R = 1 ,3383.28 ,87.24,91.44,69.08
XS GIS Cut Line= 6
      634704.907    4333750.9752     634605.6881    4333822.4128
     634575.3645    4333953.8528     634608.0712    4333976.7745
     634644.6855    4334023.9676     634356.3619    4334607.9623
#Sta/Elev= 30
       0  962.75   51.96  960.51  143.72  954.71  186.64  948.02  238.76   945.7
  270.09  943.37  272.68  942.94  278.81  940.73  281.89  940.58  294.16   940.6
  369.25  940.87  415.33  942.78  504.42  943.35  562.79  945.16  568.94  947.24
  572.01  947.43  587.37  945.71   605.8   944.5  630.38   946.5  682.61  946.81
  713.33  947.68  725.61   946.6   737.9  948.06  851.57  950.11  876.15  951.42
   903.8  951.97  931.45  953.95   980.6   957.9  995.96  959.92 1008.25  962.24
#Mann= 3 , 0 , 0
       0     .09       0  278.81     .04       0  294.16     .09       0
Bank Sta=278.81,294.16
XS Rating Curve= 0 ,0
Exp/Cntr=0.3,0.1

Type RM Length L Ch R = 1 ,3291.84 ,31.07,91.44,109.43
XS GIS Cut Line= 6
     634696.4403    4333748.4617     634593.2526    4333818.3118
     634519.9342    4334020.9249     634547.7011    4334046.3263
     634602.0875    4334075.6937     634273.6353    4334618.8103
#Sta/Elev= 30
       0  963.04   57.74  960.24  139.78  955.26  157.99  953.01  182.27  948.27
  191.37  947.58  383.52   940.6  398.05   940.6  442.71  942.35   525.5  943.31
  571.49  944.47  583.75   946.7  599.08  944.71  611.35  944.14  638.95  945.14
  654.28  946.44  700.27  947.23  737.07  947.14   752.4  946.55  764.66  948.19
  819.85  948.42  908.77  950.41  936.37  952.25  963.97  952.13  982.36  952.66
 1016.09  955.46 1025.29  955.76 1055.95  960.14 1062.09  960.49 1074.35  962.57
#Mann= 3 , 0 , 0
       0     .09       0  383.52     .04       0  398.05     .09       0
Bank Sta=383.52,398.05
XS Rating Curve= 0 ,0
Exp/Cntr=0.3,0.1

Type RM Length L Ch R = 1 ,3200.4  ,23.29,91.44,100.13
XS GIS Cut Line= 6
     634689.0761    4333743.1369     634582.1842    4333814.0454
     634502.6613    4334031.0397      634498.851    4334045.9004
      634513.588    4334151.5159     634178.9804    4334659.0601
#Sta/Elev= 30
       0  962.91   64.14  959.63  164.76   952.9  189.09   948.1  195.17  947.61
  289.44  943.91  386.91  941.07  446.81  940.66  447.84  940.63  453.94  940.63
  466.13  942.11  499.78  943.72  508.99  945.19  545.84  942.71  579.61  945.44
  616.45  946.03  637.94   947.6  665.58  947.57  674.79  946.56  693.21  946.57
  702.42  948.58  708.56  949.07  742.33  949.05  938.83  952.18  981.82   953.8
   994.1  954.87 1015.59  955.33 1061.65  960.41 1080.07  961.18 1089.28  962.19
#Mann= 3 , 0 , 0
       0     .09       0  446.81     .04       0  453.94     .09       0
Bank Sta=446.81,453.94
XS Rating Curve= 0 ,0
Exp/Cntr=0.3,0.1

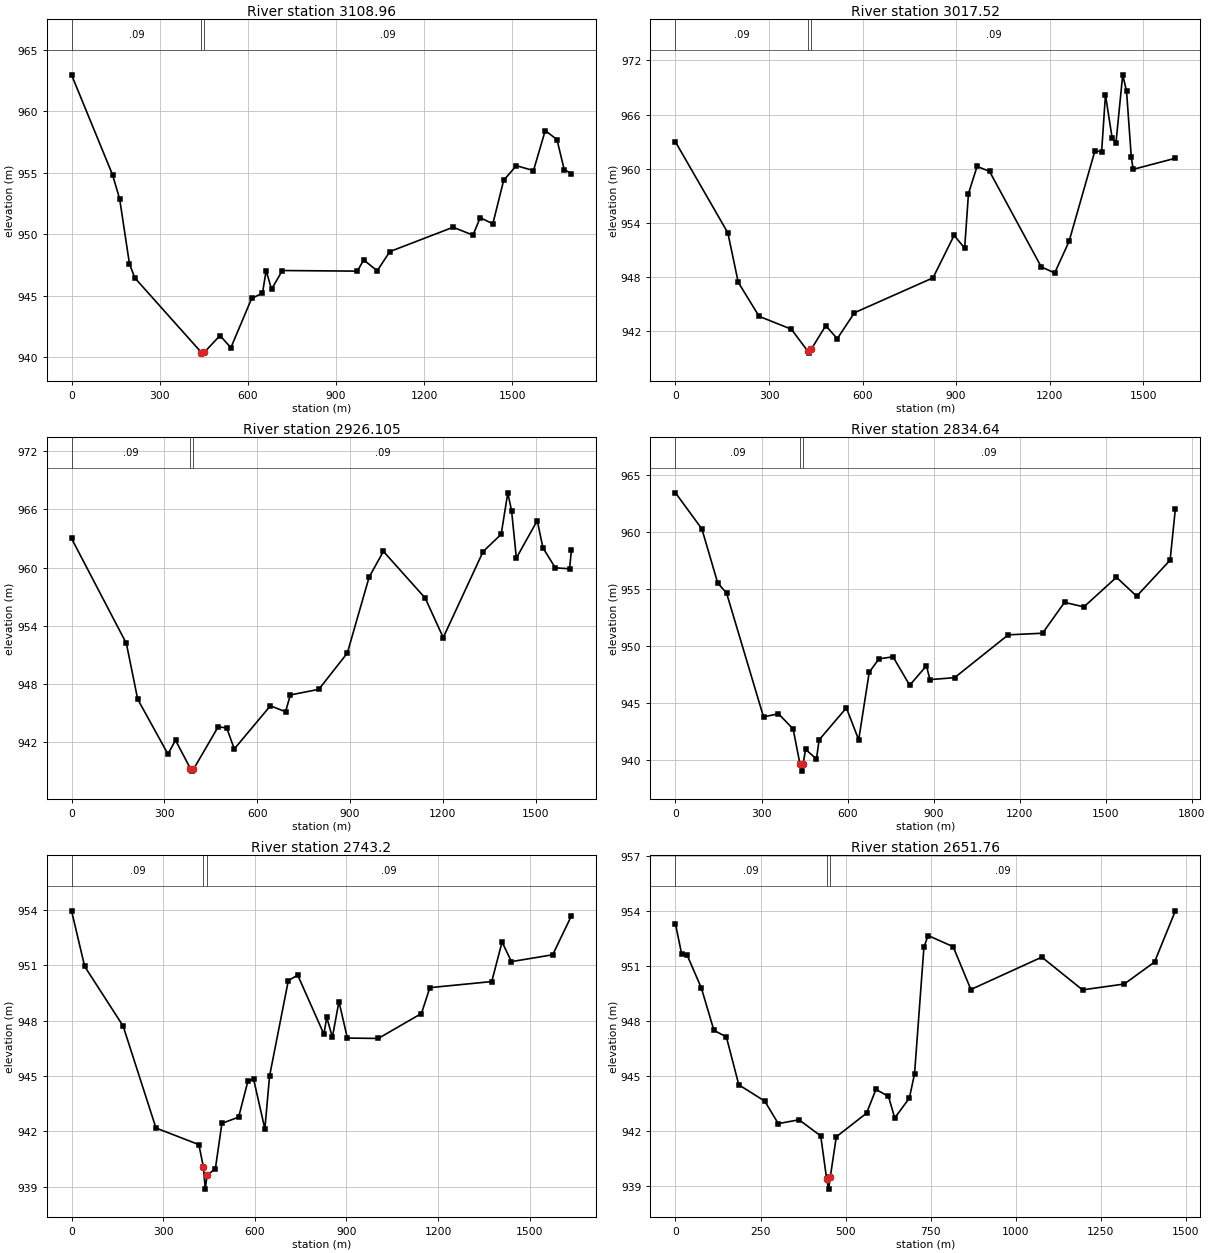
Type RM Length L Ch R = 1 ,3108.96 ,71.44,91.44,94.5
XS GIS Cut Line= 6
     634686.3597    4333736.9104     634579.2032    4333805.7022
     634518.3489    4333885.0773     634475.5159    4334042.7617
     634428.5769    4334080.8739     633475.9062    4334888.8379
#Sta/Elev= 30
       0  962.98  139.46  954.85  163.71  952.88  197.05   947.6  215.23  946.46
  441.83  940.39  444.49  940.34  451.28   940.4  505.16  941.77  542.03  940.78
  612.71  944.79  649.59  945.22  661.88  947.05  680.31  945.54  717.19  947.06
  972.24  947.01  993.75  947.92 1039.84  947.04 1082.86   948.6 1297.97  950.58
 1365.57  949.94 1390.15  951.36 1433.17  950.86 1470.05   954.4 1513.07  955.59
 1571.45  955.19  1611.4  958.45 1651.35  957.71 1675.93  955.27 1700.52  954.95
#Mann= 3 , 0 , 0
       0     .09       0  441.83     .04       0  451.28     .09       0
Bank Sta=441.83,451.28
XS Rating Curve= 0 ,0
Exp/Cntr=0.3,0.1

Type RM Length L Ch R = 1 ,3017.52 ,96.46,91.41,87.28
XS GIS Cut Line= 6
      634681.068    4333730.2958     634569.9428    4333800.4105
     634435.6245    4333980.9198      634389.507     4334004.922
     634265.6026    4334058.1961     633464.8642    4334752.5817
#Sta/Elev= 30
       0  962.96  167.88  952.88  201.33  947.39  268.22  943.62  371.69  942.19
  423.59  939.79  427.99  939.54  435.82  939.99  481.93  942.59  518.81  941.14
  574.12  944.02  826.04  947.89  893.63   952.6  927.42  951.18  939.71  957.24
  967.36  960.25 1007.29  959.69 1173.19   949.1  1216.2  948.43 1262.28  951.93
 1345.23  961.97 1366.73  961.87 1379.02  968.19 1400.53  963.37 1412.82  962.88
 1434.32   970.4 1446.61   968.6 1461.97  961.24 1468.11  959.92 1603.29  961.15
#Mann= 3 , 0 , 0
       0     .09       0  423.59     .04       0  435.82     .09       0
Bank Sta=423.59,435.82
XS Rating Curve= 0 ,0
Exp/Cntr=0.3,0.1

Type RM Length L Ch R = 1 ,2926.105,53.22,91.47,99.9
XS GIS Cut Line= 3
     634676.6583    4333724.6734     634333.3703    4333930.3034
     633411.9474     4334722.816
#Sta/Elev= 30
       0  963.01  177.17  952.18  213.83  946.42  311.58  940.76  336.01  942.19
  384.13  939.27  387.94     939  394.05  939.19  473.82  943.57  501.44  943.46
     526  941.29  642.62  945.74  691.73  945.13  707.07  946.86  799.15  947.44
  891.22  951.18  961.81  959.03 1007.84  961.68 1142.88  956.86  1201.2  952.78
  1330.1  961.66 1388.41  963.44  1409.9  967.72 1422.17  965.85 1437.52  960.99
 1505.04  964.85 1523.45  962.04 1563.35  959.98 1609.39  959.88 1615.52  961.79
#Mann= 3 , 0 , 0
       0     .09       0  384.13     .04       0  394.05     .09       0
Bank Sta=384.13,394.05
XS Rating Curve= 0 ,0
Exp/Cntr=0.3,0.1

Type RM Length L Ch R = 1 ,2834.64 ,134.29,91.44,62.69
XS GIS Cut Line= 6
     634689.8875    4333642.6524     634396.3239      4333849.63
     634333.1545    4333848.9685     634296.8277    4333843.4465
     634268.3315    4333850.6221     633274.3638     4334616.321
#Sta/Elev= 30
       0  963.43    92.1  960.26  147.36  955.51  178.06  954.64     307  943.77
  359.19  944.04  410.33  942.71  433.89  939.66  439.66  939.01  445.23  939.65
   453.6  940.92  491.63  940.07  500.83  941.75  595.93  944.56  638.88  941.76
  675.69  947.69  709.44  948.86  758.52  949.04  816.81  946.55  875.09  948.25
  887.36  947.04  973.26  947.21 1160.39  950.97 1280.03  951.11 1356.72  953.82
 1424.21  953.42 1537.72  956.02 1608.28  954.36 1724.85  957.52 1743.26  962.04
#Mann= 3 , 0 , 0
       0     .09       0  433.89     .04       0  445.23     .09       0
Bank Sta=433.89,445.23
XS Rating Curve= 0 ,0
Exp/Cntr=0.3,0.1

Type RM Length L Ch R = 1 ,2743.2  ,70.73,91.44,101.17
XS GIS Cut Line= 5
     634605.2206    4333507.7146     634295.5136     4333744.741
     634251.4454    4333793.4423     634190.8554    4333873.6197
     633308.7597    4334497.2582
#Sta/Elev= 30
       0  953.94   42.99  950.93   168.9   947.7  276.38  942.18  416.87  941.28
   431.8  940.05  437.77  938.87  443.74  939.62  470.91  939.98  492.22  942.43
  547.04  942.77  577.66  944.74  596.07  944.82   632.9  942.13  648.25  944.99
  709.63  950.16  740.32  950.46  826.25  947.26  835.46  948.18  853.87  947.09
  875.35  949.03  902.97  947.05 1004.25  947.03 1145.43  948.38 1173.05  949.78
  1375.6  950.11 1409.36  952.25 1440.05  951.19 1575.09  951.56 1636.47  953.67
#Mann= 3 , 0 , 0
       0     .09       0   431.8     .04       0  443.74     .09       0
Bank Sta=431.8,443.74
XS Rating Curve= 0 ,0
Exp/Cntr=0.3,0.1

Type RM Length L Ch R = 1 ,2651.76 ,89.44,91.42,90.53
XS GIS Cut Line= 5
     634589.3456    4333481.2562     634229.3884    4333699.9773
     634200.6166    4333713.5491     634196.2224    4333713.9745
     633359.0306    4334282.9453
#Sta/Elev= 30
       0  953.31   18.31  951.65   33.57  951.64    76.3   949.8  112.93   947.5
  149.56  947.14  186.18  944.52  262.49  943.63  302.16   942.4  363.21  942.61
  426.98  941.73  444.33  939.39  450.12  938.82  455.22  939.49  472.76  941.68
  561.72  942.97  589.32  944.27  626.13  943.89  644.54  942.71  687.48  943.79
  702.82  945.12  730.42  952.05  742.69  952.68  816.31  952.07  868.45  949.73
 1077.04   951.5 1196.66  949.71 1319.36  950.03 1408.31  951.23 1469.66  954.03
#Mann= 3 , 0 , 0
       0     .09       0  444.33     .04       0  455.22     .09       0
Bank Sta=444.33,455.22
XS Rating Curve= 0 ,0
Exp/Cntr=0.3,0.1

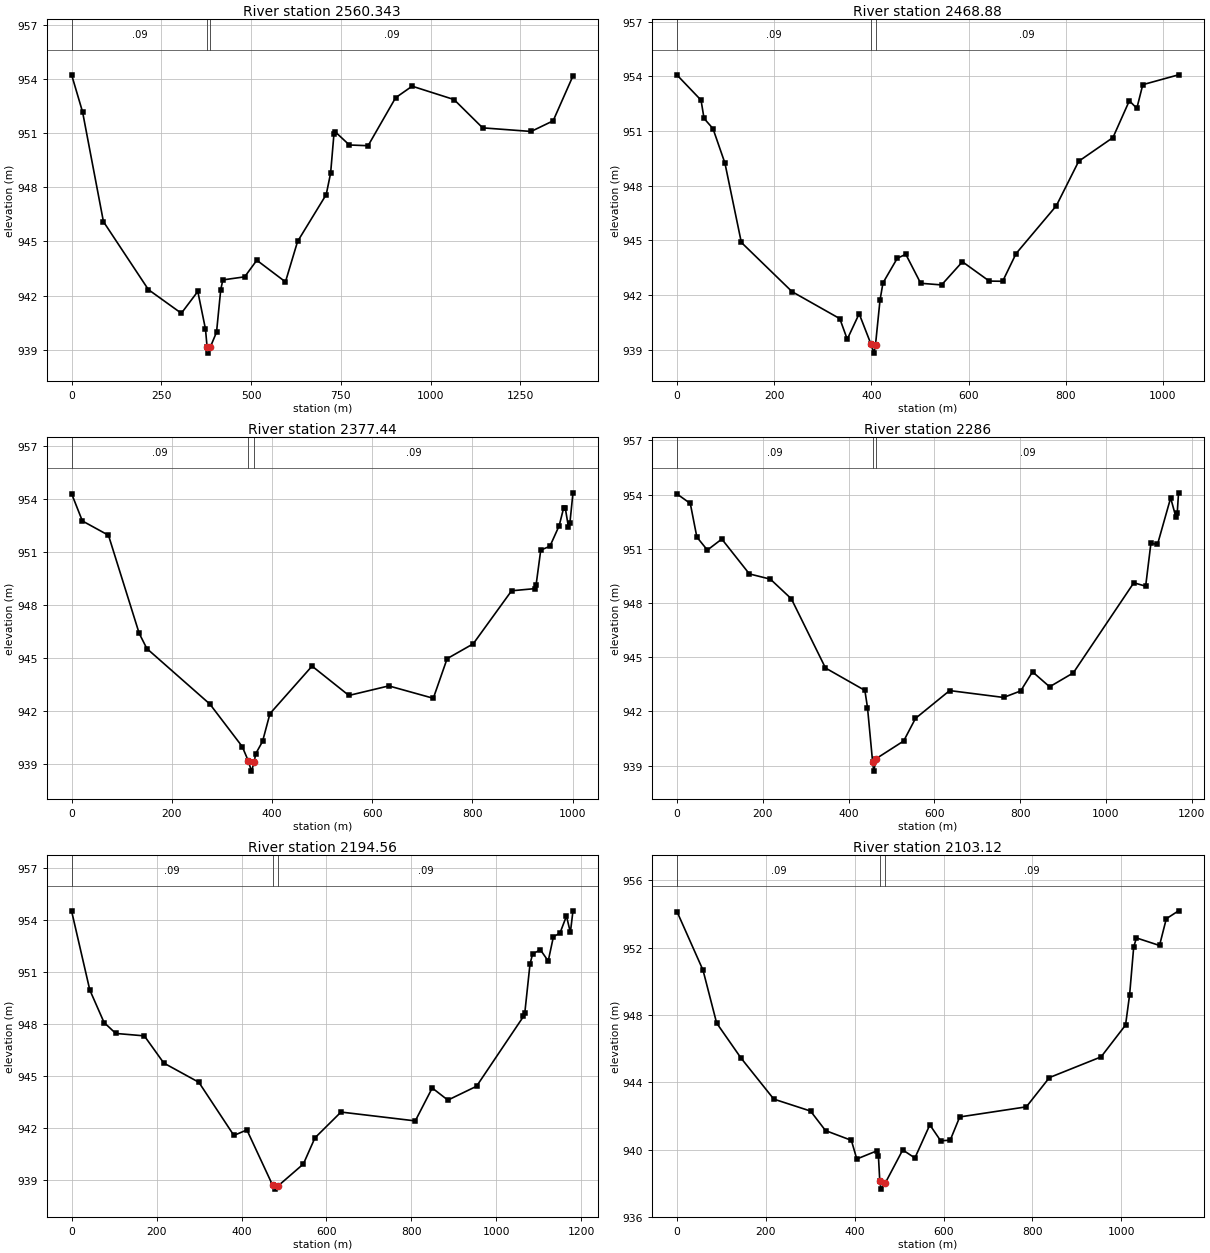
Type RM Length L Ch R = 1 ,2560.343,45.96,91.46,103.71
XS GIS Cut Line= 5
     634494.0954    4333457.4437     634155.4517    4333634.3914
     634152.5033    4333637.0833     634111.3206    4333659.6358
     633359.0306    4334261.7786
#Sta/Elev= 30
       0  954.24   30.57  952.18   88.64   946.1  213.97  942.33  305.67  941.02
  351.52  942.23  372.92  940.14   377.5  939.13  379.03  938.81  386.08  939.13
  403.69  939.97  415.42  942.33  421.29  942.87  482.13  943.04  515.89  943.96
  595.68  942.76  629.43     945  709.22   947.6   721.5  948.79   730.7  950.94
  733.77  951.09  773.67  950.35  825.84  950.31  902.56  952.97  948.59  953.61
  1065.2  952.87 1144.99   951.3 1280.01   951.1 1341.39  951.69 1396.63  954.18
#Mann= 3 , 0 , 0
       0     .09       0   377.5     .04       0  386.08     .09       0
Bank Sta=377.5,386.08
XS Rating Curve= 0 ,0
Exp/Cntr=0.3,0.1

Type RM Length L Ch R = 1 ,2468.88 ,101.74,91.44,81.71
XS GIS Cut Line= 5
     634496.0798    4333409.8186     634199.8457    4333559.2818
     634105.5385    4333547.7792     634064.8255    4333564.2575
     633685.7917    4333978.6739
#Sta/Elev= 30
       0  954.06   49.16  952.69    55.3  951.69   73.73  951.13   98.31  949.24
  132.11  944.89  236.56  942.19  334.87  940.71  350.19  939.58  374.71  940.98
  399.23   939.3  405.36  938.82  408.42  939.29  417.62  941.72  423.75  942.67
  453.16  944.02  470.73  944.24  501.42  942.65  544.39  942.56  587.35  943.83
  642.59  942.77  670.21  942.76  697.83  944.28  780.69   946.9  826.72  949.34
  897.31  950.64  931.07  952.66  946.41  952.24  958.69  953.54 1032.34  954.08
#Mann= 3 , 0 , 0
       0     .09       0  399.23     .04       0  408.42     .09       0
Bank Sta=399.23,408.42
XS Rating Curve= 0 ,0
Exp/Cntr=0.3,0.1

Type RM Length L Ch R = 1 ,2377.44 ,96.16,91.44,66.63
XS GIS Cut Line= 6
     634493.2576    4333372.9532      634321.718    4333439.4455
     634160.6842    4333463.1203      634124.129    4333456.4299
     634038.9756    4333485.3454     633723.3185    4333907.4126
#Sta/Elev= 30
       0  954.31   21.46  952.77   73.59  951.96  134.92  946.41  150.25  945.55
  276.11  942.41   340.6  940.01  352.87  939.19     359  938.62  364.55  939.13
  367.32  939.59  381.19   940.3  395.96  941.87  480.02  944.56  553.57   942.9
  633.24  943.44   722.1  942.74  749.68  944.98  801.77  945.82  878.38  948.82
  924.34  948.94  927.41  949.17   936.6  951.12  954.98  951.34  973.37   952.5
  982.56  953.53  985.63  953.49  991.75  952.45  994.82  952.66 1000.95  954.36
#Mann= 3 , 0 , 0
       0     .09       0  352.87     .04       0  364.55     .09       0
Bank Sta=352.87,364.55
XS Rating Curve= 0 ,0
Exp/Cntr=0.3,0.1

Type RM Length L Ch R = 1 ,2286    ,113.79,91.44,31.15
XS GIS Cut Line= 6
     634607.0286    4333285.6405     634167.3323    4333365.7958
     634154.7194    4333372.5253     634151.9864     4333372.675
     634020.3295    4333422.5226     633710.0893    4333894.1834
#Sta/Elev= 30
       0  954.03   30.61  953.51   45.92  951.65   70.41  950.93  104.08  951.54
  168.37  949.61  217.35  949.32  266.33  948.23  345.92   944.4  437.76  943.16
  443.88  942.21  455.78  939.21  458.53  938.69  464.01  939.38  528.28  940.36
  555.82  941.61  635.47  943.15  761.27  942.77  801.15  943.13  828.77  944.19
  868.65  943.36  923.88  944.13 1065.02  949.12 1092.63  948.93  1104.9  951.31
 1120.24  951.24 1150.93  953.82  1163.2  952.75 1166.27  952.97 1169.34   954.1
#Mann= 3 , 0 , 0
       0     .09       0  455.78     .04       0  464.01     .09       0
Bank Sta=455.78,464.01
XS Rating Curve= 0 ,0
Exp/Cntr=0.3,0.1

Type RM Length L Ch R = 1 ,2194.56 ,120,91.44,57.96
XS GIS Cut Line= 4
     634445.6325    4332978.7233     634120.8441    4333275.7136
     634041.7521    4333374.4908     633691.5685    4333878.3084
#Sta/Elev= 30
       0  954.52   42.79  949.97   76.41  948.09  103.91  947.46  171.15  947.32
     217  945.75  299.51  944.64  382.03  941.57   412.6  941.89  473.24  938.69
  479.27  938.47   485.3  938.64  545.55  939.92  572.78  941.43  634.14  942.92
     809  942.41  848.88  944.31   885.7  943.61  953.19  944.41 1063.63  948.44
  1066.7  948.62 1078.97  951.45 1085.11  952.05 1103.51  952.29 1121.92  951.64
 1134.19  953.05 1149.53  953.25 1164.87  954.24 1174.07  953.29 1180.21  954.54
#Mann= 3 , 0 , 0
       0     .09       0  473.24     .04       0   485.3     .09       0
Bank Sta=473.24,485.3
XS Rating Curve= 0 ,0
Exp/Cntr=0.3,0.1

Type RM Length L Ch R = 1 ,2103.12 ,116.4,91.44,86.33
XS GIS Cut Line= 4
     634204.8612    4332846.4313     634032.4372    4333208.9377
     633993.9872    4333340.3497     633680.9851    4333841.2666
#Sta/Elev= 30
       0  954.12   58.22  950.66   88.86  947.52  144.02  945.43  217.57     943
   300.3  942.29  334.01  941.13  392.23  940.55  404.47  939.44  450.11  939.93
  453.15  939.63  456.19  938.15  459.23  937.65  468.36     938  507.92  939.98
   535.3   939.5  568.95  941.47  593.43  940.52  614.86  940.56  636.28  941.94
  786.24  942.54  838.27  944.28  954.56  945.51 1009.65   947.4 1018.83   949.2
 1028.02  952.04 1034.14  952.58 1086.16  952.13 1101.47  953.72 1129.01  954.19
#Mann= 3 , 0 , 0
       0     .09       0  456.19     .04       0  468.36     .09       0
Bank Sta=456.19,468.36
XS Rating Curve= 0 ,0
Exp/Cntr=0.3,0.1