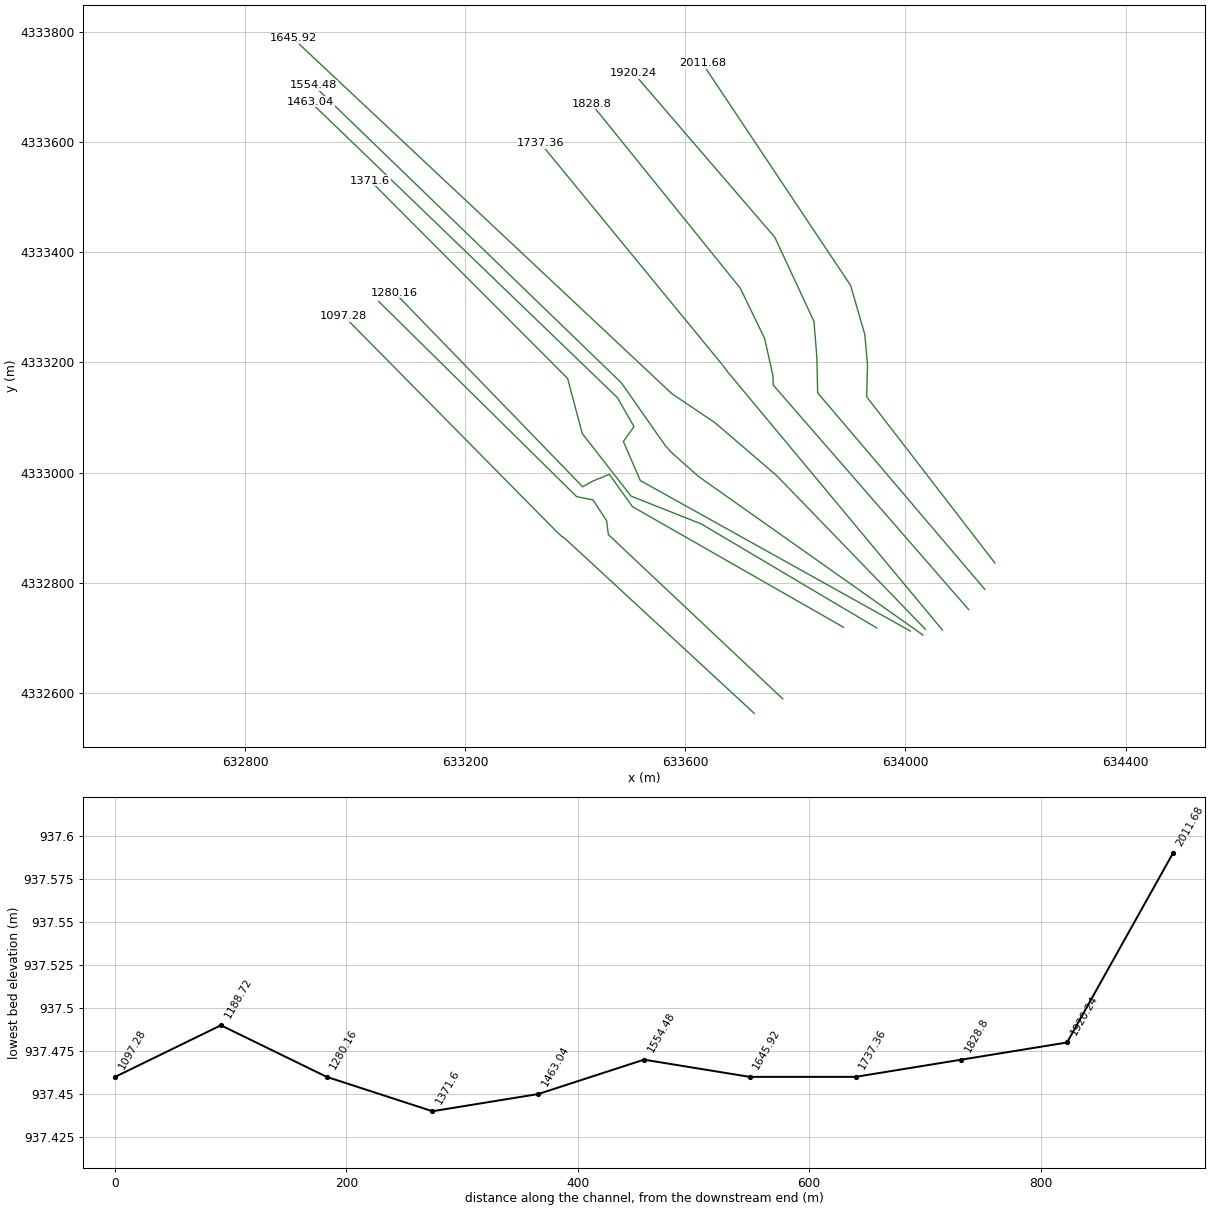
HEC-RAS study BeaverCreek.prj: BeaverCreek

--- BeaverCreek.g01 (geometry) --- (continued)

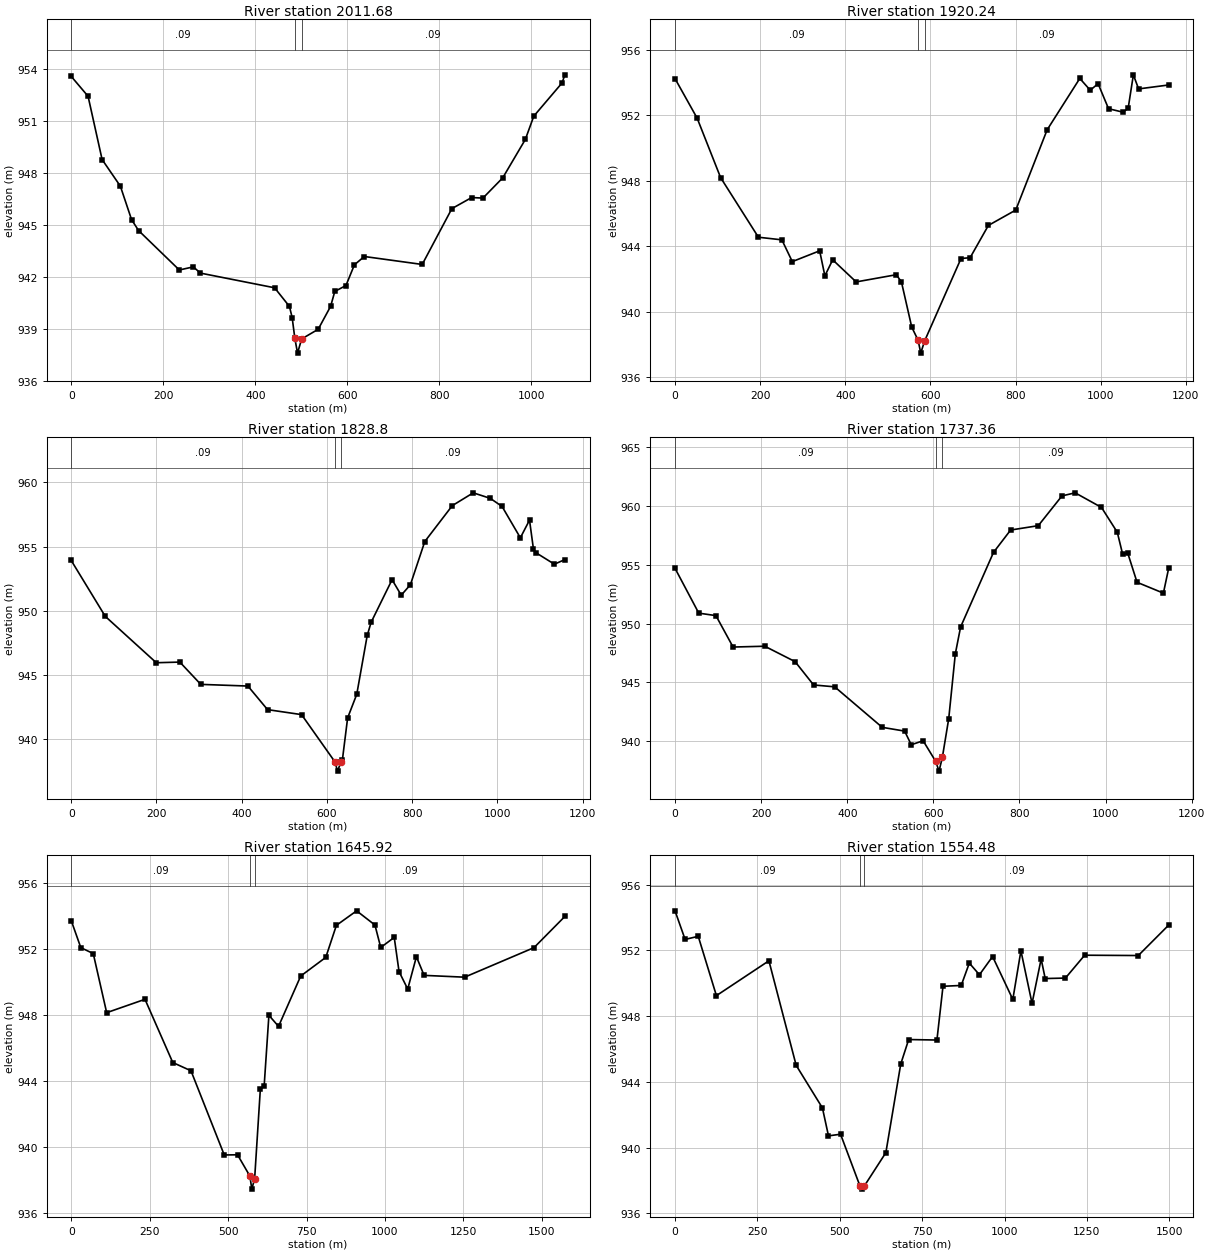
Type RM Length L Ch R = 1 ,2011.68 ,90.55,91.44,85.8
XS GIS Cut Line= 6
     634162.5277     4332835.848     633929.5022    4333137.6991
     633931.0066    4333195.4119     633926.0976    4333250.9206
     633900.1334    4333340.1057     633630.7142    4333743.3706
#Sta/Elev= 30
       0   953.6   36.61  952.45   67.11  948.79  106.77  947.25  131.18  945.31
  146.43  944.68   234.9   942.4  265.41  942.58  280.66  942.22     442  941.37
  474.26  940.29  480.13  939.65  485.99  938.44  491.86  937.59  500.75  938.41
   536.7  938.97  563.77   940.3  572.79  941.16  597.03   941.5  615.45   942.7
  636.93  943.18  762.78  942.72  827.24  945.95  870.22  946.59  894.77  946.56
  937.75  947.73  986.86  949.95 1005.28   951.3 1066.67  953.22  1072.8  953.69
#Mann= 3 , 0 , 0
       0     .09       0  485.99     .04       0  500.75     .09       0
Bank Sta=485.99,500.75
XS Rating Curve= 0 ,0
Exp/Cntr=0.3,0.1

Type RM Length L Ch R = 1 ,1920.24 ,80.46,91.44,94.66
XS GIS Cut Line= 6
     634144.0069    4332788.2229     633840.4366    4333144.8097
      633839.071    4333208.3064      633833.694    4333274.5528
     633762.6277     4333427.107     633506.3598    4333724.8497
#Sta/Elev= 30
       0  954.25   52.03  951.83  107.13   948.2  195.89  944.56  250.99   944.4
  275.47  943.07  339.75  943.73  351.99   942.2  370.36  943.18  425.45  941.83
  519.72  942.27  531.82  941.83  555.99  939.07  571.09  938.26  577.13  937.48
   586.2  938.22  671.72  943.26  693.14  943.31  735.98  945.28  800.34  946.22
  873.99  951.12  950.72  954.26  975.27  953.54  993.69  953.94 1018.24  952.41
    1052   952.2 1064.28  952.43 1076.55  954.48 1088.83  953.62 1159.42  953.86
#Mann= 3 , 0 , 0
       0     .09       0  571.09     .04       0   586.2     .09       0
Bank Sta=571.09,586.2
XS Rating Curve= 0 ,0
Exp/Cntr=0.3,0.1

Type RM Length L Ch R = 1 ,1828.8  ,55.58,91.44,93.31
XS GIS Cut Line= 6
     634114.9026    4332751.1811     633759.8267     4333158.739
     633759.1653    4333176.2677     633743.9994    4333243.6516
     633699.9069    4333334.7404     633429.6304    4333669.2871
#Sta/Elev= 30
       0  953.91   79.85  949.55  199.63  945.93  254.91  945.98  304.05  944.24
  414.62  944.11  460.69  942.27  540.54  941.88  618.94  938.19     625  937.47
   633.3  938.21  636.37  938.35  648.63  941.62   670.1  943.47  694.63  948.06
  703.83  949.09  752.94  952.41  774.45   951.2  795.95  952.02  829.74  955.39
  894.26  958.19  943.41  959.19  983.34  958.76 1010.99  958.13    1054  955.68
  1075.5  957.06 1084.72   954.8 1090.86  954.51 1133.87  953.62 1158.45  953.98
#Mann= 3 , 0 , 0
       0     .09       0  618.94     .04       0   633.3     .09       0
Bank Sta=618.94,633.3
XS Rating Curve= 0 ,0
Exp/Cntr=0.3,0.1

Type RM Length L Ch R = 1 ,1737.36 ,75.85,91.44,95.89
XS GIS Cut Line= 5
     634067.2776    4332714.1394     633686.8016    4333171.0554
     633676.5234    4333183.3088     633668.9252    4333193.6861
     633337.0261    4333597.8495
#Sta/Elev= 30
       0  954.69   55.17  950.88   95.01  950.67  134.85     948  208.41  948.07
   278.9  946.76  321.81  944.78  370.85  944.62  481.19  941.18  533.29  940.86
  548.61   939.7   576.2  940.04  605.25   938.3  613.15  937.46  620.87  938.63
  635.68  941.92  650.97  947.42   663.2   949.7  739.66  956.04  779.42  957.94
  843.64  958.31  898.69  960.84  929.28   961.1  990.44  959.86 1027.14  957.75
 1039.38  955.91 1051.61  955.96 1073.02   953.5 1134.19  952.58 1146.42  954.69
#Mann= 3 , 0 , 0
       0     .09       0  605.25     .04       0  620.87     .09       0
Bank Sta=605.25,620.87
XS Rating Curve= 0 ,0
Exp/Cntr=0.3,0.1

Type RM Length L Ch R = 1 ,1645.92 ,93.12,91.44,82.57
XS GIS Cut Line= 5
     634036.0567    4332715.7269     633766.2207    4332994.2923
     633653.5238    4333090.8443     633575.6046    4333143.2111
     632887.2335    4333788.3499
#Sta/Elev= 30
       0  953.73   30.54  952.09   70.24  951.73  112.99  948.15  235.14  948.96
   323.7  945.13  381.72  944.63  487.77  939.53  530.17  939.54  569.54  938.25
   575.6  937.46  584.68   938.1  602.85  943.52  614.97   943.7  630.11  947.99
  660.84  947.32  731.52  950.37  811.42   951.5  845.22  953.44  909.76  954.32
  968.14  953.46  986.58   952.1 1029.61  952.71 1044.97  950.64 1072.63  949.58
 1100.29  951.54 1124.87  950.41 1253.94   950.3  1475.2  952.09 1573.54  953.98
#Mann= 3 , 0 , 0
       0     .09       0  569.54     .04       0  584.68     .09       0
Bank Sta=569.54,584.68
XS Rating Curve= 0 ,0
Exp/Cntr=0.3,0.1

Type RM Length L Ch R = 1 ,1554.48 ,90.24,91.44,56.22
XS GIS Cut Line= 6
     634031.8233    4332705.1435     633623.7865    4332993.1227
     633574.9156    4333036.4272     633563.1792      4333049.64
     633483.7378    4333163.0059     632924.9367     4333702.757
#Sta/Elev= 30
       0   954.4   30.64  952.66   70.47  952.85  125.62  949.24  284.95  951.36
  367.67     945  447.34  942.41  465.72  940.71  502.36  940.81  561.11  937.67
  567.97  937.47  573.86  937.64  639.87  939.69  685.01  945.08  709.08  946.57
  794.82  946.54  813.25  949.81  868.52  949.86  893.09  951.22  923.79  950.51
  963.72  951.62 1025.13  949.01  1049.7  951.97 1083.48  948.77 1111.11  951.47
  1123.4  950.28 1184.81  950.31 1243.16   951.7 1405.91  951.68 1498.03  953.53
#Mann= 3 , 0 , 0
       0     .09       0  561.11     .04       0  573.86     .09       0
Bank Sta=561.11,573.86
XS Rating Curve= 0 ,0
Exp/Cntr=0.3,0.1

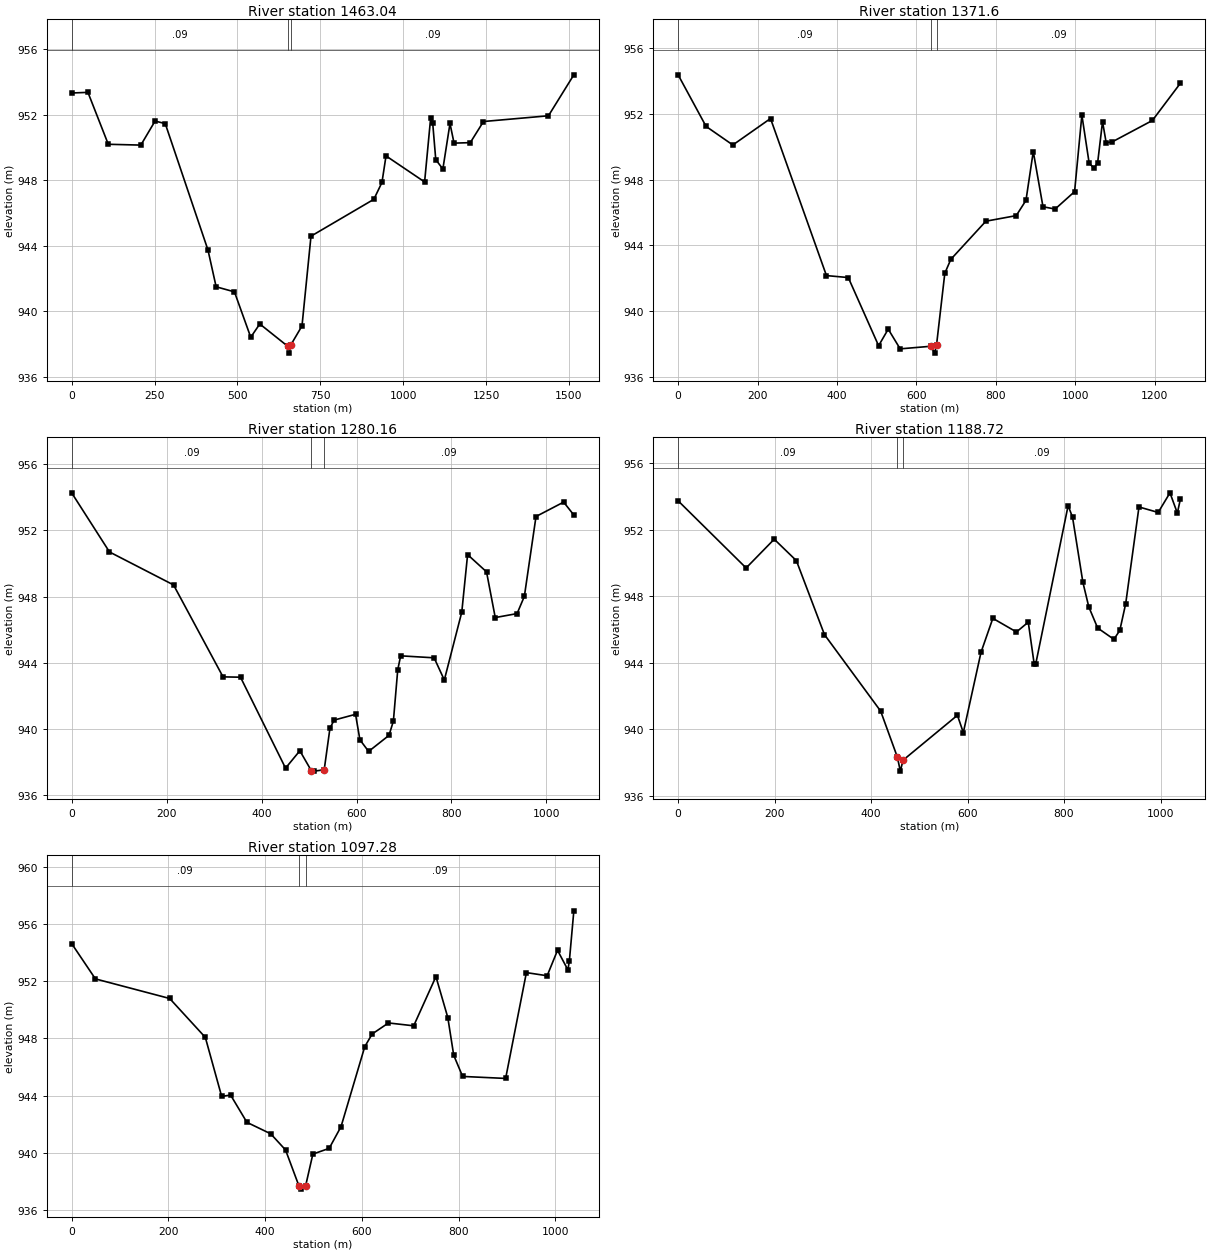
Type RM Length L Ch R = 1 ,1463.04 ,92.09,91.44,101.84
XS GIS Cut Line= 6
     634008.9368    4332712.4196     633518.1453    4332985.6085
     633487.4112     4333056.517     633506.6729    4333083.3987
     633476.8396    4333135.7948     632918.5867    4333673.1236
#Sta/Elev= 30
       0  953.33   49.11  953.37   110.5   950.2  208.72  950.15  251.69  951.62
  282.39  951.46   411.3  943.74  435.86   941.5   491.1  941.19  540.22  938.42
  567.54  939.23  651.17  937.88  656.14  937.45  661.42  937.96  694.85  939.11
  721.98  944.59  911.57  946.84  936.07  947.87  948.32  949.49  1064.7   947.9
 1083.08  951.83  1089.2  951.48 1098.39  949.26 1119.83  948.69 1141.27  951.47
 1153.52  950.27 1202.52   950.3 1242.33  951.59 1438.34  951.94  1514.9  954.44
#Mann= 3 , 0 , 0
       0     .09       0  651.17     .04       0  661.42     .09       0
Bank Sta=651.17,661.42
XS Rating Curve= 0 ,0
Exp/Cntr=0.3,0.1

Type RM Length L Ch R = 1 ,1371.6  ,17.64,91.44,130.27
XS GIS Cut Line= 6
      633947.862    4332717.9759     633629.1261    4332906.7452
     633501.3177    4332957.3774     633412.6292    4333071.0956
     633386.1275       4333170.9     633027.1102    4333530.2483
#Sta/Elev= 30
       0  954.38   70.41  951.24  137.77  950.11  232.67  951.72   373.5  942.16
  428.48  942.04  504.86  937.89  529.02   938.9  559.16   937.7  637.55  937.86
  645.75  937.44  650.64  937.92  671.54   942.3  686.72  943.15  774.94  945.47
  851.44  945.81  875.92  946.74  894.28  949.71  918.76  946.35  949.36  946.21
  998.32  947.27 1016.68  951.93 1035.04     949 1047.28   948.7 1056.46  949.04
  1068.7  951.53 1077.88  950.25 1093.18   950.3 1194.16   951.6 1264.54  953.86
#Mann= 3 , 0 , 0
       0     .09       0  637.55     .04       0  650.64     .09       0
Bank Sta=637.55,650.64
XS Rating Curve= 0 ,0
Exp/Cntr=0.3,0.1

Type RM Length L Ch R = 1 ,1280.16 ,63.18,91.44,39.28
XS GIS Cut Line= 6
     633887.3233    4332719.3328     633503.8974    4332938.1951
     633461.8137    4332996.9685     633431.0687    4332984.1582
     633413.4097    4332974.3108     633072.0895    4333326.5187
#Sta/Elev= 30
       0  954.26   79.71  950.69  214.61   948.7  318.86  943.15  355.65  943.13
  450.53  937.64  480.65  938.69  504.74  937.49  510.77  937.46  531.95  937.54
  544.06  940.05  552.86  940.54  597.96  940.89  607.16  939.35  625.55  938.65
  668.46  939.62  677.66  940.48  686.85  943.58  692.99  944.42  763.49   944.3
  784.95  942.96  821.73  947.06  833.99  950.53  873.84  949.49  892.23  946.73
  938.22  946.97  953.54  948.01  978.07  952.83 1036.31   953.7 1057.76  952.92
#Mann= 3 , 0 , 0
       0     .09       0  504.74     .04       0  531.95     .09       0
Bank Sta=504.74,531.95
XS Rating Curve= 0 ,0
Exp/Cntr=0.3,0.1

Type RM Length L Ch R = 1 ,1188.72 ,80.33,91.44,91.27
XS GIS Cut Line= 6
     633777.0447    4332589.2899     633460.1419    4332887.4942
      633456.974    4332912.6587     633432.3606    4332950.3329
     633402.5949     4332956.286     633042.9852    4333310.6437
#Sta/Elev= 30
       0  953.75  140.96  949.71  199.19  951.44  245.15  950.15  303.38   945.7
  419.83   941.1  454.64  938.32  460.56  937.49  466.35  938.15  578.94  940.85
  591.18  939.81  627.89  944.64  652.37  946.68  701.33  945.86  725.81  946.45
  738.05  943.94  741.11  943.91  808.42  953.46   817.6  952.76  839.02  948.85
  851.26  947.37  869.62   946.1  903.28  945.42  915.52  945.95  927.75  947.56
  955.29  953.38  995.07  953.05 1019.55  954.23 1034.85  953.01 1040.97  953.83
#Mann= 3 , 0 , 0
       0     .09       0  454.64     .04       0  466.35     .09       0
Bank Sta=454.64,466.35
XS Rating Curve= 0 ,0
Exp/Cntr=0.3,0.1

Type RM Length L Ch R = 1 ,1097.28 ,1074.2,1097.28,1051.81
XS GIS Cut Line= 5
     633725.2392    4332562.9241     633380.1052     4332881.508
     633375.7543    4332883.9183     633367.1776     4332891.735
     632979.4851    4333284.1853
#Sta/Elev= 30
       0  954.63   49.12  952.16  202.61  950.79  276.29  948.07  310.06  943.94
  328.48  944.04  362.25  942.13  411.37  941.33  442.07   940.2  469.69  937.69
  474.67  937.46  483.37  937.66  498.53  939.91  532.24  940.31  556.76  941.83
   605.8  947.42  621.12  948.31  654.84  949.08  706.94  948.88  752.91  952.32
  777.43  949.46  789.68  946.82  808.07  945.34  896.95   945.2  939.86   952.6
  982.77  952.38 1004.22  954.16 1025.67  952.79 1028.74  953.44 1037.93  956.92
#Mann= 3 , 0 , 0
       0     .09       0  469.69     .04       0  483.37     .09       0
Bank Sta=469.69,483.37
XS Rating Curve= 0 ,0
Exp/Cntr=0.3,0.1
LCMann Table=0

Chan Stop Cuts=-1
Use User Specified Reach Order=0
Composite Channel Slope=5